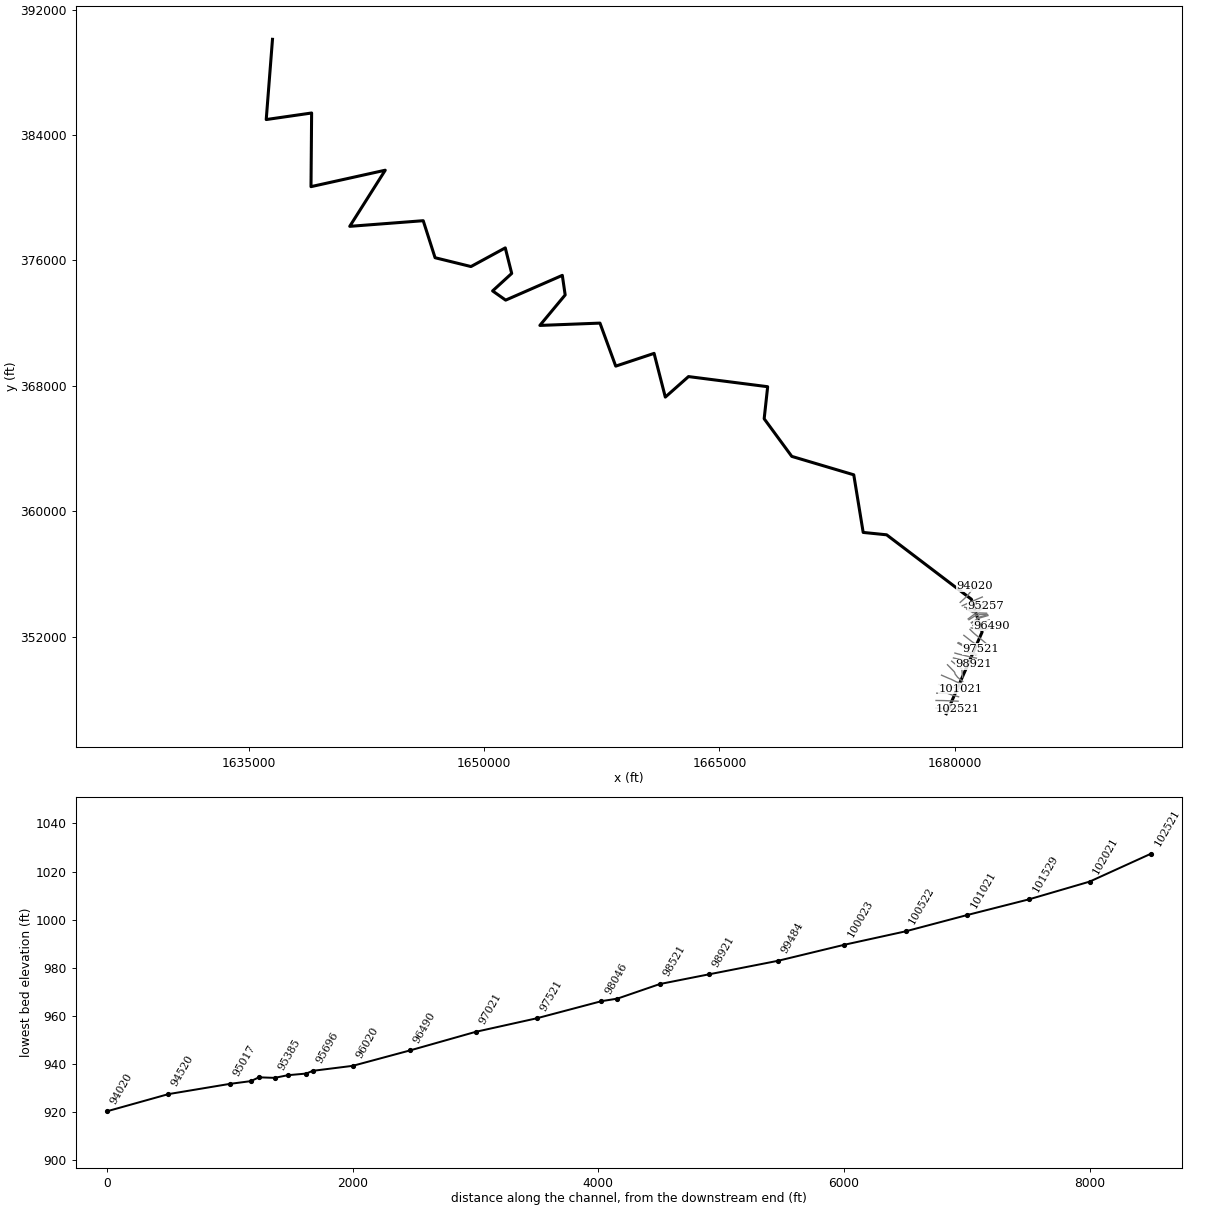
--- SFFSHGCK.prj (project) ---

Proj Title=SFFSHGCK
Current Plan=p01
Default Exp/Contr=0,0
English Units
Geom File=g01
Flow File=f01
Plan File=p01
BEGIN DESCRIPTION:
---------- MODELED AS PART OF WVEMD CTP PROGRAM, 2023----------
Stream Name: South Fork Fishing Creek
Flood Zone:  AFH
Wetzel County, WV
HEC-RAS Version: RAS 6.3
Vertical Datum: NAVD88
Projection: NAD 1983 StatePlane West Virginia S FIPS 4702 (US Feet)
Terrain: 1-meter West Virginia FEMA R3 South Central (collected 2018-2020)
Land Use: 2019 NLCD
Hydrologic Method:
WV SIR2010-5033 regression equations
Additional Model Notes:
Leveraged XS
END DESCRIPTION:
DSS Export Rating Curves= 0
DSS Export Rating Curve Sorted= 0
DSS Export Volume Flow Curves= 0
DXF OffsetX= 0
DXF OffsetY= 0
DXF ScaleX= 0
DXF ScaleY= 0

--- SFFSHGCK.p01 (plan) ---

Plan Title=Floodplain
Program Version=6.31
Short Identifier=Floodplain
Geom File=g01
Flow File=f01
Subcritical Flow
K Sum by GR= 0
Std Step Tol= 0.01
Critical Tol= 0.01
Num of Std Step Trials= 20
Max Error Tol= 0.3
Flow Tol Ratio= 0.001
Split Flow NTrial= 30
Split Flow Tol= 0.02
Split Flow Ratio= 0.02
Log Output Level= 0
Friction Slope Method= 1
Unsteady Friction Slope Method= 2
Unsteady Bridges Friction Slope Method= 1
Parabolic Critical Depth
Global Vel Dist= 0 , 0 , 0
Global Log Level= 0
CheckData=True
Encroach Param=-1 ,0,0, 0
Mapping Interval=1HOUR
Computation Time Step Use Courant=        0
Computation Time Step Use Time Series=    0
Computation Time Step Count To Double=0
Computation Time Step Max Doubling=0
Computation Time Step Max Halving=0
Computation Time Step Residence Courant=0
Run HTab= 0
Run UNet= 0
Run Sediment= 0
Run PostProcess= 0
Run WQNet= 0
Run RASMapper=-1
UNET Theta= 0
UNET Theta Warmup= 0
UNET ZTol= 0
UNET ZSATol= 0
UNET MxIter= 0
UNET Max Iter WO Improvement= 0
UNET MaxInSteps= 0
UNET DtIC= 0
UNET DtMin= 0
UNET MaxCRTS= 0
UNET WFStab= 0
UNET SFStab= 0
UNET WFX= 1
UNET SFX= 1
UNET Gravity=32.17405
UNET 1D Methodology=Finite Difference
UNET DSS MLevel= 1
UNET Pardiso=0
UNET DZMax Abort= 0
UNET Use Existing IB Tables= 0
UNET Froude Reduction=False
UNET Froude Limit= 0
UNET Froude Power= 0
UNET D1 Cores= 0
UNET WindReference=Eulerian
UNET WindDragFormulation=Hsu (1988)
UNET D2 Coriolis=0
UNET D2 Cores= 0
UNET D2 Theta= 1
UNET D2 Theta Warmup= 1
UNET D2 Z Tol= 0.01
UNET D2 Volume Tol= 0.01
UNET D2 Max Iterations= 20
UNET D2 Equation= 0
UNET D2 RampUpFraction=0.1
UNET D2 TimeSlices= 1
UNET D2 Turbulence Formulation=Non-Conservative (original)
UNET D2 Eddy Viscosity=0.3
UNET D2 Transverse Eddy Viscosity=0.1
UNET D2 Smagorinsky Mixing=0
UNET D2 BCVolumeCheck=0
UNET D2 Cores=0
UNET D2 SolverType=PARDISO (Direct)
UNET D2 Minimum Iterations= 3
UNET D2 Maximum Iterations= 30
UNET D2 Restart Number= 10
UNET D2 Relaxation Coeff=1.3
UNET D2 SOR Precondition Iterations= 10
UNET D2 ILUT Maximum Fill= 8
UNET D2 ILUT Tolerance=1E-08
UNET D2 Convergence Tolerance=0.00001
UNET D1D2 MaxIter= 0
UNET D1D2 ZTol=0.01
UNET D1D2 QTol=0.1
UNET D1D2 MinQTol=1
Write IC File= 0
Write IC File at Fixed DateTime=0
Write IC File at Sim End=0
Echo Input=False
Echo Parameters=False
Echo Output=False
Write Detailed= 0
HDF Write Warmup=0
HDF Write Time Slices=0
HDF Flush=0
HDF Compression= 1
HDF Chunk Size= 1
HDF Spatial Parts= 1
HDF Use Max Rows=0
HDF Fixed Rows= 1
Calibration Method= 0
Calibration Iterations= 20
Calibration Max Change=0.05
Calibration Tolerance=0.2
Calibration Maximum=1.5
Calibration Minimum=0.5
Calibration Optimization Method= 1
WQ AD Non Conservative
WQ ULTIMATE=-1
WQ Max Comp Step=1HOUR
WQ Output Interval=15MIN
WQ Output Selected Increments= 0
WQ Create Restart=0
WQ Fixed Restart=0
WQ System Summary=0
WQ Write To DSS=0
Sorting and Armoring Iterations= 10
XS Update Threshold= 0.02
Bed Roughness Predictor= 0
Hydraulics Update Threshold= 0.02
Energy Slope Method= 1
Volume Change Method= 1
Sediment Retention Method= 0
Sediment TS Multiplier= 1
Warm Up Method= 0
XS Weighting Method= 0
Number of US Weighted Cross Sections= 1
Number of DS Weighted Cross Sections= 1
Upstream XS Weight=0
Main XS Weight=1
Downstream XS Weight=0
Number of DS XS's Weighted with US Boundary= 1
Upstream Boundary Weight= 1
Weight of XSs Associated with US Boundary= 0
Number of US XS's Weighted with DS Boundary= 1
Downstream Boundary Weight= 0.5
Weight of XSs Associated with DS Boundary= 0.5
Percentile Method= 0
Sediment Output Level= 3
Mass or Volume Output= 0
Output Increment Type= 1
Profile and TS Output Increment= 1
Transport Output Increment 1
XS Output Flag= 0
XS Output Increment= 10
Read HDF5 Sediment Hotstart= 0
Sediment Hotstart Type= 0
Write Gradation File= 0
Read Gradation Hotstart= 0
Write HDF5 File= 1
Write Binary Output= 1
Write DSS Sediment File= 0
DSS Sediment Output Type= 1
SV Curve= 0
Specific Gage Flag= 0
Subcell Erosion Methods= 0
Subcell Deposition Methods= 0
Advection Scheme= 1
Matrix Solver= 0
Implicit Weighting Factor= 1
Maximum Outer Loop Convergence Iterations= 5
Convergence Maximum Absolute= 0.001
Convergence RMSE= 0.0001
Grain Fractions Max Abs Error= 0.001
Max Subgrid Regions= 1
Max Subgrid Length Scale= 3.402823E+38
Initial Layer Thickness= 3.402823E+38
Min Layer Thickness= 3.402823E+38
Max Layer Thickness= 3.402823E+38
Number of Layers= 5

--- SFFSHGCK.f01 (steady flow) ---

Flow Title=Flow
Program Version=4.00
Number of Profiles=1
Profile Names=F01pct
River Rch & RM=SFFSHGCK,Main,102521
     665
River Rch & RM=SFFSHGCK,Main,99484
     782
River Rch & RM=SFFSHGCK,Main,96490
    1130
River Rch & RM=SFFSHGCK,Main,93513
    1520
River Rch & RM=SFFSHGCK,Main,90885
    2060
River Rch & RM=SFFSHGCK,Main,89012
    2340
River Rch & RM=SFFSHGCK,Main,81508
    2610
River Rch & RM=SFFSHGCK,Main,76506
    3100
River Rch & RM=SFFSHGCK,Main,74071
    4990
River Rch & RM=SFFSHGCK,Main,69006
    5560
River Rch & RM=SFFSHGCK,Main,63506
    7290
River Rch & RM=SFFSHGCK,Main,37500
    8100
River Rch & RM=SFFSHGCK,Main,31500
    9880
Boundary for River Rch & Prof#=SFFSHGCK,Main      ,1
Up Type=0
Dn Type=3
Dn Slope=0.000329

--- SFFSHGCK.g01 (geometry) ---

Geom Title=Geometry
Program Version=6.31

River Reach=SFFSHGCK        ,Main
Reach XY= 30
     1679472.256      347083.813     1681759.469      352297.199
     1681075.155      354387.819     1675667.149       358497.96
     1674172.539      358649.403     1673571.162      362325.092
     1669617.456      363500.557     1667856.089      365900.897
     1668079.755      367944.929     1663029.699      368590.764
     1661550.481      367281.292     1660834.191      370070.548
     1658387.301      369257.064     1657382.972      372001.678
      1653547.33      371853.369     1655162.347      373798.326
     1654980.696      375047.727     1651366.885      373467.515
     1650533.951      374055.2951651752.16675957375170.279251367
     1651341.871      376800.174     1649154.312      375609.477
     1646864.021      376173.073      1646107.74      378533.899
     1641420.414      378174.183     1643685.554      381754.693
     1638949.398      380706.138     1638989.273      385404.278
     1636093.264      384986.508     1636493.101      390104.613

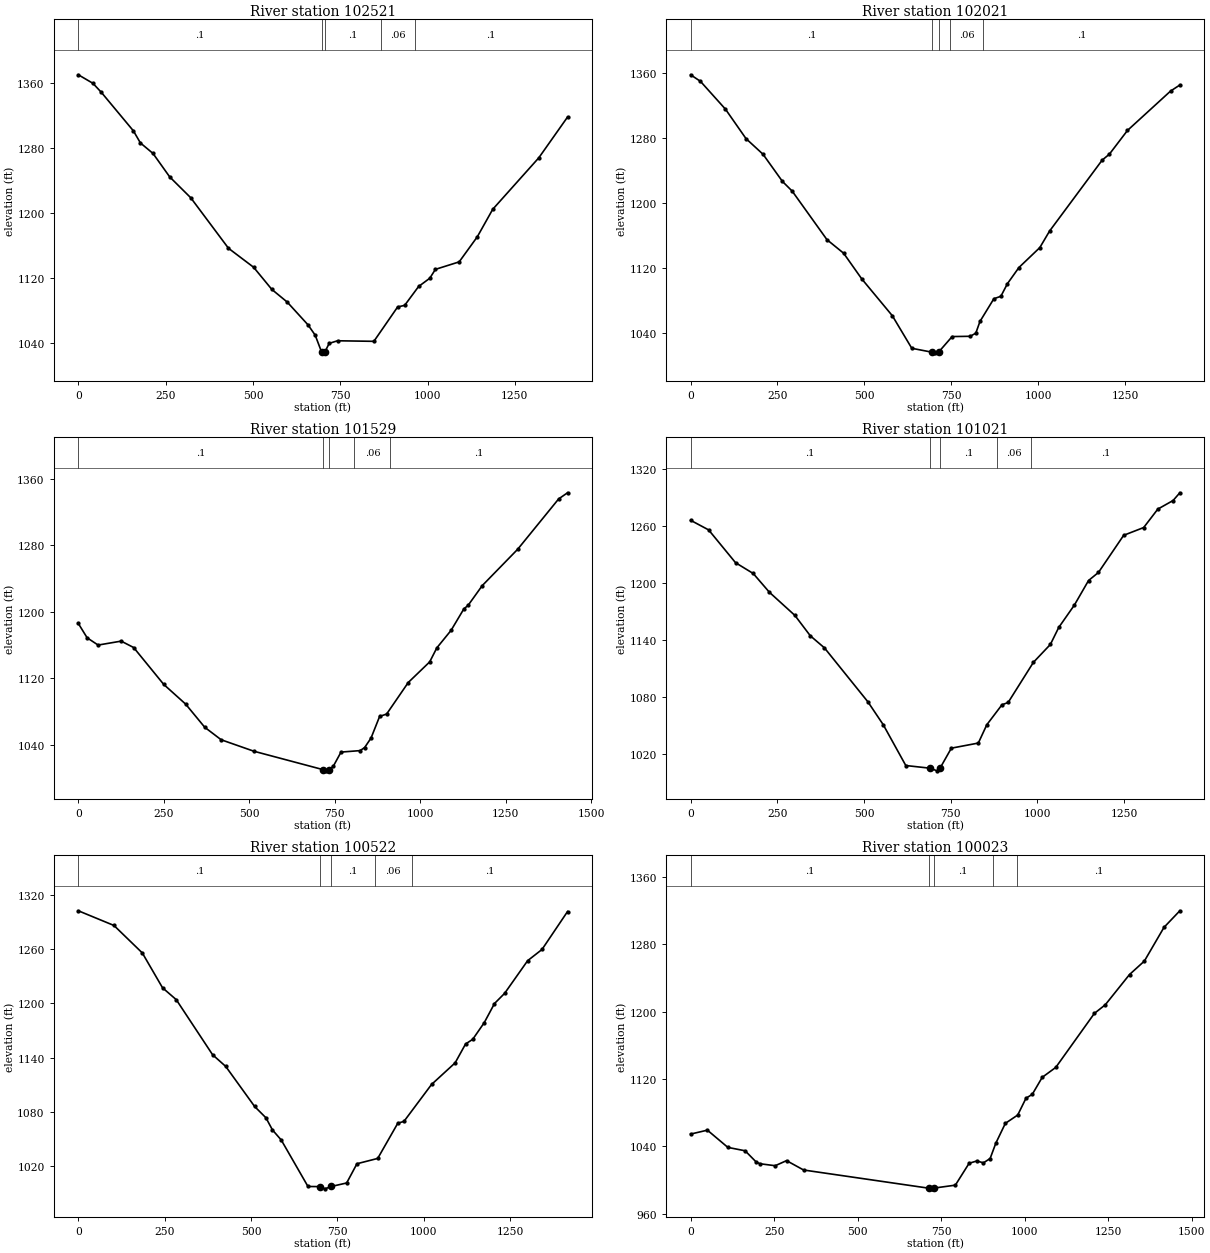
Type RM Length L Ch R = 1 ,102521  ,499.9,500,499.8
XS GIS Cut Line= 6
1678798.47232334347446.8674124181678997.14876325347439.105945006
1679192.31241493347431.4832568321679623.23379718347414.650613338
1680098.65246576347396.0788000821680198.18605934347392.191668749
#Sta/Elev= 30
       0 1370.04    41.7 1359.56    65.7 1348.52   157.8 1300.89   177.8 1286.05
   213.8 1273.14   261.7  1244.2   321.9 1218.52     430 1156.26     502 1132.85
   554.1 1105.58   598.1 1090.02   657.5 1062.01   678.2 1049.25  696.43 1028.62
   702.2 1027.44   706.2 1028.61   718.2 1039.08   742.2 1042.31   846.3 1041.62
   914.3 1083.97   934.4 1085.95   974.4 1109.21  1006.4 1119.38  1022.4 1130.29
  1090.5 1139.52  1142.5 1170.47  1186.5 1204.25  1318.6  1267.8  1400.8 1317.95
#Mann= 5 ,-1,0
       0      .1       0  696.43    .045       0   706.2      .1       0
  865.39     .06       0  962.89      .1       0
Bank Sta=696.43,706.2
XS Rating Curve= 0 ,0
Exp/Cntr(USF)=0,0
Exp/Cntr=0.3,0.1

Type RM Length L Ch R = 1 ,102021  ,490.1,491.6,487.6
XS GIS Cut Line= 6
1678819.86434092347930.2421018331678920.56919201347928.303457424
1679219.50100884347924.8575981711679314.57890268 347923.17453067
1679402.05510567347920.2828041761680226.61316784347883.220214263
#Sta/Elev= 30
       0 1357.71    28.3 1349.65   100.3  1315.4   159.4 1279.21   208.3 1260.01
   264.3 1226.55   292.3 1214.66   392.3 1154.98   440.3 1138.29   492.3 1106.81
   580.4 1061.46   636.4 1021.42   695.1 1016.56   704.5 1015.82  713.571016.735
   752.5 1035.83   804.6 1036.16   820.6 1040.03   832.6 1054.44   872.6 1082.36
   892.7 1085.35   911.7 1100.92   944.7 1120.73  1004.8 1145.23  1032.8 1165.51
  1184.2 1252.77    1205  1260.1    1257 1289.26    1381 1337.68  1407.7 1345.11
#Mann= 5 ,-1,0
       0      .1       0   695.1    .045       0  713.57      .1       0
  747.29     .06       0  842.29      .1       0
Bank Sta=695.1,713.57
XS Rating Curve= 0 ,0
Exp/Cntr(USF)=0,0
Exp/Cntr=0.3,0.1

Type RM Length L Ch R = 1 ,101529  ,500.4,508.4,504.3
XS GIS Cut Line= 6
1678862.28420359348395.4839535061678962.92278184348392.611912012
1679358.46562593348399.4504810121679532.55714126348394.119126841
1679785.21378817348297.3391366751680257.31520617348166.245238751
#Sta/Elev= 30
       0 1185.83    25.8 1168.57    57.9 1159.83   125.4 1164.57   161.9 1156.86
   249.9 1112.48   313.9 1088.83   369.9 1060.89   417.9 1045.88   513.9 1032.04
  716.131009.906   725.2 1008.48  734.861009.914   746.4 1014.33   768.6 1031.05
   824.5 1032.82   837.7 1036.53   856.4 1047.94   881.5 1073.95     902 1076.83
   965.3 1114.78    1028 1139.59  1048.9 1156.46  1090.5  1177.5  1127.9 1203.31
  1140.4 1207.63  1181.8  1231.4  1285.4  1275.1  1405.3 1335.71  1431.3 1343.08
#Mann= 5 ,-1,0
       0      .1       0  716.13    .045       0  734.86      .1       0
  807.49     .06       0  913.15      .1       0
Bank Sta=716.13,734.86
XS Rating Curve= 0 ,0
Exp/Cntr(USF)=0,0
Exp/Cntr=0.3,0.1

Type RM Length L Ch R = 1 ,101021  ,496.5,498.6,489.8
XS GIS Cut Line= 6
 1678993.1182595348950.0842222571679289.85749543348891.684076592
1679387.45244458348874.9472334241679569.31198901348850.925627917
 1679813.0519871348795.3266577571680378.41043642348684.767823756
#Sta/Elev= 30
       0 1266.12      52 1255.97   129.6 1221.39   180.6    1210   227.4 1190.15
   300.7 1165.82   345.2 1144.31   385.9 1131.59   511.2 1074.72   555.5 1050.56
   620.6 1007.49   690.4 1004.67   710.9 1001.88   719.3 1004.63     752 1025.79
   829.8 1031.18   854.3 1050.49     898 1071.56   915.8 1073.96   988.7 1116.33
  1037.6 1135.17  1061.8 1153.14  1106.9 1176.74  1147.7  1202.6  1176.3 1211.12
    1249 1250.28  1306.7 1258.47  1347.5 1277.92  1391.5 1286.97    1411 1295.13
#Mann= 5 ,-1,0
       0      .1       0   690.4    .045       0   719.3      .1       0
  884.91     .06       0  982.52      .1       0
Bank Sta=690.4,719.3
XS Rating Curve= 0 ,0
Exp/Cntr(USF)=0,0
Exp/Cntr=0.3,0.1

Type RM Length L Ch R = 1 ,100522  ,500.1,499.2,486.2
XS GIS Cut Line= 6
1679172.24519785349542.6315935851679629.27479559349343.455482751
 1679782.4792136349283.894250169 1680101.3365155349124.364385501
1680286.65077743349059.7027694281680479.25209826349004.254061416
#Sta/Elev= 30
       0 1302.14   103.2 1285.92   185.3 1255.58   243.9 1217.08   283.5 1204.03
   388.8 1143.18   426.7 1130.33   510.4 1086.09   543.2 1073.58   562.1 1060.15
   587.5 1049.06   664.9  997.73   700.8   997.6   714.2  995.14   732.1  997.74
   776.9 1001.61   806.7 1022.84   866.8 1028.72     925 1067.61   942.8 1069.61
  1022.6 1110.35    1091 1134.26  1121.1 1155.03  1141.9 1160.24  1175.2  1178.6
  1204.9 1199.75  1234.2 1210.97  1300.9 1247.05  1342.4 1259.41  1416.4  1301.3
#Mann= 5 ,-1,0
       0      .1       0   700.8    .045       0   732.1      .1       0
  858.33     .06       0  965.87      .1       0
Bank Sta=700.8,732.1
XS Rating Curve= 0 ,0
Exp/Cntr(USF)=0,0
Exp/Cntr=0.3,0.1

Type RM Length L Ch R = 1 ,100023  ,528.1,538.6,540.1
XS GIS Cut Line= 6
1679549.17882717350208.0003415941679964.06087142349781.512349427
1680012.50270367 349717.322845251680034.73625501349619.729536504
 1680198.8756905349405.1354774981680523.16506818349141.395191342
#Sta/Elev= 30
       0 1054.55    50.2 1059.22   111.5 1038.76   163.2 1034.72   197.1  1021.1
   208.4  1019.3   253.2    1017   287.2 1023.03   338.3 1011.91   713.3   990.3
   721.5  989.55   727.8   990.4   792.6  993.92   833.8 1019.89   856.8 1022.62
   876.7 1020.43   896.7 1025.54   913.8 1043.77   942.3  1067.3   979.3 1077.16
  1004.1 1097.14  1022.9 1101.74  1052.7 1121.93  1093.3 1133.73  1208.8 1197.81
  1241.5 1208.06  1314.1 1243.99  1358.5 1259.94  1417.3 1299.98  1464.7 1319.65
#Mann= 5 ,-1,0
       0      .1       0   713.3    .045       0   727.8      .1       0
  904.21     .06       0  977.23      .1       0
Bank Sta=713.3,727.8
XS Rating Curve= 0 ,0
Exp/Cntr(USF)=0,0
Exp/Cntr=0.3,0.1

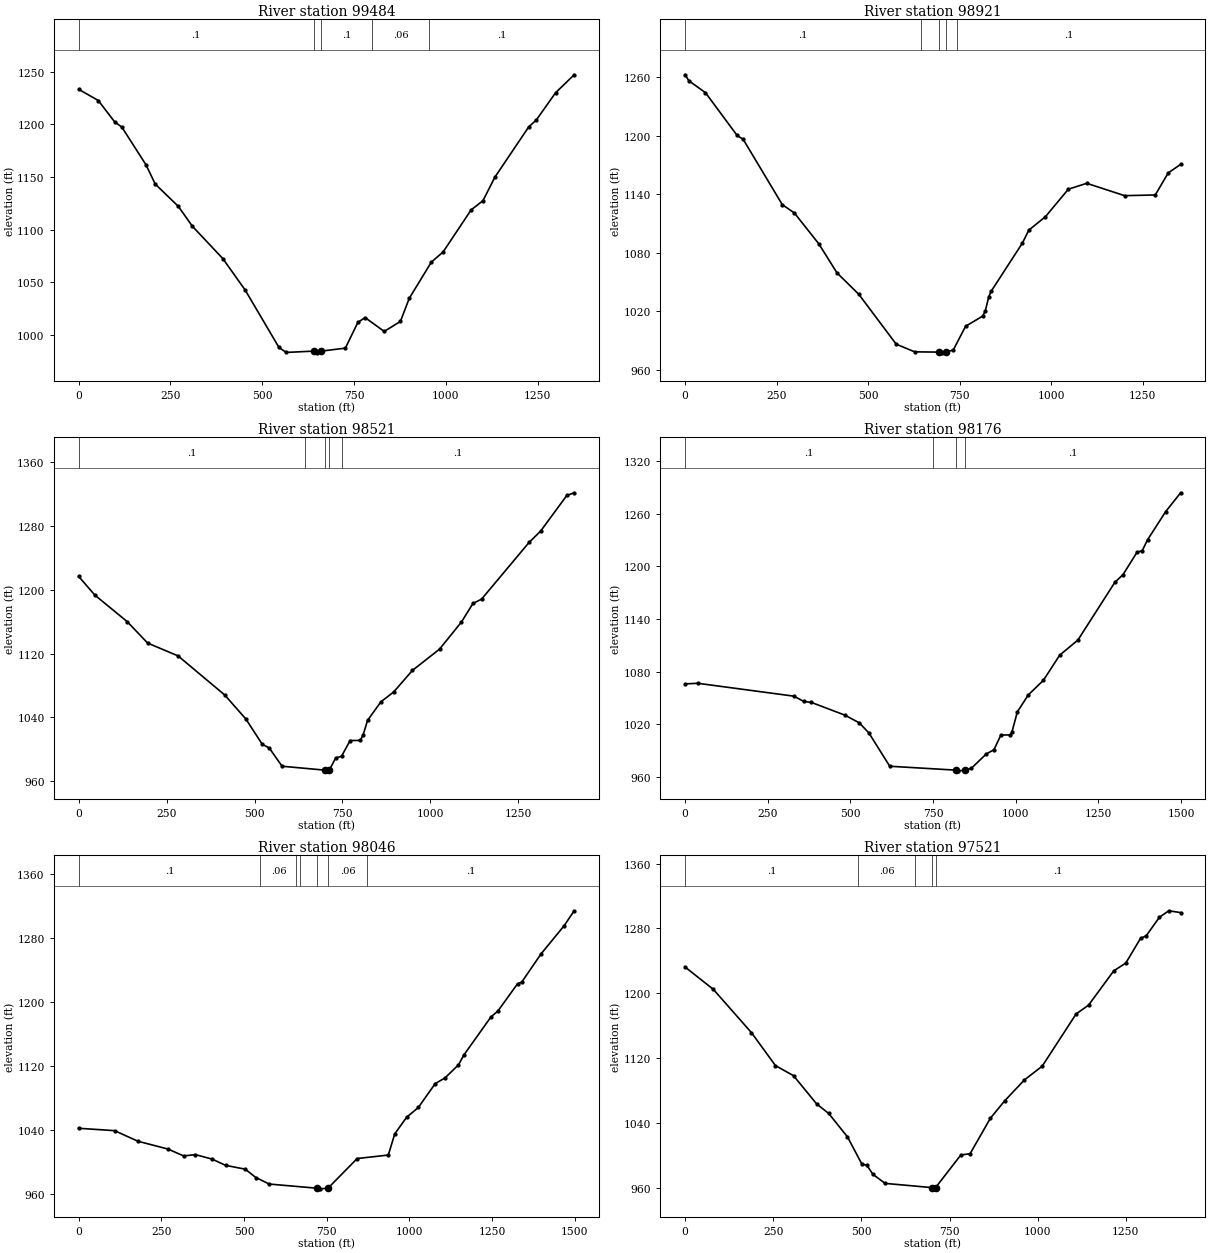
Type RM Length L Ch R = 1 ,99484   ,557.6,563.3,563.2
XS GIS Cut Line= 5
1679816.28495704350438.4817623941680139.69812744350173.762950929
1680464.58942135349945.9456693211680485.84231605349677.665428607
1680520.33027533349414.291057472
#Sta/Elev= 30
       0 1233.25    53.6 1222.56    97.9 1202.34   117.8 1197.25   183.2 1161.64
   208.8 1143.11   271.3  1122.1   309.9 1103.07   392.6 1072.45   453.6  1042.5
   545.5  988.06     565  983.29   640.2  984.53   648.9   982.9  660.24 984.514
   726.4  987.36   760.4 1011.76     780 1016.42   832.2 1003.24   876.3 1012.73
   900.4 1034.69   960.6  1069.1   992.7 1078.78  1068.9 1118.68  1101.2 1127.45
  1133.4 1149.68    1226 1197.64  1246.4 1204.04  1298.8 1229.91  1349.5 1247.01
#Mann= 5 ,-1,0
       0      .1       0   640.2    .045       0  660.24      .1       0
  797.94     .06       0  954.74      .1       0
Bank Sta=640.2,660.24
XS Rating Curve= 0 ,0
Exp/Cntr(USF)=0,0
Exp/Cntr=0.3,0.1

Type RM Length L Ch R = 1 ,98921   ,388.3,400,398.1
XS GIS Cut Line= 5
1679929.92415934 350642.70470121 1680390.4914203 350531.86242642
1680828.40945649350387.4188866281680912.69818492350365.277427282
1681223.98888054350251.434941019
#Sta/Elev= 30
       0 1262.24    10.5    1256    55.7 1243.89   142.1 1200.03   158.6  1196.1
   265.6 1129.08   298.5 1120.61   365.1 1089.02   414.8 1059.25   474.5 1037.21
   576.5  986.17   627.1  978.27   694.4  978.01   702.5  977.26   711.3  977.98
   732.4  980.18   766.1  1004.5   812.4 1014.83   819.7 1019.94   829.2 1034.54
   835.5 1040.13   921.1 1089.68   938.7 1102.99   984.2  1116.8  1046.6 1144.95
    1097 1151.01  1200.3 1138.35  1284.1 1139.05  1319.5 1161.66  1353.4 1170.42
#Mann= 5 ,-1,0
       0      .1       0  643.72     .06       0   694.4    .045       0
   711.3     .06       0  743.72      .1       0
Bank Sta=694.4,711.3
XS Rating Curve= 0 ,0
Exp/Cntr(USF)=0,0
Exp/Cntr=0.3,0.1

Type RM Length L Ch R = 1 ,98521   ,355.4,344.9,328.1
BEGIN DESCRIPTION:
Structure 31 XS 4
END DESCRIPTION:
XS GIS Cut Line= 6
1680024.10996392350955.2682040041680220.13188159350896.942205176
  1680588.266644350811.8068767491680916.04485984350731.089518502
1681102.38471025 350689.578774751681393.61936401 350628.11826776
#Sta/Elev= 30
       0 1216.65    46.1 1193.21     138 1160.02   196.2 1133.14   282.5 1117.15
   415.1 1068.23   475.4 1038.06   521.9 1006.49   541.8 1001.82   578.3  978.98
   701.6  974.02   705.8  973.22  712.39  974.02   730.5  989.31   747.2   991.4
   771.7 1011.15   800.6 1011.29   808.8 1018.37   821.2 1036.35   859.3  1059.7
   895.3 1071.84   948.7  1098.9  1025.9 1125.59  1088.1 1159.53  1120.8 1182.75
  1145.3 1188.16  1280.2 1259.09  1313.1 1273.31  1387.6 1317.95  1408.5  1321.3
#Mann= 5 ,-1,0
       0      .1       0  642.38     .06       0   701.6    .045       0
  712.39     .06       0  747.37      .1       0
Bank Sta=701.6,712.39
XS Rating Curve= 0 ,0
Exp/Cntr(USF)=0,0
Exp/Cntr=0.3,0.1

Type RM Length L Ch R = 1 ,98176   ,136.8,129.9,133.1
BEGIN DESCRIPTION:
Structure 31 XS 3
END DESCRIPTION:
XS GIS Cut Line= 6
1680206.26375606 351592.439794381680782.22155433351272.295206127
 1680801.5849059 351225.500439841680809.65296905351123.842844114
1680808.03935642351001.2082841911681351.77036808350849.232830062
#Sta/Elev= 30
       0 1066.22    38.7 1066.89   329.1 1052.22   359.1 1046.21     382 1045.09
   482.6 1030.73   526.7 1021.89   555.9 1010.32     619   972.4   820.3  967.92
   826.9  967.16   846.9  967.81   866.1  970.18   910.9  986.36   934.2  991.24
   955.1 1007.92   984.1 1008.13   988.3 1010.98  1004.9 1034.36  1038.1 1053.71
  1083.8 1070.32  1132.8 1098.87    1188 1116.12  1299.8 1181.88  1324.7 1190.76
  1366.5 1216.01  1382.9 1218.17    1399 1230.53  1453.5 1262.45  1498.8 1283.93
#Mann= 4 ,-1,0
       0      .1       0   749.6     .06       0   820.3    .045       0
   846.9      .1       0
Bank Sta=820.3,846.9
XS Rating Curve= 0 ,0
Exp/Cntr(USF)=0,0
Exp/Cntr=0.3,0.1

Type RM Length L Ch R = 1 ,98046   ,508.9,525.3,534.9
BEGIN DESCRIPTION:
Structure 31 XS 2
END DESCRIPTION:
XS GIS Cut Line= 6
1680267.60376902351620.0479193721680843.56156729351299.903331119
1680862.92491886351253.1085648321680870.99298201351151.450969106
1680869.37936938351028.8164091831681413.11038104350876.840955054
#Sta/Elev= 30
       0 1041.86   108.8 1038.88   179.4 1025.64   270.6 1015.82   317.7 1007.24
     353 1008.92   403.3 1003.37   444.5  995.48     504  990.68     536  980.26
   576.5  972.08   722.2  966.84   730.7   966.1   754.3  966.95   842.5 1004.01
   936.7 1008.37   956.1 1034.85   991.8 1055.49  1027.6 1067.93  1078.3 1097.63
  1108.7 1105.03  1148.9 1121.23  1165.5 1133.72  1247.3 1181.26  1267.8 1188.38
  1327.5  1222.6  1339.9 1224.54  1398.9 1260.14  1468.7 1295.37  1498.8 1313.93
#Mann= 7 ,-1,0
       0      .1       0     550     .06       0  658.95     .05       0
  668.95     .06       0   722.2    .045       0   754.3     .06       0
  871.57      .1       0
Bank Sta=722.2,754.3
XS Rating Curve= 0 ,0
Exp/Cntr(USF)=0,0
Exp/Cntr=0.3,0.1

Type RM Length L Ch R = 1 ,97521   ,498.3,499.8,497
BEGIN DESCRIPTION:
Structure 31 XS 1
END DESCRIPTION:
XS GIS Cut Line= 6
1680593.59340501352085.906690761  1681108.167179351683.164386004
1681254.37915692351586.9854445011681324.20742933 351533.91173175
1681470.89972125351411.082909167 1681693.2312976351212.639736503
#Sta/Elev= 30
       0 1232.43      80 1204.94   187.9 1151.72   256.3 1110.95   307.6 1098.47
   373.1 1063.67   407.3 1051.94   460.6 1023.01   501.4  989.51   515.6  988.06
   532.7   976.9   567.3  965.72  699.49  960.55   705.8     959  710.42  960.55
     782  1000.7   808.4 1002.34   865.7  1045.9     906 1067.29   962.6 1093.36
  1012.8 1110.17  1109.1 1174.63  1144.2 1185.39  1215.8 1227.73    1250 1237.33
  1291.8 1267.85  1307.4  1270.7  1345.3 1293.78  1371.8 1301.78  1405.5 1299.53
#Mann= 5 ,-1,0
       0      .1       0  489.72     .06       0  653.44      .1       0
  699.49    .045       0  710.42      .1       0
Bank Sta=699.49,710.42
XS Rating Curve= 0 ,0
Exp/Cntr(USF)=0,0
Exp/Cntr=0.3,0.1

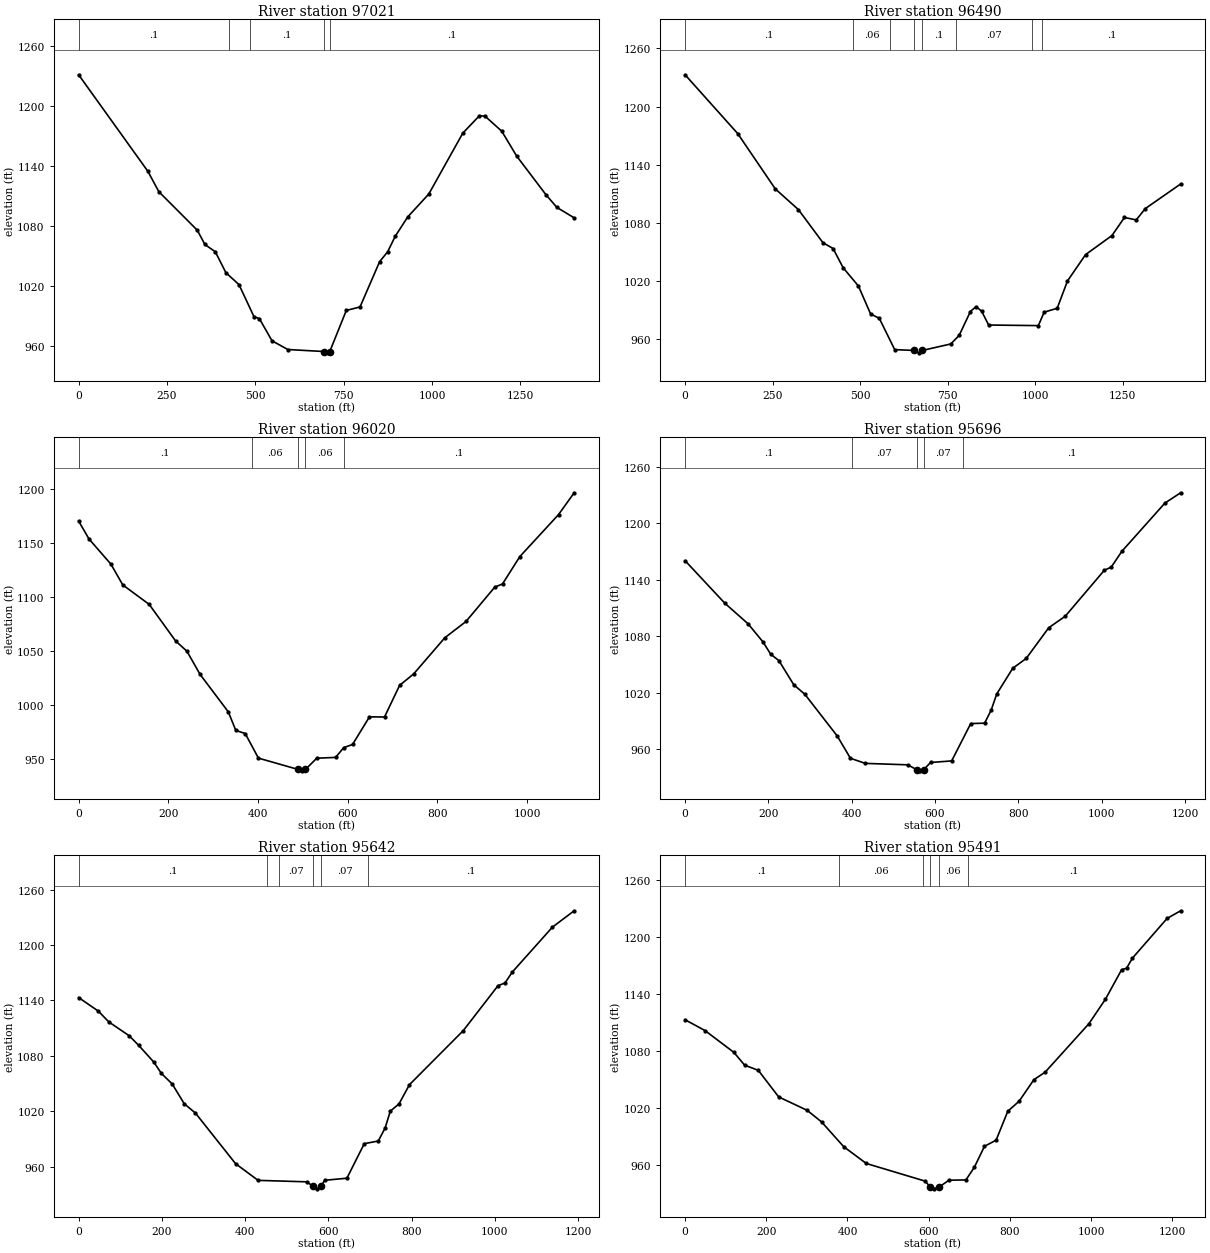
Type RM Length L Ch R = 1 ,97021   ,522.5,530.7,536.1
XS GIS Cut Line= 6
1680983.34131317352464.7687939261681123.96931276352323.416714415
 1681267.8459935352190.9898139241681338.54729567352129.312443838
1681601.07629818351917.1944297551682039.83624743351544.519978255
#Sta/Elev= 30
       0 1231.58   195.9 1134.99   226.9 1114.59   335.9 1075.98   357.2 1061.76
   386.7 1054.45   416.7 1033.49   453.7 1021.59   495.9  989.64   511.4  987.55
   547.1  965.39   591.8  956.66   694.6  954.64   706.1  953.33  710.57  954.65
   757.3  995.76   796.1  999.24   851.6 1044.57   874.3 1054.46   895.6 1069.91
   931.1 1089.35   990.7 1112.26  1086.9 1173.16  1134.1 1190.68  1149.9 1190.12
  1197.1 1175.15  1239.1 1150.34  1322.2 1111.55  1352.9 1098.91    1402 1088.42
#Mann= 5 ,-1,0
       0      .1       0  424.94     .06       0  484.94      .1       0
   694.6    .045       0  710.57      .1       0
Bank Sta=694.6,710.57
XS Rating Curve= 0 ,0
Exp/Cntr(USF)=0,0
Exp/Cntr=0.3,0.1

Type RM Length L Ch R = 1 ,96490   ,465.3,469.8,472.5
XS GIS Cut Line= 5
 1681066.3480164352564.1378033531681604.34102363352428.005391764
 1681959.6255991352410.291022524 1682295.4614203352646.712646397
1682374.39468937 352698.23538619
#Sta/Elev= 30
       0 1232.76   150.4 1172.01   257.6 1114.97   323.7 1093.55   393.8 1059.37
   422.7 1053.39   451.6 1033.45   495.1 1014.69     530  985.74   554.7  981.32
   598.8  948.98   654.8  948.13   666.9  945.66  677.36948.1039     759  954.84
   782.9  963.66     815  988.28   831.1  993.44   847.1  988.67   867.1  974.39
  1009.1  973.76  1025.8  987.68  1062.9  991.63  1092.3 1019.84  1143.9 1047.02
  1219.5  1066.8  1255.1 1085.44  1288.7 1082.89  1314.5 1094.56  1415.6 1120.01
#Mann= 8 ,-1,0
       0      .1       0     480     .06       0  584.95      .1       0
   654.8    .045       0  677.36      .1       0  774.95     .07       0
  990.68     .06       0 1020.68      .1       0
Bank Sta=654.8,677.36
XS Rating Curve= 0 ,0
Exp/Cntr(USF)=0,0
Exp/Cntr=0.3,0.1

Type RM Length L Ch R = 1 ,96020   ,324.6,324.4,324.1
BEGIN DESCRIPTION:
Structure 30 XS 4
END DESCRIPTION:
XS GIS Cut Line= 6
1681166.09750934352719.9313413351681846.54693584352936.435173422
1681935.83940817352965.8137235941682027.27656126 352999.88419351
1682119.72125825353036.211548671 1682212.5015845353073.630437091
#Sta/Elev= 30
       0 1170.28    23.1 1153.75    72.1 1130.39    98.4 1111.24   157.4 1093.19
   216.2 1059.39   241.4 1049.91   270.8 1028.44   333.7   993.8   350.5   976.6
   371.5  973.72   400.9  950.97     489  940.54   497.4   939.2   505.8  940.49
     531   950.9     573  951.63   591.2  960.72   610.8  963.59   648.5  989.13
   682.1  989.01   715.7 1018.27   747.1 1028.87   816.6 1062.34   863.8  1077.4
     928 1109.22   945.2 1112.11   983.8 1137.43  1070.1 1176.28    1105 1196.48
#Mann= 5 ,-1,0
       0      .1       0  386.56     .06       0     489    .045       0
   505.8     .06       0  591.56      .1       0
Bank Sta=489,505.8
XS Rating Curve= 0 ,0
Exp/Cntr(USF)=0,0
Exp/Cntr=0.3,0.1

Type RM Length L Ch R = 1 ,95696   ,54.5,54.6,54.6
BEGIN DESCRIPTION:
Structure 30 XS 3
END DESCRIPTION:
XS GIS Cut Line= 6
1681082.51322091352873.5499765831681457.08053561353071.984762636
1681462.03143399353113.2694370821681475.53460043353145.339457375
1681504.22882912353166.7194709031682132.53174888353346.562084248
#Sta/Elev= 30
       0 1160.25    95.1 1115.22   151.3 1093.19   186.9 1074.05   205.5 1060.96
   225.3 1054.12   260.8 1028.58   287.5  1018.4   365.3  974.09   396.9  950.48
   432.5  945.05   534.4  943.52556.4194938.2982     565  937.13573.1194938.4488
   589.2  946.01   639.9  947.66   685.7  987.32     719  987.75   734.7  1001.5
   748.1 1018.74   786.5 1045.99   818.8 1056.43   872.9 1089.03   912.7 1101.35
  1006.5 1150.13  1022.9  1153.4  1048.5  1170.2  1151.7 1221.37  1189.6 1232.36
#Mann= 5 ,-1,0
       0      .1       0     400     .07       0556.4194    .045       0
573.1194     .07       0  666.04      .1       0
Bank Sta=556.4194,573.1194
XS Rating Curve= 0 ,0
Exp/Cntr(USF)=0,0
Exp/Cntr=0.3,0.1

Type RM Length L Ch R = 1 ,95642   ,149.7,150.1,149.3
BEGIN DESCRIPTION:
Structure 30 XS 2
END DESCRIPTION:
XS GIS Cut Line= 6
1681073.86297026 352905.665097211681395.26101785353082.451678196
1681399.27940751353126.7931844791681425.86314472353179.960658899
1681479.88815905353215.9773351191682107.43110796353402.142074856
#Sta/Elev= 30
       0 1143.04    47.5 1128.32    72.4  1116.7   121.3 1101.74   144.1 1091.39
   180.6 1073.17   198.9 1060.87   224.7 1049.55   253.7 1028.11   280.6 1017.99
   376.9  963.27   431.1  945.16   548.5  943.57 562.105938.9279   573.5  935.99
582.0044938.8108     591  945.25   644.4  947.49   686.1  984.89   719.8  987.76
   736.2 1001.86   748.7  1020.1   769.6 1027.96   794.6 1048.72     924  1107.3
  1007.4 1155.89  1024.1 1158.84  1041.5 1170.56  1138.1 1219.28  1190.3 1236.98
#Mann= 6 ,-1,0
       0      .1       0  451.33     .06       0  480.78     .07       0
 562.105    .045       0582.0044     .07       0  695.71      .1       0
Bank Sta=562.105,582.0044
XS Rating Curve= 0 ,0
Exp/Cntr(USF)=0,0
Exp/Cntr=0.3,0.1

Type RM Length L Ch R = 1 ,95491   ,106.4,106.7,106.6
BEGIN DESCRIPTION:
Structure 30 XS 1
END DESCRIPTION:
XS GIS Cut Line= 4
1680918.73647011353079.4195487421681286.28156929353314.289831636
1681612.58990125353407.5207836251682057.22982612353432.621424545
#Sta/Elev= 30
       0 1113.03    49.1 1101.67   120.3 1078.72   146.6 1065.34   180.4 1059.85
   230.6 1031.91   300.7 1017.85   336.4 1005.58   390.9  979.56   446.4  961.96
     592  943.33  603.76937.1303   612.8   935.3   625.3  937.05   650.2  944.39
   691.9  944.66   712.7  958.04   737.6  980.01   766.3  986.48     795  1016.8
   823.1 1027.49   859.2 1049.97   887.2 1058.01   994.8 1108.83  1035.5 1134.55
  1075.5 1165.64  1087.6 1167.17  1102.2 1177.86  1187.7  1219.6  1220.9 1227.59
#Mann= 6 ,-1,0
       0      .1       0     380     .06       0  586.18      .1       0
  603.76    .045       0   625.3     .06       0  696.18      .1       0
Bank Sta=603.76,625.3
XS Rating Curve= 0 ,0
Exp/Cntr(USF)=0,0
Exp/Cntr=0.3,0.1

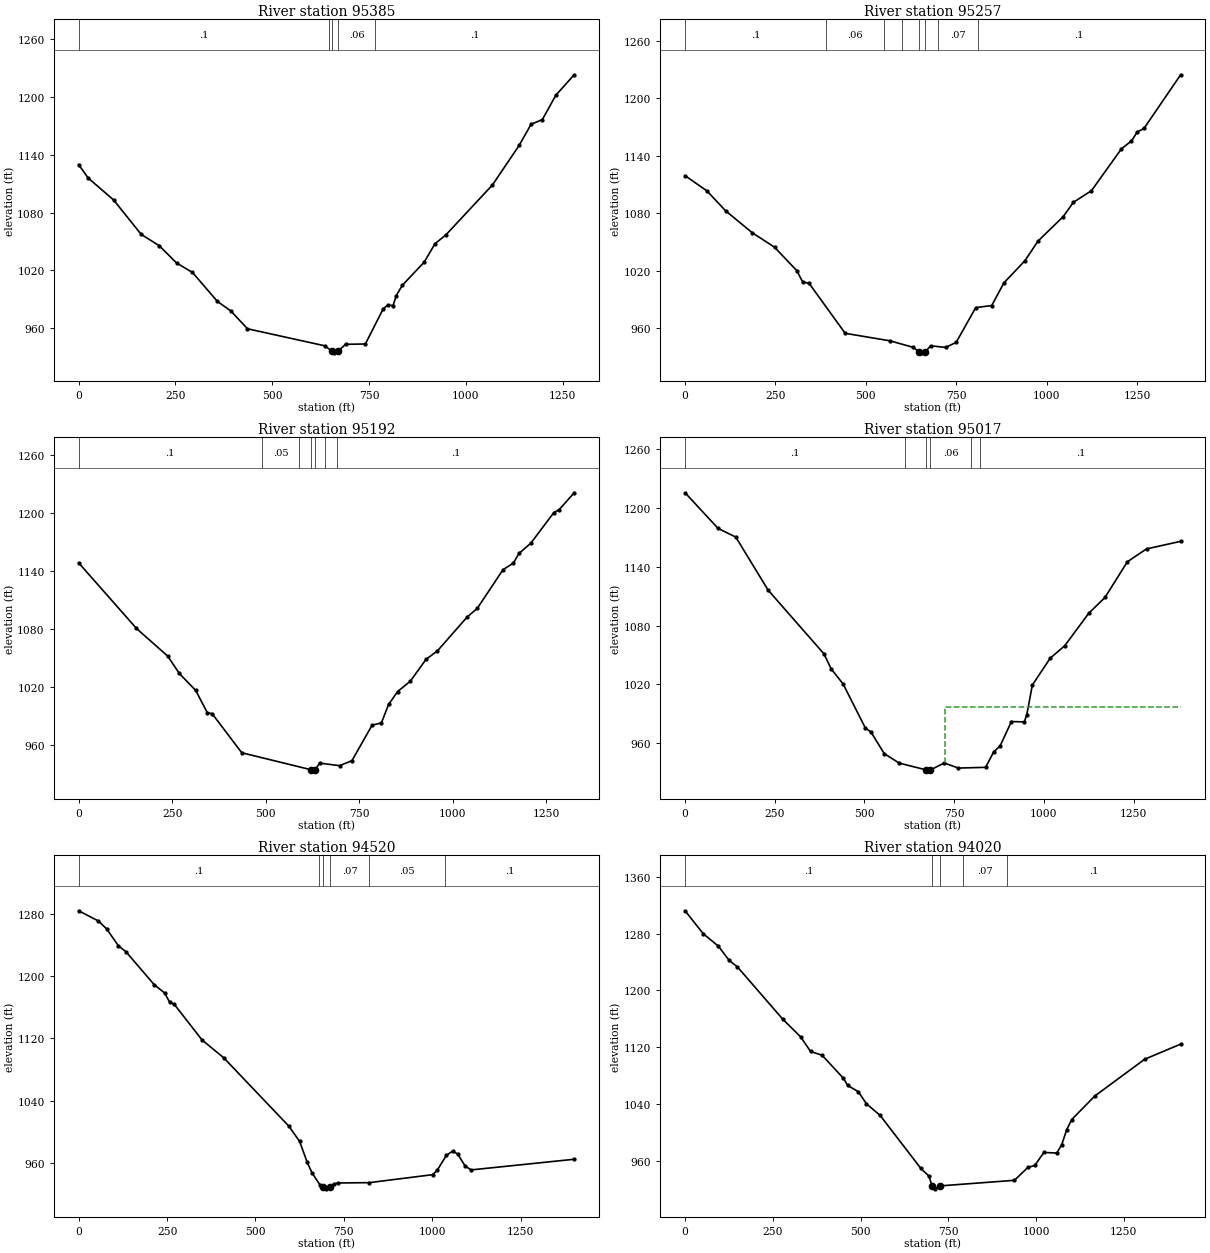
Type RM Length L Ch R = 1 ,95385   ,128.4,128.1,127.8
BEGIN DESCRIPTION:
Structure 29 XS 4
END DESCRIPTION:
XS GIS Cut Line= 4
1680868.53518827353129.6208305821681214.56545238353394.970463165
1681578.52474572353513.3020560731682039.30079689 353498.95883269
#Sta/Elev= 30
       0 1129.81    24.6 1115.84    90.2 1093.11   161.5 1057.32   208.6 1045.39
   252.8  1027.6     294 1017.74   358.4  987.62   392.6  977.88   436.1  959.21
   635.4  941.53   654.4  935.93   660.6   934.2  670.49936.0026   689.3  943.07
   740.5   943.4   786.8  980.06   799.4  984.18     812  983.17   820.4  993.73
   836.1 1004.45   892.4 1028.42   920.4 1047.58   948.4 1056.72  1068.5 1108.53
  1137.7 1149.71  1168.5 1171.69  1197.5 1176.52  1232.6 1201.93  1279.8 1223.11
#Mann= 5 ,-1,0
       0      .1       0  646.06     .05       0   654.4    .045       0
  670.49     .06       0  766.06      .1       0
Bank Sta=654.4,670.49
XS Rating Curve= 0 ,0
Exp/Cntr(USF)=0,0
Exp/Cntr=0.3,0.1

Type RM Length L Ch R = 1 ,95257   ,65,64.9,64.7
BEGIN DESCRIPTION:
Structure 29 XS 3
END DESCRIPTION:
XS GIS Cut Line= 5
1680795.02616843353739.2078243531681178.70739392353529.438182379
1681248.63060791353545.5743086851681555.21700772353633.426551904
1681998.06402967353947.184563404
#Sta/Elev= 30
       0 1119.35    60.5 1103.42   111.8 1082.76   185.5 1059.85   247.4 1044.67
   309.3 1020.06   324.9 1008.66   343.1  1006.9   442.8   954.8   566.8  946.97
   630.7   940.2   646.9  935.39   653.3  934.43  664.61 935.413   679.1  941.77
   720.7   940.1   749.8  945.35   803.9  981.65   848.1  983.78   881.8 1007.43
   939.9 1030.54   976.1 1051.03    1046 1076.67  1074.2  1091.6    1124 1103.65
    1207  1147.4  1234.7 1155.61  1250.7 1164.91  1269.3 1168.63  1370.7 1224.65
#Mann= 8 ,-1,0
       0      .1       0     390     .06       0  549.04     .05       0
  599.04     .06       0   646.9    .045       0  664.61     .06       0
  699.04     .07       0  809.04      .1       0
Bank Sta=646.9,664.61
XS Rating Curve= 0 ,0
Exp/Cntr(USF)=0,0
Exp/Cntr=0.3,0.1

Type RM Length L Ch R = 1 ,95192   ,173.4,174.2,174.7
BEGIN DESCRIPTION:
Structure 29 XS 2
END DESCRIPTION:
XS GIS Cut Line= 4
1680791.44036258353789.409106193  1681200.222229353602.947202216
1681548.04539603353694.3852512821681974.75629167353983.042621861
#Sta/Elev= 30
       0 1148.46   154.6 1080.44   238.2  1051.7   268.9 1033.85   312.9 1016.14
   343.7  993.21   356.9  992.02   435.9  951.59  619.63934.1054     627  932.85
  632.76934.0844   643.7  940.88   697.3  938.21   730.4  943.46   784.2  980.21
     809  982.52   828.3  1001.7   852.5 1015.08   886.3 1025.79   928.6 1048.55
   958.7 1057.19  1038.1 1092.31    1065 1101.16    1134 1141.37  1161.6 1148.18
  1176.9 1158.32  1208.1 1168.77  1269.7 1200.51    1284  1203.6  1324.1 1221.09
#Mann= 7 ,-1,0
       0      .1       0   489.3     .05       0   589.3     .06       0
  619.63    .045       0  632.76     .06       0   659.3     .07       0
   689.3      .1       0
Bank Sta=619.63,632.76
XS Rating Curve= 0 ,0
Exp/Cntr(USF)=0,0
Exp/Cntr=0.3,0.1

Type RM Length L Ch R = 1 ,95017   ,496,497.6,496.6
BEGIN DESCRIPTION:
Structure 29 XS 1
END DESCRIPTION:
XS GIS Cut Line= 6
1680642.03500381353876.5906544921681182.29319977353758.929756504
 1681344.1214315353821.8428514151681491.53747526353894.287916511
1681839.33566417354070.8476027551681931.81251334354109.746475086
#Sta/Elev= 30
       0 1215.68    92.2  1179.2   141.3 1170.44   231.4 1116.24   386.9 1051.26
   407.4 1035.67   440.2 1020.53   502.7  975.23   517.9  971.43   554.9  949.36
   596.9  939.55  672.14932.6469   675.9  931.68   683.8  932.64   722.4  939.69
   761.6  934.52   837.7  935.26   860.1  951.06   878.1  957.14   909.5  982.04
   945.4   981.6   952.4  988.98   967.9 1019.29  1017.7 1046.77  1057.9 1059.33
  1125.3  1092.7  1170.3 1108.74  1232.7 1145.24  1286.1 1158.36  1381.2 1166.08
#Mann= 6 ,-1,0
       0      .1       0  612.92     .06       0  672.14    .045       0
   683.8     .06       0  796.56     .07       0  822.53      .1       0
#XS Ineff= 2 , 0
                          723.65          996.55
Permanent Ineff=
       F       F
Bank Sta=672.14,683.8
XS Rating Curve= 0 ,0
Exp/Cntr(USF)=0,0
Exp/Cntr=0.3,0.1

Type RM Length L Ch R = 1 ,94520   ,496,500,505.9
XS GIS Cut Line= 6
 1680489.2255035 353970.693603591681323.44561984354341.430723011
1681409.55863659 354378.50873284  1681498.745138354416.366596758
1681589.46772559354454.6148798321681772.83382867354531.598321676
#Sta/Elev= 30
       0 1283.55    55.7 1270.56    79.3 1260.32   112.6 1238.62   133.9 1231.04
   213.3 1189.08     243  1178.3     257 1166.72   270.3 1163.81     349 1118.04
   410.2 1095.29   594.1  1007.8   624.7  988.23     646   961.6   659.8  947.87
   681.6  932.99  692.24929.3317   700.6  927.44   711.2  929.29     721  933.79
   734.2  934.94   821.8  935.38  1000.7  945.57  1013.8  951.28  1039.8  970.45
  1057.2  975.62  1071.2  972.27  1092.5  956.79  1109.4  951.68  1400.9  965.32
#Mann= 6 ,-1,0
       0      .1       0  680.39     .06       0  692.24    .045       0
   711.2     .07       0  820.39     .05       0 1036.65      .1       0
Bank Sta=692.24,711.2
XS Rating Curve= 0 ,0
Exp/Cntr(USF)=0,0
Exp/Cntr=0.3,0.1

Type RM Length L Ch R = 1 ,94020   ,501.7,506.9,517.2
XS GIS Cut Line= 6
1680358.44131626 354185.324407921680583.97728251354387.577284262
1680726.65055358354520.1534626781680790.04314335354581.934835166
1680839.10374075354638.733278006 1681307.8678951355224.690439418
#Sta/Elev= 30
       0 1312.24    51.6 1279.92    94.9 1262.35   125.6 1242.24   148.9 1233.22
   278.2 1159.43   329.2 1134.51   357.5  1113.9   390.1  1108.7   450.9 1076.19
   463.2 1066.04   493.4 1057.24   516.5 1040.23   555.6  1023.8   671.8  948.97
   694.6  938.28  703.52924.5923   711.7   920.3   725.1  924.41   938.2  932.32
   976.3  950.38   995.9  953.22  1022.2  971.57  1058.9  970.78  1073.1  982.79
  1087.3 1003.89  1101.5    1018    1167  1051.1  1309.6 1103.08  1411.7 1124.27
#Mann= 5 ,-1,0
       0      .1       0  703.52    .045       0   725.1      .1       0
  791.28     .07       0  916.28      .1       0
Bank Sta=703.52,725.1
XS Rating Curve= 0 ,0
Exp/Cntr(USF)=0,0
Exp/Cntr=0.3,0.1