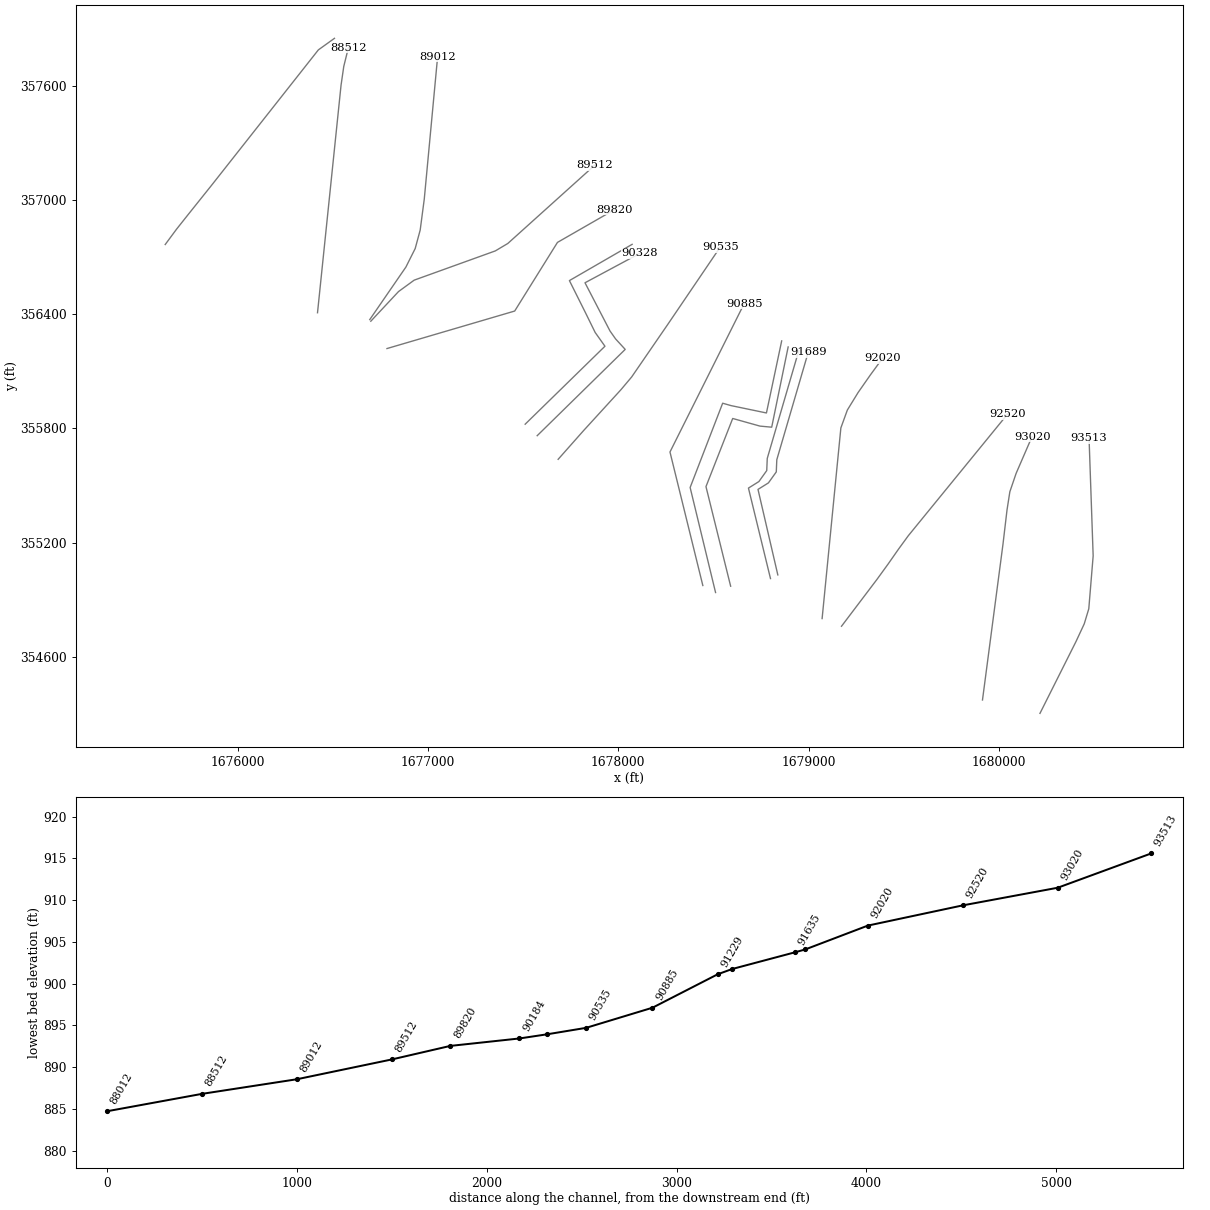
HEC-RAS study SFFSHGCK.prj: SFFSHGCK

--- SFFSHGCK.g01 (geometry) --- (continued)

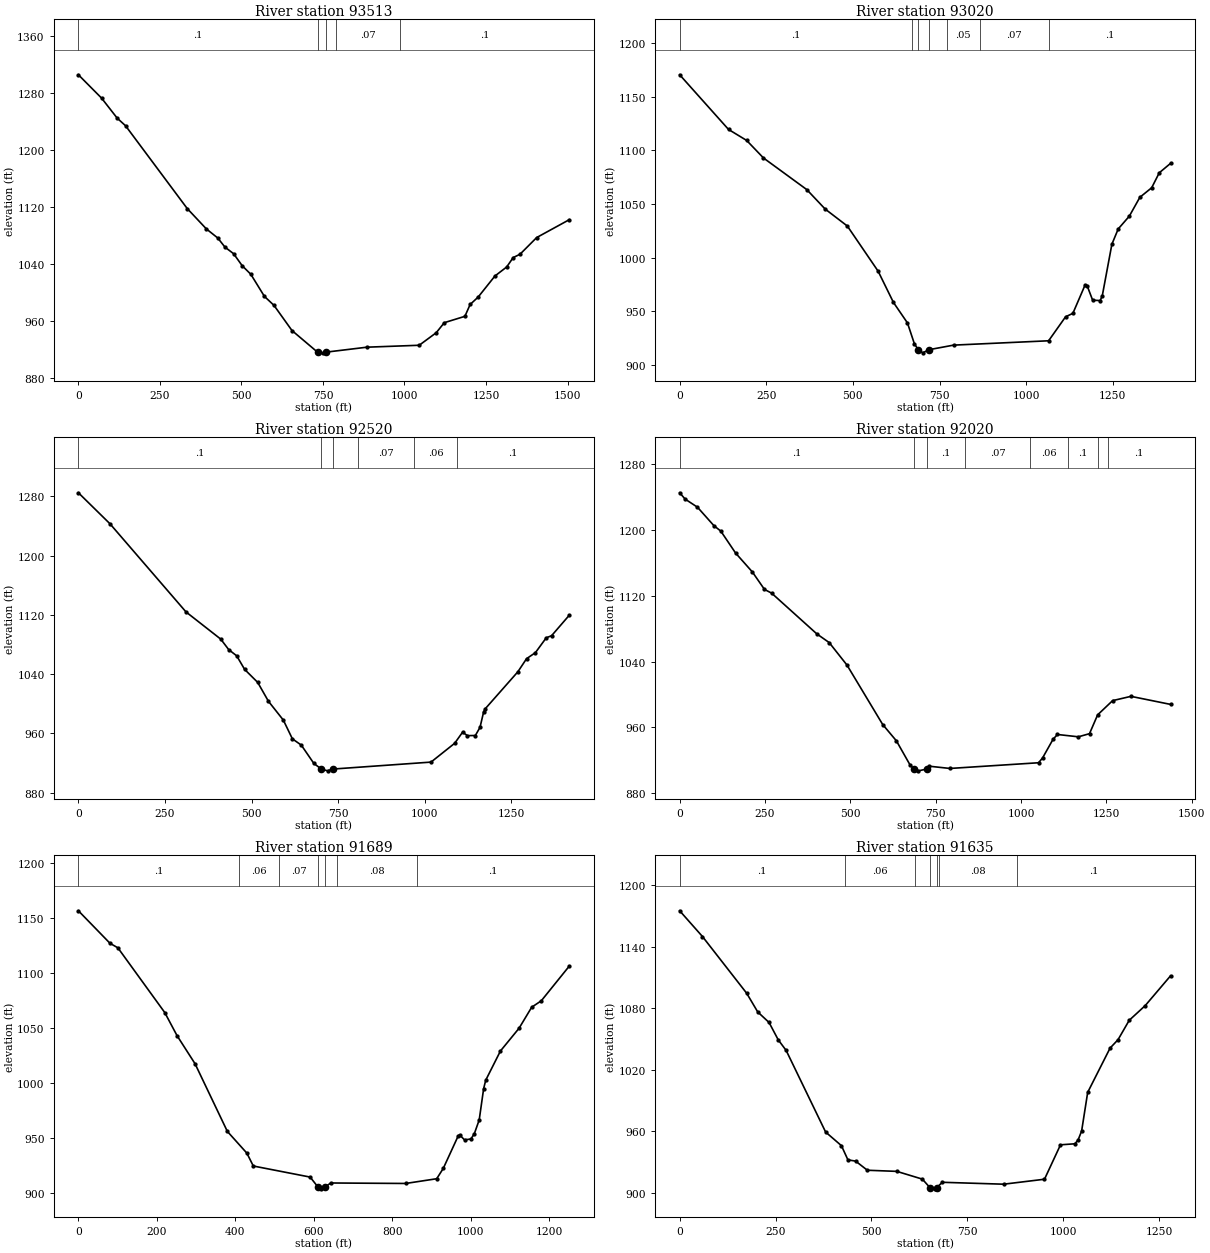
Type RM Length L Ch R = 1 ,93513   ,492.9,493.1,492.1
XS GIS Cut Line= 6
1680216.00459325354302.3661685881680405.32704926354679.862132758
1680448.59697583354772.7228394151680472.55073148354852.053223522
1680495.50879332355129.9460795661680473.95853705355748.240470701
#Sta/Elev= 30
       0 1305.68    71.1 1272.94     119 1244.82   144.6 1234.18   333.8 1117.98
   392.5 1089.42   427.5 1076.67   449.5 1063.87     476 1054.65   502.5 1037.71
   528.7 1025.84   570.5  994.77   599.8  982.19     655  946.87733.3608916.5518
   748.8  915.59760.2936916.6083   885.1  923.53  1045.2  926.22  1097.3  943.79
  1122.1   957.9  1185.3  966.82  1201.3  983.43  1225.8  993.77  1277.4 1023.38
  1313.4 1036.04  1333.4 1049.25  1354.3 1053.91  1405.4 1077.33  1505.2 1102.34
#Mann= 5 ,-1,0
       0      .1       0733.3608    .045       0760.2936      .1       0
  790.04     .07       0  986.54      .1       0
Bank Sta=733.3608,760.2936
XS Rating Curve= 0 ,0
Exp/Cntr(USF)=0,0
Exp/Cntr=0.3,0.1

Type RM Length L Ch R = 1 ,93020   ,506.2,500,489.7
XS GIS Cut Line= 6
1679913.91595858354372.7751485111680021.59422092355191.111766428
1680042.82088451 355371.131419511680057.74867618355467.095138341
1680090.60523775355563.412531003 1680174.5056605355757.084059671
#Sta/Elev= 30
       0 1170.23     141 1119.36   193.4 1109.11   241.8 1092.82   366.9 1063.37
   419.9 1045.28   483.9 1029.48   572.7  987.49     617  958.37   657.4  939.32
   677.6  919.73  689.04914.2649   701.8  911.48   718.4  914.33   790.5  918.66
  1064.8   922.7  1113.8  945.03  1134.9  948.25  1169.8  974.41  1176.1  973.84
  1191.9  960.46  1213.7  960.12  1219.8  964.72  1247.4 1012.52  1265.7 1026.79
  1297.7 1038.64  1328.2 1056.23  1362.3  1065.1  1384.2 1079.04  1416.6 1087.75
#Mann= 7 ,-1,0
       0      .1       0  670.39     .07       0  689.04    .045       0
   718.4     .07       0  770.39     .05       0  865.39     .07       0
 1066.66      .1       0
Bank Sta=689.04,718.4
XS Rating Curve= 0 ,0
Exp/Cntr(USF)=0,0
Exp/Cntr=0.3,0.1

Type RM Length L Ch R = 1 ,92520   ,491.3,500,511.4
XS GIS Cut Line= 6
1679173.07885759 354760.270436511679358.49220067355005.166600257
1679417.54720068355086.5581697521679472.72425568355165.509455428
1679524.39541218355236.3062298451680046.30184868355875.716040254
#Sta/Elev= 30
       0 1284.82    91.1 1242.99   310.7 1123.93     411 1087.22     434 1073.04
     457 1064.68   479.9 1046.37   517.7 1028.79   548.7 1003.28   591.7  977.88
   617.8  952.58   643.6  944.08   679.9  919.31  701.78911.6951   719.6  909.37
   733.8  911.74  1018.1  921.17  1086.4  946.58  1109.1  961.48  1123.4   956.9
  1146.1  957.08  1159.6  968.15  1169.9  988.82    1175  993.38  1268.8 1043.11
  1293.9 1060.79  1319.5 1068.96  1350.8 1089.03  1366.2 1091.85  1417.1 1119.39
#Mann= 6 ,-1,0
       0      .1       0  701.78    .045       0   733.8      .1       0
   806.7     .07       0   969.2     .06       0 1092.95      .1       0
Bank Sta=701.78,733.8
XS Rating Curve= 0 ,0
Exp/Cntr(USF)=0,0
Exp/Cntr=0.3,0.1

Type RM Length L Ch R = 1 ,92020   ,331.5,330.5,328.6
BEGIN DESCRIPTION:
Structure 28 XS 4
END DESCRIPTION:
XS GIS Cut Line= 6
1679071.16862834354800.5715370031679169.71141025355802.376948088
1679203.75038417355896.2678364221679260.13511392355988.231891334
1679324.02671842356079.7684536731679390.03806934356170.210858092
#Sta/Elev= 30
       0 1245.46      16 1237.77    52.2 1227.87   100.4 1205.37   120.5  1198.8
   163.8  1172.1     213 1149.04   248.5 1127.78   269.3 1123.31   401.9 1073.64
   438.1 1063.08   490.3 1035.63   594.8  963.35     635  943.44   675.2  913.94
   687.3  909.11   699.3  906.95  725.22909.2441   731.5  912.57   791.8  909.86
  1051.5   916.8  1063.3  922.72    1094  945.43  1106.8  951.21  1168.1  948.38
  1200.7   952.2  1224.5  975.09  1268.4  992.42  1322.1  997.63    1438  987.85
#Mann= 8 ,-1,0
       0      .1       0   687.3    .045       0  725.22      .1       0
  835.39     .07       0 1026.64     .06       0 1136.51      .1       0
 1224.38     .05       0 1254.38      .1       0
Bank Sta=687.3,725.22
XS Rating Curve= 0 ,0
Exp/Cntr(USF)=0,0
Exp/Cntr=0.3,0.1

Type RM Length L Ch R = 1 ,91689   ,53.5,54,53.8
BEGIN DESCRIPTION:
Structure 28 XS 3
END DESCRIPTION:
XS GIS Cut Line= 6
1678838.40747467355030.0099919141678734.25759776355479.289593404
1678789.01317585355513.522135251 1678830.3243336355571.264660391
1678833.04619539355635.1903490421678998.51153082356200.855570929
#Sta/Elev= 30
       0 1156.72    80.6 1127.17   100.7 1123.06   220.2 1064.27   251.5 1043.29
   297.4 1017.77   379.8  956.27   429.6  936.51     446  924.83   590.9  914.77
   611.4   905.5   619.5  904.09     628  905.58   643.5  909.41   834.4  908.97
   913.6  913.27   930.3  922.62   967.8  951.69   971.9  953.13   984.5   948.6
  1000.8  949.36  1009.5  954.14    1022  966.72  1033.3  995.17  1038.6 1002.78
  1076.1 1029.32  1123.6    1050  1155.8  1069.1  1180.3 1074.94  1251.5 1106.39
#Mann= 7 ,-1,0
       0      .1       0     410     .06       0  511.19     .07       0
   611.4    .045       0     628     .07       0  658.16     .08       0
  862.14      .1       0
Bank Sta=611.4,628
XS Rating Curve= 0 ,0
Exp/Cntr(USF)=0,0
Exp/Cntr=0.3,0.1

Type RM Length L Ch R = 1 ,91635   ,341.5,330.9,312.6
BEGIN DESCRIPTION:
Structure 28 XS 2
END DESCRIPTION:
XS GIS Cut Line= 6
1678799.87527398355010.8206583041678684.10738613355486.240784409
1678738.86296423355520.4733262561678780.17412197355578.215851396
1678782.89598376355642.1415400471678948.36131919356207.806761933
#Sta/Elev= 30
       0 1175.05    59.4 1149.93   174.7 1094.58   203.5 1076.34     233 1066.09
     257  1049.1   277.6 1038.79   380.5  959.16   421.7  945.87   438.6  932.02
   458.7   930.8   489.3  921.89   566.1  920.79   632.6  913.24   652.6   904.9
   664.6  903.75  669.94904.9163   684.7  910.14   844.7  908.28   951.1  913.13
   992.8   946.7  1030.3  947.71  1038.7  951.41  1047.9  960.17  1063.7  997.88
    1122 1041.03  1142.9 1049.32    1172  1068.2  1213.7 1082.54  1279.6 1111.53
#Mann= 7 ,-1,0
       0      .1       0     430     .06       0  614.14     .07       0
   652.6    .045       0  669.94     .07       0  676.28     .08       0
  880.26      .1       0
Bank Sta=652.6,669.94
XS Rating Curve= 0 ,0
Exp/Cntr(USF)=0,0
Exp/Cntr=0.3,0.1

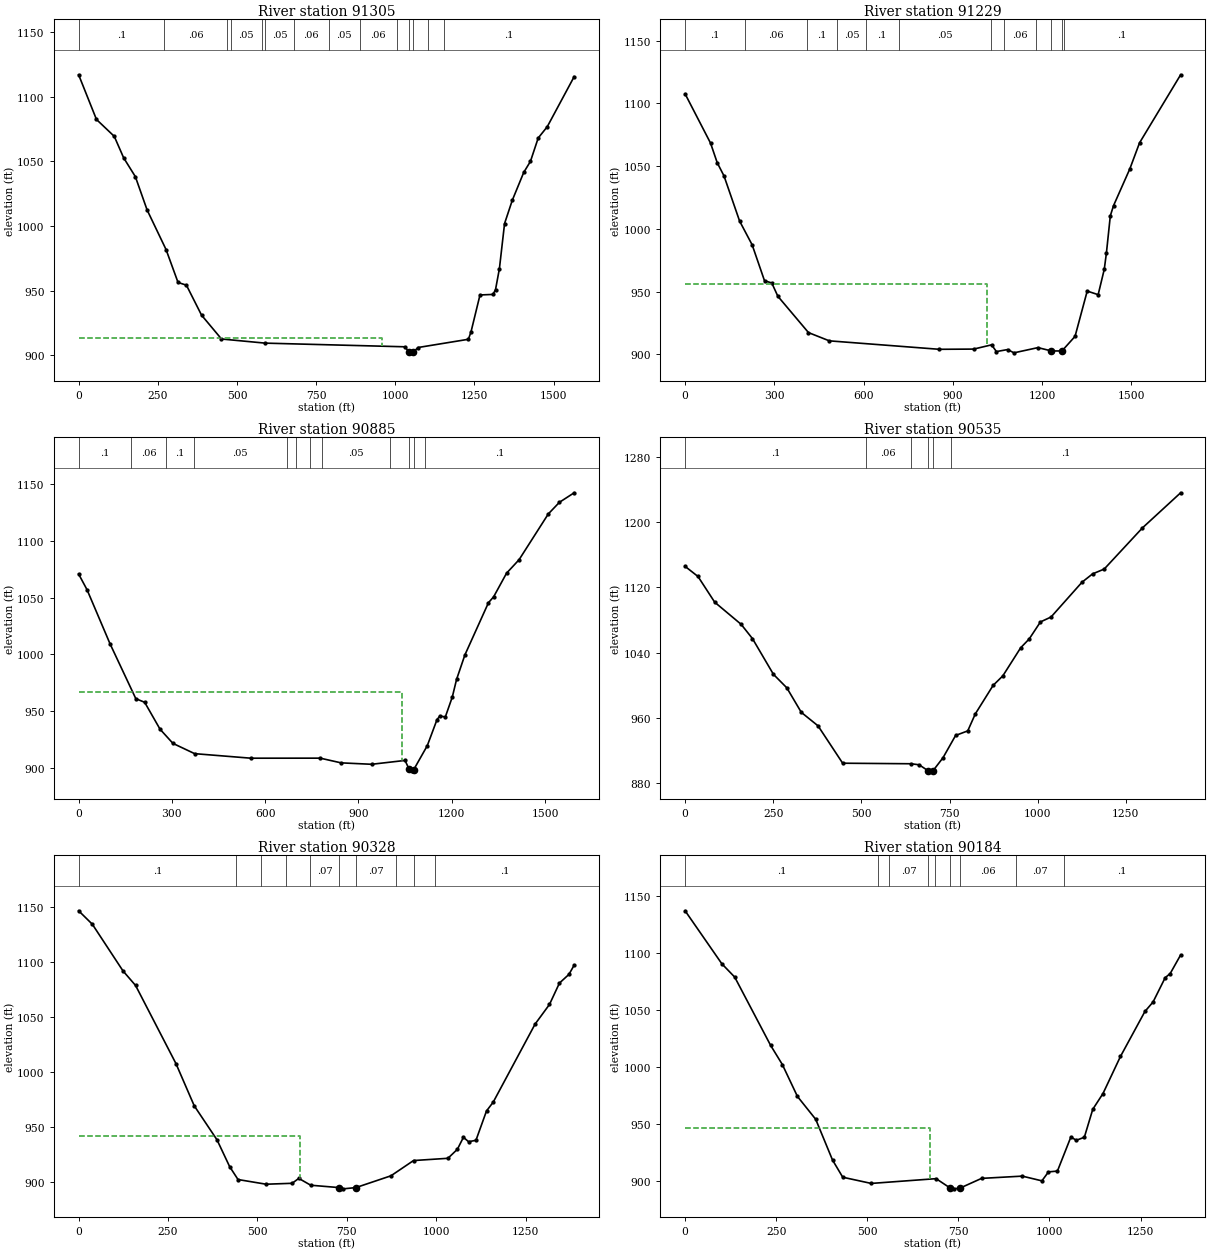
Type RM Length L Ch R = 1 ,91305   ,74.4,76,78.2
BEGIN DESCRIPTION:
Structure 27 XS 3
END DESCRIPTION:
XS GIS Cut Line= 6
1678590.49742684354970.6877905161678460.83739244355493.958643599
 1678601.3024297355852.0673100161678744.85461064355811.934442227
1678806.25883076355806.2992015381678892.70772984356227.876954254
#Sta/Elev= 30
       0 1117.17    56.3 1082.56   112.5 1069.48   142.2 1052.81   179.1 1038.26
   216.2 1012.46     276   981.8   313.9  956.28   340.4  954.16   388.2  930.93
   451.1  912.47   589.1  909.27  1030.5  906.43  1042.5  902.45  1047.1  901.75
 1057.27902.4015  1071.7  905.87  1230.7  912.25  1238.9  917.86  1267.4  946.58
  1308.3  947.01  1316.4  950.67  1328.7  966.94    1345 1001.92  1369.5 1020.01
  1405.6 1041.56  1426.7 1050.07  1451.2 1068.18  1479.8 1076.92  1564.8 1115.73
#Mann= 14 ,-1,0
       0      .1       0     270     .06       0     470      .1       0
     480     .05       0   579.1      .1       0   589.1     .05       0
   679.1     .06       0   789.1     .05       0   889.1     .06       0
 1003.77     .07       0  1042.5    .045       0 1057.27     .07       0
 1102.82     .08       0 1154.49      .1       0
#XS Ineff= 2 , 0
          957.48  913.28
Permanent Ineff=
       F       F
Bank Sta=1042.5,1057.27
XS Rating Curve= 0 ,0
Exp/Cntr(USF)=0,0
Exp/Cntr=0.8,0.6

Type RM Length L Ch R = 1 ,91229   ,322.9,343.3,364.8
BEGIN DESCRIPTION:
Structure 27 XS 2
END DESCRIPTION:
XS GIS Cut Line= 6
1678511.23365757354937.4558556691678377.62653176355489.311375324
1678548.53285119355932.2620612011678592.29311279355919.759129313
1678778.58679792 355881.000040461678858.67341264356259.684700196
#Sta/Elev= 30
       0 1107.57    85.5 1068.32   107.9 1052.72   130.8 1042.13   183.2 1006.15
   225.4  987.19   266.9  958.59   291.3  956.83   311.8   946.2   414.7  917.26
   484.7  910.68   854.2  903.94     970  904.11  1030.1   907.5  1046.3  902.13
  1084.1  903.74  1105.2  901.12    1186  905.28    1231  902.64  1266.5  902.61
  1310.6  914.24  1351.5  950.36  1388.3  947.49  1408.8  967.68  1415.9   980.4
  1429.2 1010.41    1440 1018.48  1494.7 1047.75  1527.4 1068.53  1665.5 1122.78
#Mann= 12 ,-1,0
       0      .1       0     200     .06       0     410      .1       0
     510     .05       0   607.8      .1       0   717.8     .05       0
  1027.8     .07       0 1072.58     .06       0 1177.92     .07       0
    1231    .045       0  1266.5     .07       0 1273.43      .1       0
#XS Ineff= 2 , 0
         1014.52  956.03
Permanent Ineff=
       F       F
Bank Sta=1231,1266.5
XS Rating Curve= 0 ,0
Exp/Cntr(USF)=0,0
Exp/Cntr=0.3,0.1

Type RM Length L Ch R = 1 ,90885   ,350.2,349.9,347.8
BEGIN DESCRIPTION:
Structure 27 XS 1
END DESCRIPTION:
XS GIS Cut Line= 3
1678444.32370625354974.2521819981678271.67379516355675.919128349
1678661.24282532356455.057188651
#Sta/Elev= 30
       0 1070.88    27.1 1057.01   101.2 1009.16   183.9  960.85   212.4  957.63
   261.9  933.85   303.3  921.36   373.1  912.29   554.1  908.28     777  908.32
     844  904.17   942.4  902.91  1049.8  906.31  1063.2  898.35  1072.1  897.12
 1077.95898.2978  1121.3  919.33  1152.7  942.44  1161.7  945.44  1179.4  944.76
  1201.8  962.35  1215.5  977.87  1242.3   999.5  1318.1 1045.61  1334.6 1050.74
  1376.2 1071.63  1416.5 1083.55  1510.5 1123.96  1546.2 1134.23  1593.7 1142.65
#Mann= 12 ,-1,0
       0      .1       0     170     .06       0     280      .1       0
     370     .05       0     670     .07       0     700     .05       0
   742.6     .07       0   782.6     .05       0  1002.6     .07       0
  1063.2    .045       0 1077.95     .07       0  1112.6      .1       0
#XS Ineff= 2 , 0
         1040.98   966.9
Permanent Ineff=
       F       F
Bank Sta=1063.2,1077.95
XS Rating Curve= 0 ,0
Exp/Cntr(USF)=0,0
Exp/Cntr=0.5,0.3

Type RM Length L Ch R = 1 ,90535   ,190.7,207.7,234.4
BEGIN DESCRIPTION:
Structure 26 XS 4
END DESCRIPTION:
XS GIS Cut Line= 6
 1677684.0115937355637.4478981631677816.80233862355787.416758342
1678013.64610504356002.8369311671678070.26377395356070.088765172
1678261.37297179356348.2679988431678535.29040295356752.022768749
#Sta/Elev= 30
       0 1145.87    36.6 1133.44    83.9  1101.9   158.9 1074.69   191.1 1057.12
   250.6 1013.24   288.4  996.73   329.6  966.54     377  949.99   446.9  904.08
   640.6  903.41   663.7  902.16  688.75894.9271   694.7  894.71   703.2  894.89
   731.4  910.77   767.2  938.19   801.6  943.78   823.1  964.69   873.6  999.69
   901.1 1011.37   951.7 1045.86   975.9 1056.71  1007.8 1077.63  1037.8 1083.65
  1125.8 1126.47  1155.8 1136.69  1188.6 1142.56    1297 1193.12  1405.4 1236.28
#Mann= 6 ,-1,0
       0      .1       0  512.12     .06       0  640.03     .07       0
  688.75    .045       0   703.2     .07       0  755.03      .1       0
Bank Sta=688.75,703.2
XS Rating Curve= 0 ,0
Exp/Cntr(USF)=0,0
Exp/Cntr=0.3,0.1

Type RM Length L Ch R = 1 ,90328   ,147.8,143.3,129
BEGIN DESCRIPTION:
Structure 26 XS 3
END DESCRIPTION:
XS GIS Cut Line= 6
1677573.91240285355761.6324604561678036.39585338356215.113800028
1677985.75897924356270.2517296531677956.50211862 356311.88649284
1677825.15875244356565.1910906631678112.91103335356719.548274464
#Sta/Elev= 30
       0 1146.37    38.4 1134.11   124.1 1091.74   159.2 1078.57     272 1007.69
   323.2  969.31   386.9   938.4   422.2  914.09   445.6  902.38   524.1  898.13
   596.9  898.96   615.5  903.41   648.9  897.21  729.31 895.033   740.1  893.93
  775.22895.0714   873.2  905.77   936.3  919.61  1032.5  921.66  1058.9  929.83
  1075.8  940.74  1090.1  936.73  1110.8  937.98  1140.3  964.62    1159  972.61
  1276.2 1043.53  1316.4 1061.34  1344.2 1080.73  1370.8 1088.63  1385.4 1097.02
#Mann= 10 ,-1,0
       0      .1       0     440     .06       0     510     .05       0
     580     .06       0  647.72     .07       0  729.31    .045       0
  775.22     .07       0  886.86      .1       0  936.86     .06       0
  996.86      .1       0
#XS Ineff= 2 , 0
          619.99  942.07
Permanent Ineff=
       F       F
Bank Sta=729.31,775.22
XS Rating Curve= 0 ,0
Exp/Cntr(USF)=0,0
Exp/Cntr=0.3,0.1

Type RM Length L Ch R = 1 ,90184   ,374.9,364,352.1
BEGIN DESCRIPTION:
Structure 26 XS 2
END DESCRIPTION:
XS GIS Cut Line= 6
1677510.72745211355821.9898353291677929.96918589356231.703347885
1677878.51679129356304.1178291741677828.97004093 356405.11697413
1677743.21604993 356576.624956131678072.89250422356767.189380575
#Sta/Elev= 30
       0 1137.04   100.9 1090.59   136.2 1078.93   234.7 1019.14   266.9 1002.35
   308.3  974.41   358.5  954.35   404.6  918.69   432.7  903.61   510.9  898.18
   688.9  902.36  727.73 894.123   737.9  893.44   754.9  894.13   813.7   902.6
   925.5  904.58   979.3  900.44   997.4   908.3  1021.9  908.99  1058.9  938.91
  1073.6  935.96  1095.8  938.62  1118.9  963.11    1147  976.95  1194.9 1009.39
  1262.1 1048.84  1284.4 1057.12  1317.6 1078.38  1331.5 1082.09  1360.1 1098.33
#Mann= 9 ,-1,0
       0      .1       0     530     .05       0     560     .07       0
   666.2     .05       0  685.03     .06       0  727.73    .045       0
   754.9     .06       0  907.53     .07       0 1039.28      .1       0
#XS Ineff= 2 , 0
          673.33  946.72
Permanent Ineff=
       F       F
Bank Sta=727.73,754.9
XS Rating Curve= 0 ,0
Exp/Cntr(USF)=0,0
Exp/Cntr=0.3,0.1

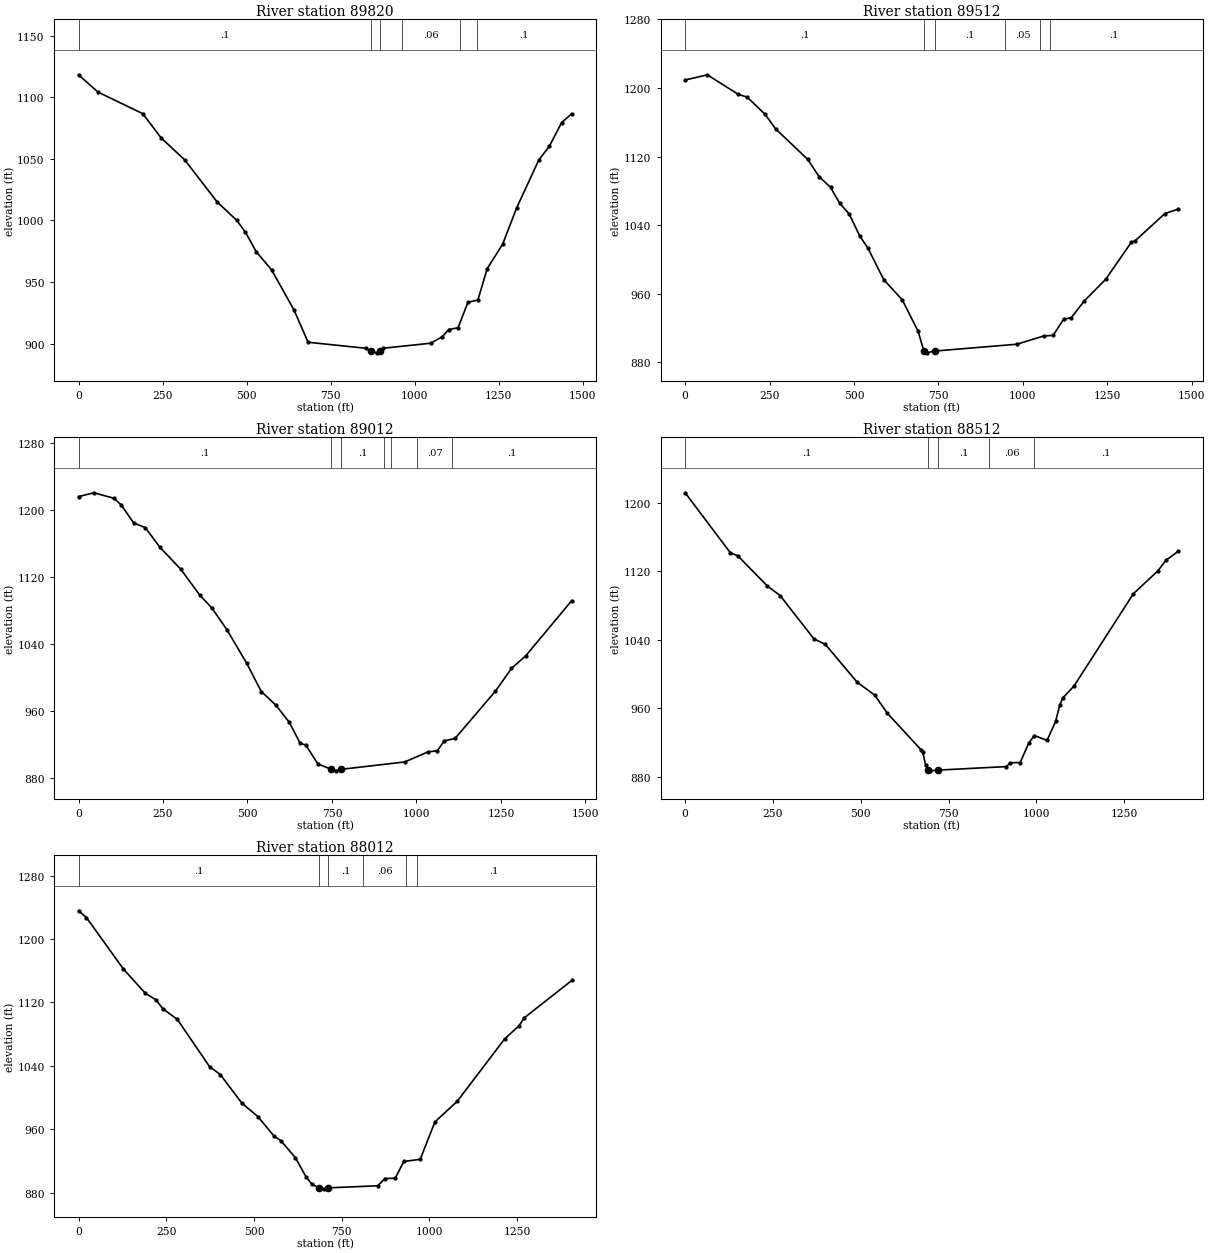
Type RM Length L Ch R = 1 ,89820   ,313.9,308.2,291.9
BEGIN DESCRIPTION:
Structure 26 XS 1
END DESCRIPTION:
XS GIS Cut Line= 6
1676784.57346746356219.523555276 1677455.6362193356416.623958142
1677541.58125738  356554.53575581677594.47091538356639.404352473
1677680.41628154356777.3161501461677978.33548381356948.372459704
#Sta/Elev= 30
       0 1118.24    57.9 1104.21   191.3 1086.66   245.5 1067.13   316.4 1049.03
   412.9 1014.89   470.6 1000.18   496.7  990.55   528.9  974.62   574.8  959.81
   641.7   927.1   683.2  901.14   854.8  896.27     869  893.73   889.4  892.55
     897  893.74   906.7  896.29  1047.9  900.35    1083  905.69  1101.1  911.44
  1129.5   912.9  1158.8   933.5  1188.6  935.45  1216.3  960.92  1262.4  980.86
  1303.9 1010.22  1369.7 1049.05  1400.8 1060.04  1437.7 1079.45  1467.9 1086.63
#Mann= 6 ,-1,0
       0      .1       0     869    .045       0     897      .1       0
  961.91     .06       0 1134.41     .07       0 1184.41      .1       0
Bank Sta=869,897
XS Rating Curve= 0 ,0
Exp/Cntr(USF)=0,0
Exp/Cntr=0.3,0.1

Type RM Length L Ch R = 1 ,89512   ,487.2,500,521.1
XS GIS Cut Line= 6
1676699.54935583356363.1753671771676845.20359209356518.978205174
 1676927.5301991356578.9997386781677353.82101317356732.617541671
1677419.47869025356771.6443665031677877.22744668  357183.8207075
#Sta/Elev= 30
       0 1209.27    65.5 1215.39   157.2 1192.56   183.6 1189.31   236.8  1169.2
   268.1  1152.2   362.7  1116.8   396.7 1096.51   430.7 1083.96   457.6 1065.55
     486 1052.84     517 1027.37   541.3 1013.14     588  976.44   643.3  952.58
   690.1  915.95   707.1  892.86   715.6  890.93   738.9  893.01   982.2  900.96
  1061.5  910.56  1089.8  911.25  1120.9  930.15    1144  932.09  1181.9  951.42
  1245.5  976.71    1321 1019.72  1333.3 1021.86    1421  1053.5  1460.9 1058.68
#Mann= 6 ,-1,0
       0      .1       0   707.1    .045       0   738.9      .1       0
  948.18     .05       0  1050.3     .06       0  1080.3      .1       0
Bank Sta=707.1,738.9
XS Rating Curve= 0 ,0
Exp/Cntr(USF)=0,0
Exp/Cntr=0.3,0.1

Type RM Length L Ch R = 1 ,89012   ,499.8,500,499.2
XS GIS Cut Line= 6
1676694.09234576356371.7537620961676883.87543076356647.627226084
1676932.80643526 356745.079787091676959.03899434356842.076312259
1676980.53337392 357005.308925421677050.57391626357752.423572928
#Sta/Elev= 30
       0 1216.05    45.5 1220.62   104.8 1214.07   126.3 1206.11   163.4 1184.42
   197.6 1179.06   240.2 1155.79   302.8 1129.22   358.3 1098.62   394.2 1083.19
   438.9 1057.21   497.3  1017.3   540.8  983.27   583.3  967.29   623.7  946.57
   655.9  921.35   672.1   919.6   708.3   896.8   748.5  890.31   761.9  888.56
  777.81890.3827   965.5  899.19  1033.8  911.16  1061.9  912.55    1082  924.35
  1114.1  927.25  1233.3  983.56    1281 1010.79    1323 1025.78  1459.5 1091.88
#Mann= 7 ,-1,0
       0      .1       0   748.5    .045       0  777.81      .1       0
  904.12     .05       0  924.12     .08       0 1001.62     .07       0
 1105.37      .1       0
Bank Sta=748.5,777.81
XS Rating Curve= 0 ,0
Exp/Cntr(USF)=0,0
Exp/Cntr=0.3,0.1

Type RM Length L Ch R = 1 ,88512   ,506.4,500,490.8
XS GIS Cut Line= 6
1676419.47740942356407.6654356721676513.41193284357315.710535586
1676533.02508259357505.3236734271676543.15399934357603.238831922
1676557.50502051357702.258318916  1676581.975444357801.525180757
#Sta/Elev= 30
       0 1211.62   128.9 1141.39   149.7 1138.07   234.1 1102.66   270.3 1091.55
   366.8 1040.86     399 1034.55   489.7  990.34   539.7  975.25   575.9  953.92
   671.9  911.24   676.5  908.45   684.5  893.57  691.12887.7803   696.6  886.81
   719.3  887.65   913.7  891.76   925.8   896.2   953.9  896.55   978.1  919.22
   994.1  928.07  1030.3  922.38  1054.5  944.48  1066.5  963.62  1074.6  971.81
  1106.7  985.73    1276 1093.71  1345.6 1120.33  1368.8 1132.72  1404.2 1143.45
#Mann= 5 ,-1,0
       0      .1       0  691.12    .045       0   719.3      .1       0
  865.39     .06       0  992.89      .1       0
Bank Sta=691.12,719.3
XS Rating Curve= 0 ,0
Exp/Cntr(USF)=0,0
Exp/Cntr=0.3,0.1

Type RM Length L Ch R = 1 ,88012   ,508.9,500,487.2
XS GIS Cut Line= 6
1675619.20735642356766.2428025011675678.50776276356846.546447679
1675740.22220625356924.2848092621675862.21868142357076.815672174
1676423.93212493357788.983867258  1676508.574016357849.696672335
#Sta/Elev= 30
       0 1235.51    22.7 1226.84   128.1  1161.9   190.6 1131.35     220 1123.33
   240.5  1111.9   281.7 1098.43   373.6 1038.79   404.1 1028.92   465.4  992.88
   511.2  975.92   557.1  951.33   577.4  945.14   618.2  923.82   648.8  899.57
   664.1  891.06   684.4  885.91   699.7  884.73  711.11885.9595   852.6  888.58
   872.9   897.7   902.5  898.17   927.1   919.3   973.7  921.92  1015.6  969.14
  1079.1  995.14  1214.3 1073.87    1255 1090.31  1270.3 1100.49  1405.6 1147.58
#Mann= 6 ,-1,0
       0      .1       0   684.4    .045       0  711.11      .1       0
  810.65     .06       0  933.15     .07       0  963.15      .1       0
Bank Sta=684.4,711.11
XS Rating Curve= 0 ,0
Exp/Cntr(USF)=0,0
Exp/Cntr=0.3,0.1