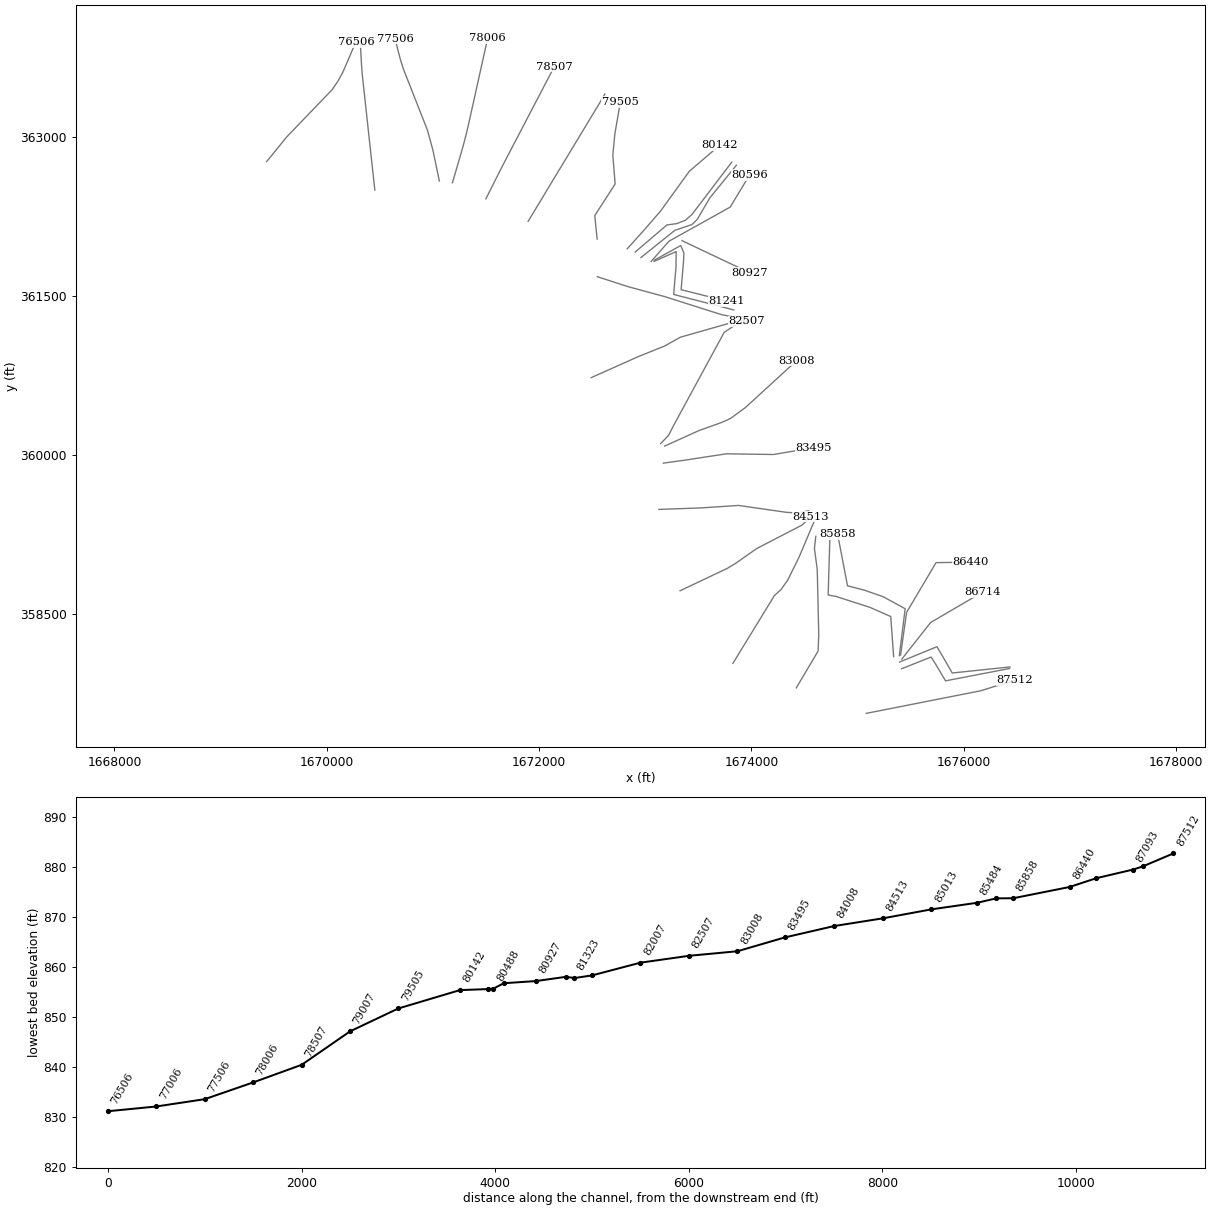
HEC-RAS study SFFSHGCK.prj: SFFSHGCK

--- SFFSHGCK.g01 (geometry) --- (continued)

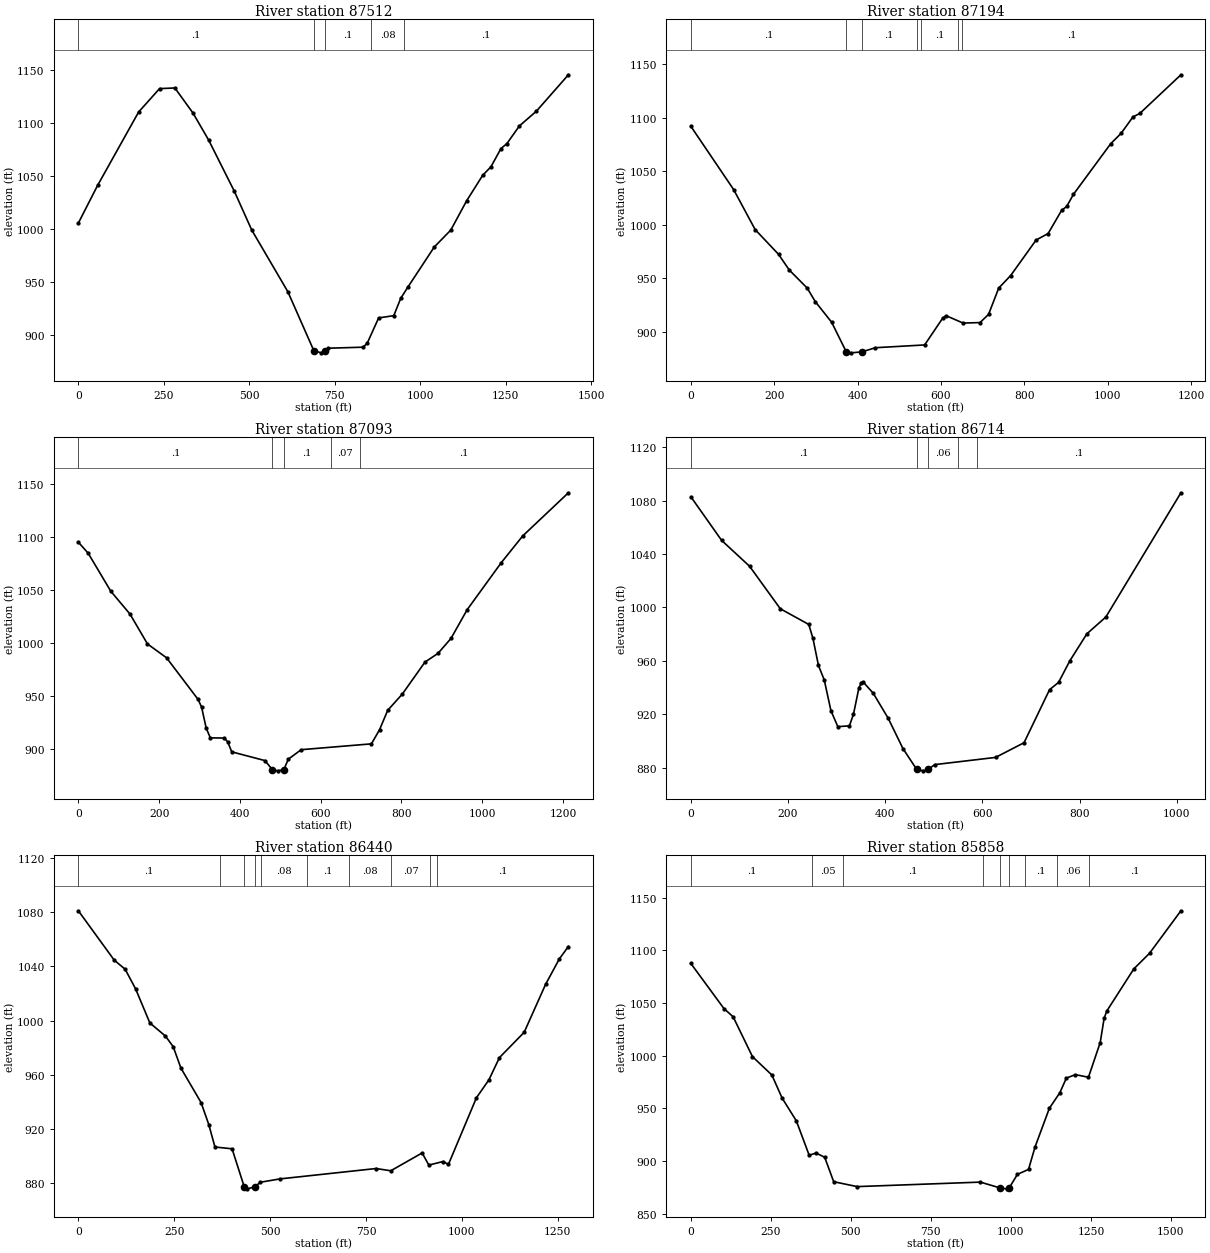
Type RM Length L Ch R = 1 ,87512   ,337.2,318.4,299.7
BEGIN DESCRIPTION:
Structure 25 XS 4
END DESCRIPTION:
XS GIS Cut Line= 6
1675083.16905843357565.6322798431675561.79900667357660.240030259
1676165.73841558357779.619384676 1676260.4075176357809.838812426
1676368.79476801357841.594654426 1676481.0051735357876.002394006
#Sta/Elev= 30
       0 1005.37    56.2 1040.93   176.3 1110.39   237.5 1132.48   282.3 1133.11
   335.3 1109.38   381.2 1083.77   456.1  1035.5   507.1  998.79   612.6  940.55
   688.7  884.75   710.4  882.71  721.67884.7274   730.8   887.1   832.8  888.05
     845  891.92   878.2  915.71   922.5  917.87   942.8  934.21   963.2  944.58
  1040.7  982.68  1089.3  998.78  1135.4 1026.35  1182.5 1050.51  1206.8 1058.65
  1235.9 1075.81  1253.2 1080.46  1290.1 1097.28  1339.5 1111.12  1433.2 1145.57
#Mann= 5 ,-1,0
       0      .1       0   688.7    .045       0  721.67      .1       0
  855.39     .08       0  952.89      .1       0
Bank Sta=688.7,721.67
XS Rating Curve= 0 ,0
Exp/Cntr(USF)=0,0
Exp/Cntr=0.3,0.1

Type RM Length L Ch R = 1 ,87194   ,99.1,101,104
BEGIN DESCRIPTION:
Structure 25 XS 3
END DESCRIPTION:
XS GIS Cut Line= 5
1675416.75099148357986.5638060481675694.12809817358096.667695727
1675738.59313054358026.7940734311675829.64057777357872.225151381
1676433.09458851357988.681188542
#Sta/Elev= 30
       0 1091.81   102.6 1032.66   154.2  995.27   210.2  972.21     236  957.48
     279  940.62   298.4  927.94   337.6  908.69  372.65 881.047   384.2   880.1
   410.3     881   442.4  884.89   560.6  887.48   603.9  912.51     612  914.85
   652.8  907.92   693.5  908.39   713.9  916.04   738.3  940.63   766.9  952.32
     828  985.56   856.7  991.57   889.1 1013.24   901.3 1016.91   917.6 1028.31
  1006.9 1075.56  1031.7 1085.22  1060.2 1100.59  1076.5 1103.79  1175.2 1139.97
#Mann= 7 ,-1,0
       0      .1       0  372.65    .045       0   410.3      .1       0
  541.25     .07       0  551.25      .1       0  640.64     .07       0
  650.64      .1       0
Bank Sta=372.65,410.3
XS Rating Curve= 0 ,0
Exp/Cntr(USF)=0,0
Exp/Cntr=0.3,0.1

Type RM Length L Ch R = 1 ,87093   ,351.6,378.5,393.6
BEGIN DESCRIPTION:
Structure 25 XS 2
END DESCRIPTION:
XS GIS Cut Line= 5
1675397.69454903358050.0852808631675749.18004301358194.067290444
1675827.52319528358060.6721933321675893.16205259357946.333538665
 1676437.3293535358003.502865999
#Sta/Elev= 30
       0 1095.12    24.2 1084.79    80.4 1048.84     128 1027.26   171.2  999.13
   218.4   986.1   296.6  946.78   305.2  939.53   316.5  919.84   326.8  910.58
   361.4   910.4     370  906.69   379.8  897.39     462  889.14   480.4   880.6
   494.1  879.47   508.8  880.58   519.9  890.44   551.8  899.42   725.7  904.92
   745.8   918.2   766.1  936.58   802.1  951.81   858.4  982.07   890.6  990.26
   922.7 1004.32   962.9 1031.51  1047.4 1075.87  1100.5 1101.08  1213.5 1141.73
#Mann= 5 ,-1,0
       0      .1       0   480.4    .045       0   508.8      .1       0
  624.53     .07       0  696.37      .1       0
Bank Sta=480.4,508.8
XS Rating Curve= 0 ,0
Exp/Cntr(USF)=0,0
Exp/Cntr=0.3,0.1

Type RM Length L Ch R = 1 ,86714   ,265.4,274.3,277.1
BEGIN DESCRIPTION:
Structure 25 XS 1
END DESCRIPTION:
XS GIS Cut Line= 3
1675418.15483446358077.6432028131675690.01629046358422.698127734
1676181.45815323358710.243898501
#Sta/Elev= 30
       0 1082.78    63.3 1050.17   120.8 1030.84   184.1  999.01   242.7  987.28
   251.3  976.83   262.6  956.63   274.6   945.7   288.3  922.76   302.5  910.83
   326.3   911.4   334.7  920.09   345.7  939.47   350.9  943.84   355.1  944.04
   375.4   935.8     406   917.2   436.5  894.44   464.9  878.78   478.8  877.75
  488.85878.9431     502  882.41   627.1  887.79   685.8  898.78   738.3  938.46
   756.9  943.93     780  960.02   815.2   980.3   854.2  992.83  1008.7 1085.79
#Mann= 5 ,-1,0
       0      .1       0   464.9    .045       0  488.85     .06       0
  549.29     .07       0  589.29      .1       0
Bank Sta=464.9,488.85
XS Rating Curve= 0 ,0
Exp/Cntr(USF)=0,0
Exp/Cntr=0.3,0.1

Type RM Length L Ch R = 1 ,86440   ,582.4,582.4,582.4
BEGIN DESCRIPTION:
Structure 24 XS 4
END DESCRIPTION:
XS GIS Cut Line= 4
1675406.16407901358115.7241381721675463.33340634   358518.026812
1675740.80732979358986.8629299791676067.46707072358991.510134355
#Sta/Elev= 30
       0 1080.83    93.7 1044.41     122 1037.78   149.4 1023.23   186.4  998.22
   227.1  988.53   247.3  980.72   267.5  964.89     320  939.56   340.2  923.24
   356.2  906.81   400.8   905.5   432.5  877.53   439.3     876   460.4   877.4
   474.3  880.85   525.7  883.32   776.5  890.97   814.6   889.3   896.4  902.44
   913.9   893.5   951.1  896.13     965  894.01    1038   943.1  1070.5  956.27
    1098  972.68  1162.5  991.32  1218.5 1026.74  1254.5 1045.53  1277.8 1054.47
#Mann= 10 ,-1,0
       0      .1       0     370     .05       0   432.5    .045       0
   460.4     .05       0  476.34     .08       0  596.34      .1       0
  706.34     .08       0  816.34     .07       0  916.34     .06       0
  936.34      .1       0
Bank Sta=432.5,460.4
XS Rating Curve= 0 ,0
Exp/Cntr(USF)=0,0
Exp/Cntr=0.3,0.1

Type RM Length L Ch R = 1 ,85858   ,176.5,176.5,176.5
BEGIN DESCRIPTION:
Structure 24 XS 3
END DESCRIPTION:
XS GIS Cut Line= 6
1675394.92397807358109.4546339591675449.63900059358552.402919061
1675240.25339843358666.7096241971675063.07873159358727.704181633
 1674906.2355839358768.3672199231674813.29149638359256.323679407
#Sta/Elev= 30
       0  1087.5   103.3 1044.75   132.1 1036.93   192.5  999.12     253  981.76
   285.2   959.8   329.6  938.22   369.7  905.58   391.3  907.72   418.2  903.66
   446.3   880.5   519.7  875.87   904.6  880.13   966.5  874.57   987.5  873.75
  994.76874.6003  1020.3  887.46  1055.1  892.19  1075.5  913.48  1120.3   950.2
  1152.9  964.85  1173.4  978.82  1201.7  982.07  1242.4  979.59  1279.1 1012.48
  1291.3 1035.37  1299.4 1042.28  1384.2 1082.39  1433.3 1097.19  1531.3 1137.49
#Mann= 9 ,-1,0
       0      .1       0     380     .05       0  476.31      .1       0
  912.57     .06       0   966.5    .045       0  994.76     .06       0
 1044.59      .1       0 1144.59     .06       0 1244.59      .1       0
Bank Sta=966.5,994.76
XS Rating Curve= 0 ,0
Exp/Cntr(USF)=0,0
Exp/Cntr=0.3,0.1

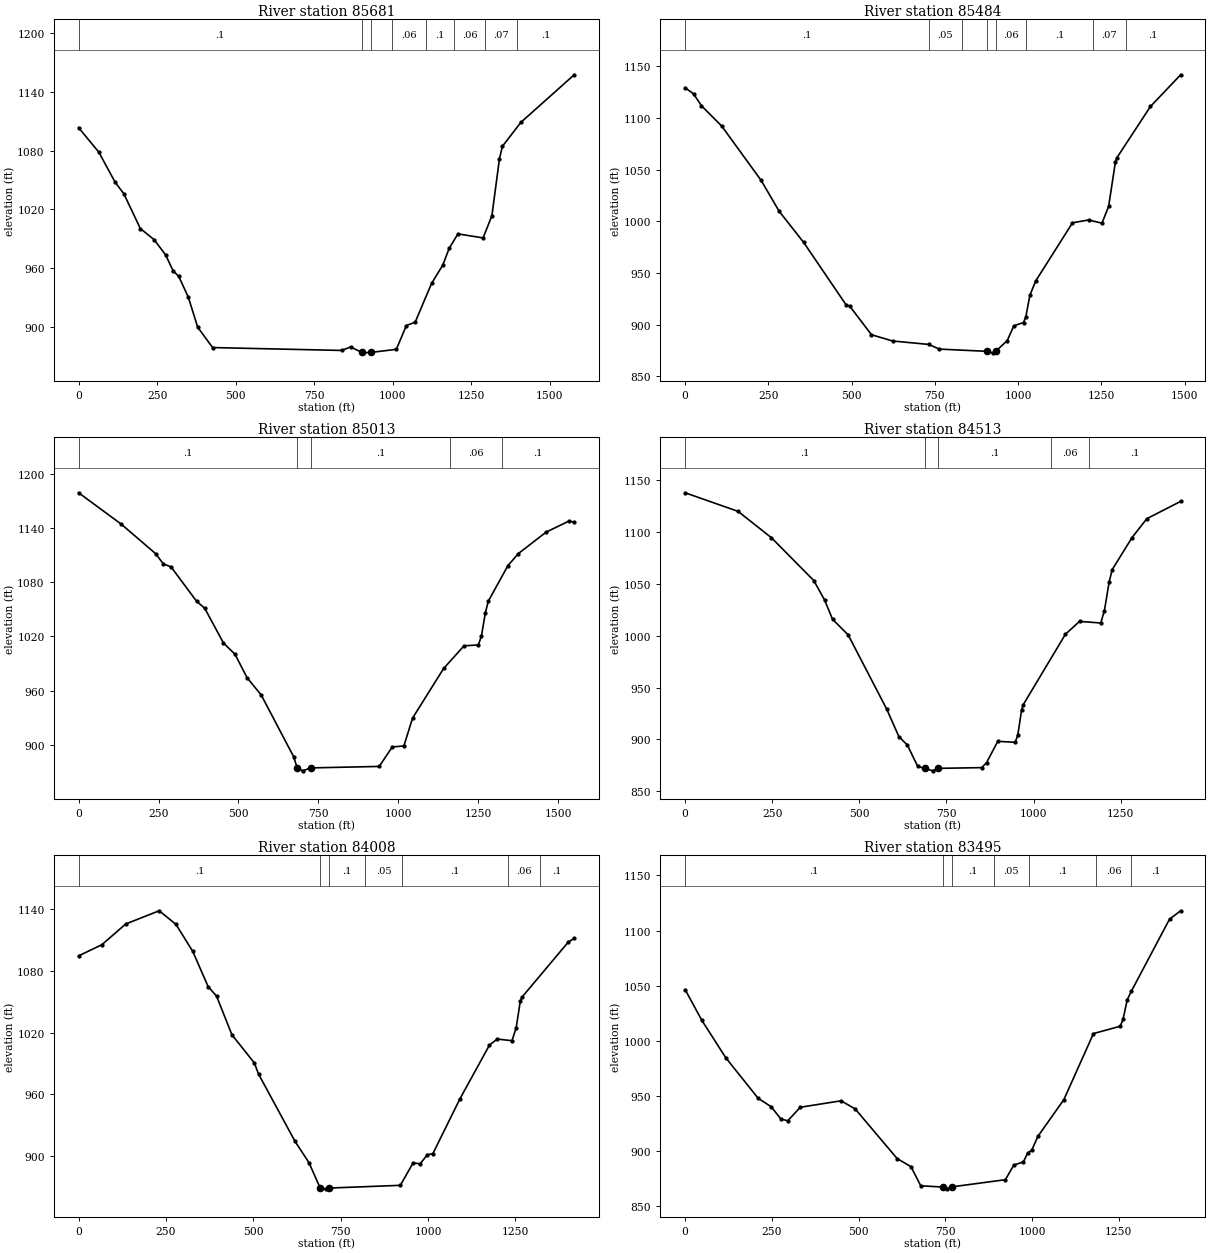
Type RM Length L Ch R = 1 ,85681   ,202.9,196.8,173
BEGIN DESCRIPTION:
Structure 24 XS 2
END DESCRIPTION:
XS GIS Cut Line= 6
1675341.15872794358100.7411257541675313.68794107358478.704066662
1675116.18175509358565.8391487131674799.59095698358667.496744439
1674724.07388587358682.0192581141674741.50090228359254.206296913
#Sta/Elev= 30
       0 1103.26      64 1078.46   116.1 1047.73   144.2 1035.78   196.3 1000.49
   240.4  989.08   276.5  973.73   300.6  957.46   318.7  951.64     349  930.49
     379  899.79   426.4   879.1   837.2  876.16   865.4  879.74  901.34 874.194
   905.9  873.72   931.2  874.19  1011.1  877.28  1043.1  901.58  1071.2  905.03
  1123.2  944.46  1159.2  963.33  1179.2  980.26  1207.2  995.01  1287.3   990.9
  1315.3 1013.62  1339.3 1071.68  1348.8 1084.32  1407.3 1108.66  1577.1 1157.25
#Mann= 8 ,-1,0
       0      .1       0  901.34    .045       0   931.2      .1       0
   997.7     .06       0  1104.6      .1       0  1194.6     .06       0
  1294.6     .07       0  1394.6      .1       0
Bank Sta=901.34,931.2
XS Rating Curve= 0 ,0
Exp/Cntr(USF)=0,0
Exp/Cntr=0.3,0.1

Type RM Length L Ch R = 1 ,85484   ,481.1,471.4,454.8
BEGIN DESCRIPTION:
Structure 24 XS 1
END DESCRIPTION:
XS GIS Cut Line= 6
1674423.82129546357806.1774540111674629.30792211 358152.67947952
1674635.60096275358307.605933663 1674621.2889835358923.390463246
1674594.78378717359120.5167094141674607.74537542359234.611953659
#Sta/Elev= 30
       0 1129.37    25.3  1123.5    49.2 1111.96   109.7 1092.39     228 1039.89
   282.2 1009.94   356.2  979.62   482.8  919.55   494.8  917.82   559.5  890.39
   623.1   884.3   731.2     881   763.2  876.46   907.2  874.29   923.2  872.84
  932.74874.3796   967.2  884.66   987.2  899.03  1016.1  902.18  1023.2  907.86
  1035.2  928.49  1052.5   942.3  1163.2  998.68  1211.4 1001.42  1251.6  998.33
  1271.7 1014.54    1292 1057.56    1296 1061.41  1397.3 1111.24  1487.9 1141.93
#Mann= 8 ,-1,0
       0      .1       0  730.95     .05       0  830.95      .1       0
   907.2    .045       0  932.74     .06       0 1023.45      .1       0
 1224.07     .07       0 1322.89      .1       0
Bank Sta=907.2,932.74
XS Rating Curve= 0 ,0
Exp/Cntr(USF)=0,0
Exp/Cntr=0.3,0.1

Type RM Length L Ch R = 1 ,85013   ,504.5,499.8,487.1
XS GIS Cut Line= 6
1673826.84578368358037.4131604281674218.48738883358677.495213583
1674278.08405443358730.9271933441674342.63346601358820.893220752
1674450.61717393359039.7753289191674592.63854343 359376.32058759
#Sta/Elev= 30
       0 1178.77   133.1 1144.17   240.7 1111.58   265.1 1100.23   289.4 1096.77
     369 1058.96   394.5  1051.2   453.3 1012.74   489.3 1000.38   527.1  974.42
   571.3  955.35   672.6  887.31     684  874.77   701.6  871.53   725.6  874.77
   940.7   876.4   981.5  897.95  1017.8  899.03    1045  929.81  1142.2  984.61
  1206.1  1009.7  1251.1 1010.62  1260.6 1020.77  1272.8 1046.18    1282 1058.98
  1343.5 1098.36  1376.2 1111.61  1462.8 1135.28  1535.4 1147.69  1550.7 1146.01
#Mann= 5 ,-1,0
       0      .1       0     684    .045       0   725.6      .1       0
 1162.93     .06       0 1324.16      .1       0
Bank Sta=684,725.6
XS Rating Curve= 0 ,0
Exp/Cntr(USF)=0,0
Exp/Cntr=0.3,0.1

Type RM Length L Ch R = 1 ,84513   ,512.1,505.5,491.9
XS GIS Cut Line= 6
1673328.96160884358721.8734056651673771.48008075358931.472067833
1673846.87002183358976.2980936771674052.37354784   359120.574708
1674477.29297359359340.5496617561674561.97095384359418.065582842
#Sta/Elev= 30
       0 1137.98   151.9 1120.07   247.5 1094.72   369.3  1053.3   400.5 1034.42
     423    1016     468 1000.85     579  928.97   613.4  902.81     638  894.52
   667.6  873.94     688  872.16   710.3  869.74   727.1  872.14   851.3  872.84
   865.1  877.67   897.3  898.23   947.4  897.25   954.8  904.45   965.5  928.17
   970.1  933.43  1091.4  1001.5  1131.8 1013.91  1192.8 1012.36  1203.3 1024.34
  1216.7 1051.66  1225.6 1063.86  1282.4 1094.72  1324.9 1112.96    1422 1129.68
#Mann= 5 ,-1,0
       0      .1       0     688    .045       0   727.1      .1       0
 1051.33     .06       0 1158.79      .1       0
Bank Sta=688,727.1
XS Rating Curve= 0 ,0
Exp/Cntr(USF)=0,0
Exp/Cntr=0.3,0.1

Type RM Length L Ch R = 1 ,84008   ,512,512.5,510
XS GIS Cut Line= 6
1673129.62998651359488.6766620871673523.70137684359502.699599922
1673879.18458976 359526.059461341674332.40120301359461.049420759
1674433.83439909359455.0523855091674540.24166659359475.316780671
#Sta/Elev= 30
       0 1094.71    66.5 1105.51   134.9  1125.7   230.6 1138.52   278.6 1125.29
   326.7 1099.03   370.7 1064.77   394.7 1055.67   438.8 1017.98     503   990.6
     515  979.76   619.2  914.48   659.3  893.66   691.4  869.05   707.4  868.19
   716.2  868.94   920.9   871.6   957.4  893.39   977.7  892.55     998  901.24
  1014.2  902.51  1091.2  955.51    1176 1007.94  1198.3 1013.83  1240.4 1012.19
  1252.4 1024.52  1264.4  1050.9  1268.4 1054.26  1402.1 1108.28  1418.5 1111.67
#Mann= 7 ,-1,0
       0      .1       0   691.4    .045       0   716.2      .1       0
  820.58     .05       0  925.11      .1       0 1228.62     .06       0
 1320.23      .1       0
Bank Sta=691.4,716.2
XS Rating Curve= 0 ,0
Exp/Cntr(USF)=0,0
Exp/Cntr=0.3,0.1

Type RM Length L Ch R = 1 ,83495   ,474.2,487.3,493.5
XS GIS Cut Line= 5
1673171.39328752359924.9103407811673379.11668921359953.768550778
1673765.20165233360012.9401021651674210.10719244 360006.29972097
1674587.82158248360070.614971853
#Sta/Elev= 30
       0 1046.55    48.2 1018.63   117.3  984.67   210.7  947.93   248.1  940.36
   275.5  929.45   295.7   927.5   332.1  939.85   449.5   945.7   490.2  938.36
   611.2  893.34   651.2  885.99   679.2  868.67743.3428867.5162   755.2   865.9
768.5504867.6695   923.3  874.19   947.3  887.35   975.3  890.39   987.3  898.31
   999.3  901.07  1017.4  913.66  1091.9  946.82  1177.1 1006.64  1254.2 1013.26
  1262.4  1019.5  1274.5 1037.35  1286.7 1045.22  1396.3 1110.29  1428.4 1117.92
#Mann= 7 ,-1,0
       0      .1       0743.3428    .045       0768.5504      .1       0
  890.31     .05       0  990.31      .1       0 1185.27     .06       0
 1285.27      .1       0
Bank Sta=743.3428,768.5504
XS Rating Curve= 0 ,0
Exp/Cntr(USF)=0,0
Exp/Cntr=0.3,0.1

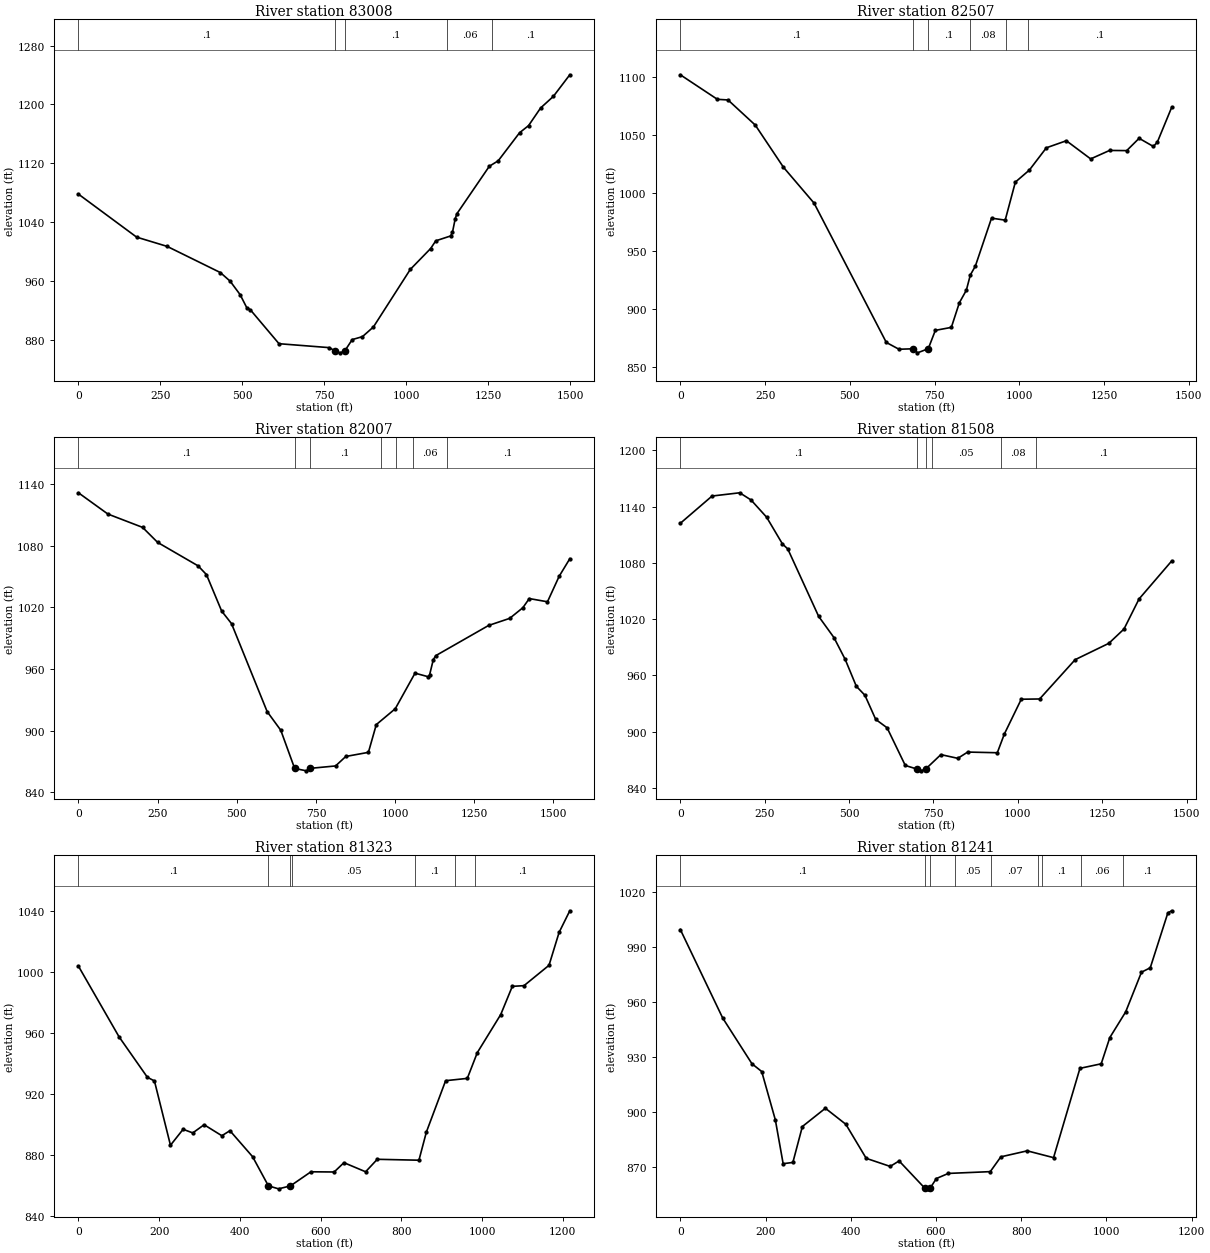
Type RM Length L Ch R = 1 ,83008   ,492.9,500.4,507.5
XS GIS Cut Line= 6
1673183.80409075360085.5156915041673507.77785225360232.429111585
1673716.07435167360306.7596715841673802.66112076360345.129345506
1673945.46332859360449.7088607551674425.08966592360889.449451089
#Sta/Elev= 30
       0 1078.43   177.6 1020.09   270.7 1007.54     433  972.06   462.8  960.43
   493.4  942.09   513.6  924.45   524.9   921.4     612  875.54   765.7   870.2
     784   865.4   798.3  863.15   812.3  865.47   835.5  881.13   866.7  885.12
   900.2  898.27  1012.7  976.31  1074.8 1004.66  1090.4 1015.08  1135.7 1021.68
  1141.4 1026.77  1149.8 1045.14  1154.8 1051.77  1253.9 1116.25    1281 1123.64
  1346.1 1161.68  1373.5 1171.32  1410.3 1195.27  1449.2 1210.98  1499.4  1240.3
#Mann= 5 ,-1,0
       0      .1       0     784    .045       0   812.3      .1       0
 1125.31     .06       0 1262.19      .1       0
Bank Sta=784,812.3
XS Rating Curve= 0 ,0
Exp/Cntr(USF)=0,0
Exp/Cntr=0.3,0.1

Type RM Length L Ch R = 1 ,82507   ,509.8,500.4,475
XS GIS Cut Line= 6
1673146.53808917360109.1734525861673220.94738917 360187.27369009
1673265.86265367360275.7849960031673744.15992543361157.539794177
1673837.08034326361219.5088303391673956.74513017361262.962483585
#Sta/Elev= 30
       0 1101.68   109.3 1080.55   140.7    1080   221.1 1058.35   304.2 1022.05
   394.5  991.16   607.6  871.19   644.9  865.33   687.3  865.74   699.5  862.24
   731.3  865.79   752.2   881.6   799.4  884.16     823  905.35   843.6  916.15
   855.4  929.28   870.2  936.91   917.9  978.23   958.2   976.5   988.2 1009.26
  1029.5 1019.62  1079.6  1038.8  1138.6 1044.88  1210.3 1029.24  1266.1 1036.53
  1316.6 1036.37  1353.2 1046.98  1395.3 1039.94    1407 1043.71  1449.3 1073.67
#Mann= 6 ,-1,0
       0      .1       0   687.3    .045       0   731.3      .1       0
  853.69     .08       0  961.19     .06       0 1024.94      .1       0
Bank Sta=687.3,731.3
XS Rating Curve= 0 ,0
Exp/Cntr(USF)=0,0
Exp/Cntr=0.3,0.1

Type RM Length L Ch R = 1 ,82007   ,510.3,499.1,479.1
XS GIS Cut Line= 6
1672491.25626326360730.8182066681672937.11101459360930.114724085
1673180.81229883361027.9022581731673331.69519918361112.114688173
  1673797.689674 361245.064225421673937.04995959361275.740017086
#Sta/Elev= 30
       0 1131.56      93 1110.86   202.6 1097.87   250.1 1083.26   377.9 1060.41
   404.2 1051.93   452.3 1016.38   483.4 1004.18   595.9  918.53   638.9  900.39
   682.7  863.22   719.9  860.87  730.78863.2648   811.9  865.63   844.2  874.86
   915.6  878.87   940.5  905.87  1000.4  921.32  1062.8  955.96    1104  952.52
  1108.6  954.05  1120.5  969.14  1128.4  973.03  1295.2 1002.41  1361.6 1009.29
  1403.1 1019.62  1423.6 1028.58    1481 1025.44    1518 1050.33  1551.5 1067.35
#Mann= 7 ,-1,0
       0      .1       0   682.7    .045       0  730.78      .1       0
  954.06     .06       0 1004.06      .1       0  1056.9     .06       0
 1162.64      .1       0
Bank Sta=682.7,730.78
XS Rating Curve= 0 ,0
Exp/Cntr(USF)=0,0
Exp/Cntr=0.3,0.1

Type RM Length L Ch R = 1 ,81508   ,210.9,184.7,154.8
XS GIS Cut Line= 6
1672549.05437601361682.6699775011672836.35202976361589.598313257
1673187.62626159361493.868845925  1673713.622913361326.599167332
  1673821.811673361304.038516924  1673949.110631361305.227162838
#Sta/Elev= 30
       0 1122.12    94.1  1151.2     176 1154.67   209.6 1146.99   255.7 1128.66
   302.7  1100.1   318.4 1094.82   409.9 1022.96   455.3 1000.32   488.6  977.05
   521.6  948.42     547  938.89     579  913.15   612.7  904.21   666.6  864.08
   700.4  860.32   713.1  858.33   727.6  860.46   772.1  875.63   822.2  871.66
   851.5  878.34   939.3  877.61   960.2  897.62  1010.3  934.65  1064.7  934.92
  1169.9   976.8  1269.7  994.21  1314.7 1009.48  1359.2 1041.46    1456 1081.99
#Mann= 6 ,-1,0
       0      .1       0   700.4    .045       0   727.6      .1       0
  746.12     .05       0  949.04     .08       0 1052.81      .1       0
Bank Sta=700.4,727.6
XS Rating Curve= 0 ,0
Exp/Cntr(USF)=0,0
Exp/Cntr=0.3,0.1

Type RM Length L Ch R = 1 ,81323   ,70.9,82,93.5
XS GIS Cut Line= 6
1673084.21377512361826.678180637 1673292.3917079361919.765874155
1673290.69920438361775.9030750821673282.23668679361679.430374527
1673268.69665864361515.2575332321673833.99283382 361369.70223064
#Sta/Elev= 30
       0 1003.95   100.7  957.54   170.8  931.02   188.3  928.59     228   886.4
   259.3  896.86   283.3   894.5   311.3  899.86   355.3  892.65   375.3  895.95
   431.5  878.87   470.6  859.74   495.8  857.79  525.23  859.73     576  868.98
   633.5  868.85   657.7  874.96   711.4  868.99   740.3  877.18   843.5  876.58
   861.9  895.04   909.6  928.77   963.3  930.28   988.1  947.19  1046.1  972.17
  1074.8  990.68  1103.8  991.14  1165.7  1004.5  1190.7 1026.11  1217.2 1040.28
#Mann= 7 ,-1,0
       0      .1       0   470.6    .045       0  525.23      .1       0
  528.76     .05       0  833.49      .1       0  933.49     .06       0
  983.49      .1       0
Bank Sta=470.6,525.23
XS Rating Curve= 0 ,0
Exp/Cntr(USF)=0,0
Exp/Cntr=0.3,0.1

Type RM Length L Ch R = 1 ,81241   ,311.3,314.4,324.1
XS GIS Cut Line= 6
1673085.06002688361837.6794535081673335.55054762361976.464742025
1673365.16935919361904.533342489 1673360.9381004361820.754418322
1673338.93555466361560.1088764721673768.83144836361451.788651288
#Sta/Elev= 30
       0  999.33    99.5  951.08   168.1  926.19     191  921.96     223   895.6
   241.3  871.75   264.1  872.43   286.4  891.99   340.4  901.95   388.4  893.21
   436.2  874.67   492.4  870.27   513.4  873.25  573.28  858.51   580.8  858.05
  586.51  858.53   600.8  863.66   628.9  866.45   727.3  867.42   752.1  875.48
     814  878.75   875.8  875.04   937.7  923.69   987.6  926.17  1007.8  940.45
    1045  954.44  1082.1  976.07  1102.7  978.47    1144 1008.39    1153 1009.53
#Mann= 9 ,-1,0
       0      .1       0  573.28    .045       0  586.51      .1       0
  644.89     .05       0  729.62     .07       0  839.62     .05       0
  849.62      .1       0  939.62     .06       0 1039.62      .1       0
Bank Sta=573.28,586.51
XS Rating Curve= 0 ,0
Exp/Cntr(USF)=0,0
Exp/Cntr=0.3,0.1

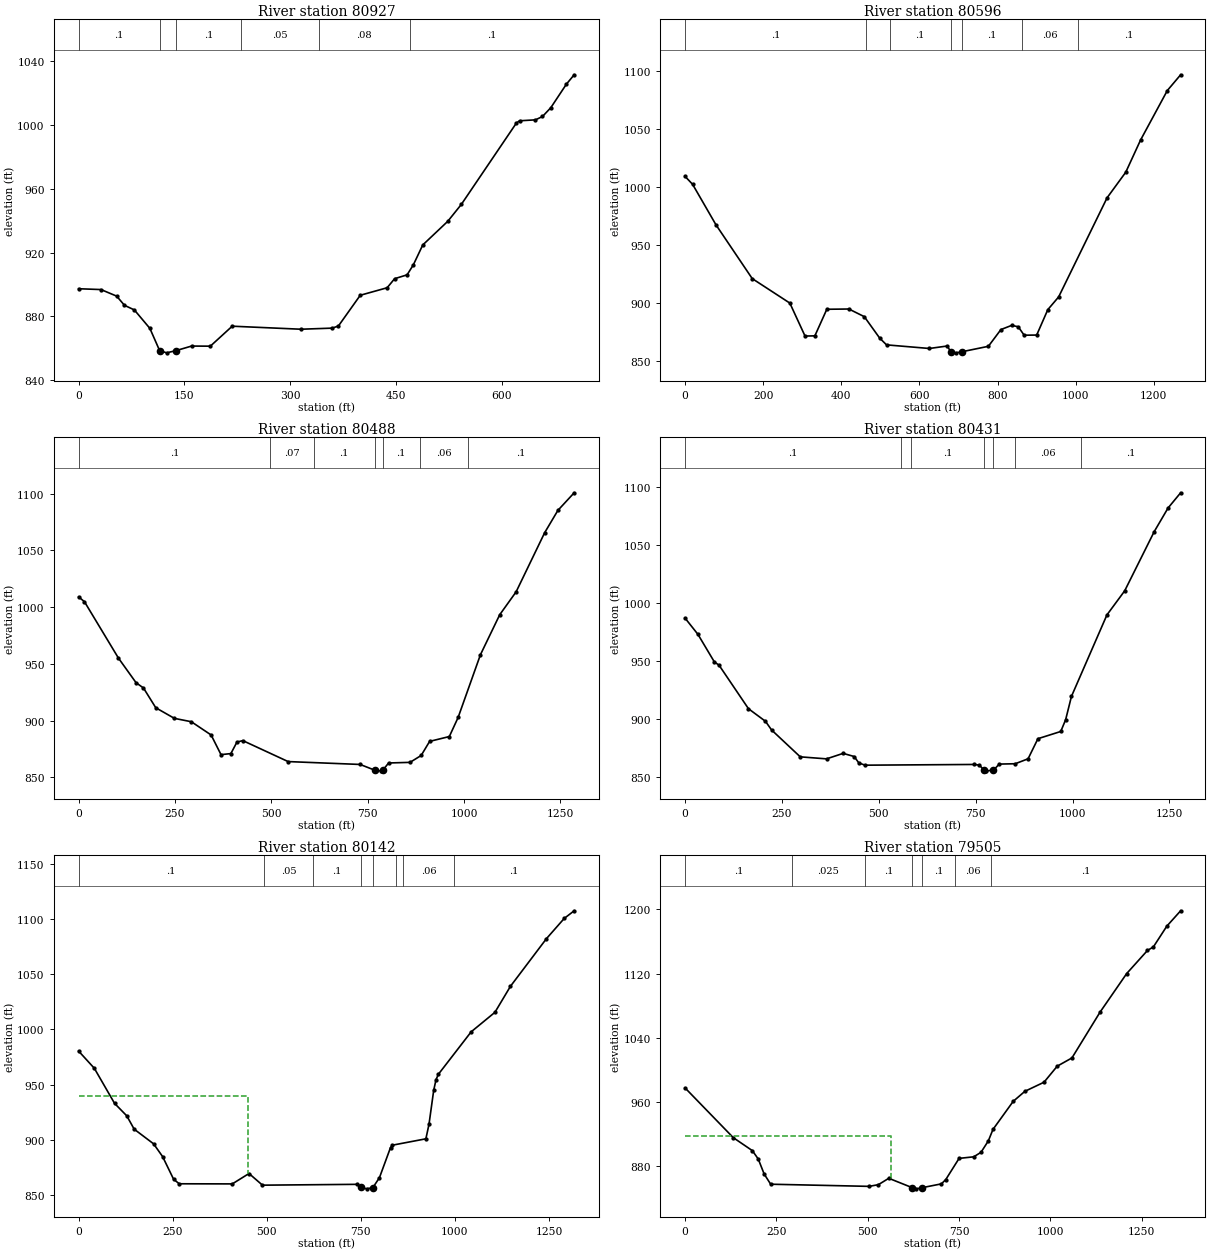
Type RM Length L Ch R = 1 ,80927   ,322.2,331.1,348.3
XS GIS Cut Line= 2
 1673347.4362069362022.392524915 1673982.0157403361721.300734292
#Sta/Elev= 30
       0  897.37    31.7  896.85    53.9  892.74      65  886.97      79  884.08
     101  872.51  114.75858.6465   124.7  857.19     138  858.57   160.1  861.44
   186.7  861.37   217.7  873.89   315.1  871.99   359.4  872.68   368.2     874
   399.2  893.28   437.3  897.99   447.9  903.67   465.6  906.08   474.5   912.4
   487.8  924.82   523.2  939.62   542.4  950.19   620.6 1001.29     625 1002.64
   647.5 1003.23   657.5 1005.34   669.3 1010.86   691.4 1025.61   702.4 1031.48
#Mann= 6 ,-1,0
       0      .1       0  114.75    .045       0     138      .1       0
     230     .05       0     340     .08       0     470      .1       0
Bank Sta=114.75,138
XS Rating Curve= 0 ,0
Exp/Cntr(USF)=0,0
Exp/Cntr=0.3,0.1

Type RM Length L Ch R = 1 ,80596   ,102,108.2,110.3
BEGIN DESCRIPTION:
Structure 23 XS 4
END DESCRIPTION:
XS GIS Cut Line= 4
 1673055.8726375361826.1111677361673223.56933101362016.675592181
1673800.97953708362338.7294694931673983.92138455 362641.72690436
#Sta/Elev= 30
       0 1008.76    19.2 1001.99    79.1  967.06   171.9  920.73   268.2  899.63
   307.1  871.23   332.3   871.4   362.9  894.31   419.4  894.53   458.9  887.93
   498.2  869.49   515.8  863.63   625.5  860.52   671.3  862.65   680.4   857.6
   694.2  856.76   707.9  857.63   776.6  862.39   808.7  876.82   836.1   880.4
     853  879.26   868.2  871.96   900.3  872.08   928.8     894   956.5  904.94
  1080.6   990.4  1128.4 1012.43  1166.2 1040.09  1234.8  1082.8  1268.9 1096.38
#Mann= 7 ,-1,0
       0      .1       0  463.84     .07       0  523.84      .1       0
   680.4    .045       0   707.9      .1       0  863.84     .06       0
    1005      .1       0
Bank Sta=680.4,707.9
XS Rating Curve= 0 ,0
Exp/Cntr(USF)=0,0
Exp/Cntr=0.3,0.1

Type RM Length L Ch R = 1 ,80488   ,57.3,56.4,55.7
BEGIN DESCRIPTION:
Structure 23 XS 3
END DESCRIPTION:
XS GIS Cut Line= 6
1672960.14833464361863.0929021971673278.97309778362119.403005897
1673440.26091913362174.4159062041673490.27264668362221.927047377
 1673610.3007928362426.9751303371673859.10913737362733.296961589
#Sta/Elev= 30
       0    1009    15.1  1004.8   103.4  955.02   149.1  933.35   168.3  928.71
   200.2  911.29   248.5  901.94   292.5  898.97   343.8   887.3   369.5  869.96
   395.1  870.89   410.9  881.07   426.2  882.31   543.7  863.84   730.5  861.31
   768.3  856.29   783.6  855.68   789.6   856.3   804.4  862.61     860  863.15
   888.9  869.22   910.9  881.65     962  885.91   984.8  902.71  1042.8   958.1
  1092.8   993.3  1135.4 1013.52  1209.4  1065.6  1243.8 1085.31    1286 1100.81
#Mann= 7 ,-1,0
       0      .1       0  496.87     .07       0  609.55      .1       0
   768.3    .045       0   789.6      .1       0  884.95     .06       0
 1011.39      .1       0
Bank Sta=768.3,789.6
XS Rating Curve= 0 ,0
Exp/Cntr(USF)=0,0
Exp/Cntr=0.8,0.6

Type RM Length L Ch R = 1 ,80431   ,284.8,289.6,288.6
BEGIN DESCRIPTION:
Structure 23 XS 2
END DESCRIPTION:
XS GIS Cut Line= 6
1672906.38572752361915.6052161261673205.20579964362170.665026637
 1673298.9777888362183.1679585251673378.99655288362215.675581433
1673440.26091913362268.1878953621673815.34887576362762.053704931
#Sta/Elev= 30
       0  987.27    33.1  973.31    75.4  949.58    87.7  946.66   163.6  909.15
   207.4  898.32   223.2  890.84   297.2  867.66     365  865.92   407.9  870.65
   436.3  867.95   448.3  862.44   464.4  860.47   745.9  861.09   759.6  860.55
   771.3  856.13   776.6  855.59   795.8856.0992   810.7  861.41     852  861.71
   885.2  865.98   910.6  883.31   969.5  889.54   982.1  899.67   997.1  919.78
  1088.7  990.09  1134.5 1010.84  1210.8 1061.95  1246.4 1082.27  1278.9  1095.4
#Mann= 7 ,-1,0
       0      .1       0  557.47     .07       0  583.84      .1       0
   771.3    .045       0   795.8      .1       0   851.2     .06       0
 1022.16      .1       0
Bank Sta=771.3,795.8
XS Rating Curve= 0 ,0
Exp/Cntr(USF)=0,0
Exp/Cntr=0.3,0.1

Type RM Length L Ch R = 1 ,80142   ,620.7,636.2,641
BEGIN DESCRIPTION:
Structure 23 XS 1
END DESCRIPTION:
XS GIS Cut Line= 5
1672830.63073863361945.5986395761672989.82121396362122.070806185
1673143.71314571362299.4446178691673416.11729073362676.802239413
1673704.10856372362923.129945413
#Sta/Elev= 30
       0  980.37    41.7  964.77    95.5  932.93   127.9  921.63   147.6  909.53
   199.3   896.2   223.2  884.62   252.4  864.07   267.4  859.97   408.3  859.86
   452.8  869.28   488.6  858.71     740  859.47   751.5  856.61   765.8  855.38
     782 856.511   799.4   865.5   828.8   892.8     834  895.01   922.8  900.78
   931.1  913.96   943.6  944.81   949.8  954.47     956  959.33  1043.2  997.88
  1106.3 1015.56  1147.6  1039.2  1243.2  1082.4  1290.6 1100.81  1316.9 1107.71
#Mann= 8 ,-1,0
       0      .1       0  492.49     .05       0  622.49      .1       0
   751.5    .045       0     782      .1       0  842.49     .07       0
  862.49     .06       0   997.9      .1       0
#XS Ineff= 2 , 0
           450.9  939.22
Permanent Ineff=
       F       F
Bank Sta=751.5,782
XS Rating Curve= 0 ,0
Exp/Cntr(USF)=0,0
Exp/Cntr=0.3,0.1

Type RM Length L Ch R = 1 ,79505   ,501.7,497.9,483.8
XS GIS Cut Line= 6
 1672547.7396041362037.3164531851672525.04630494362258.185549852
1672717.17182192362556.8923104261672695.23649834362828.947212502
1672714.35096142363027.9044917521672766.57231367363329.671604753
#Sta/Elev= 30
       0  977.41   131.9   915.5   184.2  899.29   200.3  888.85   216.4  870.28
   234.3  857.47   503.8  854.79   529.2  856.89   557.7  864.85621.9697853.1593
   633.2  851.71649.3597853.1979   701.7   857.9   713.8  863.31   750.2  889.67
   790.2   891.6   810.2  897.22   830.2  911.42     843  925.77   898.3  960.69
   930.4  973.24   982.7  984.55  1018.9 1004.55  1059.2 1014.83  1136.1 1071.84
  1209.1 1119.97    1266 1148.75  1282.1 1153.12    1319 1179.03  1356.8 1198.18
#Mann= 7 ,-1,0
       0      .1       0  292.03    .025       0  492.03      .1       0
621.9697    .045       0649.3597      .1       0  738.66     .06       0
  837.82      .1       0
#XS Ineff= 2 , 0
          562.62  917.59
Permanent Ineff=
       F       F
Bank Sta=621.9697,649.3597
XS Rating Curve= 0 ,0
Exp/Cntr(USF)=0,0
Exp/Cntr=0.3,0.1

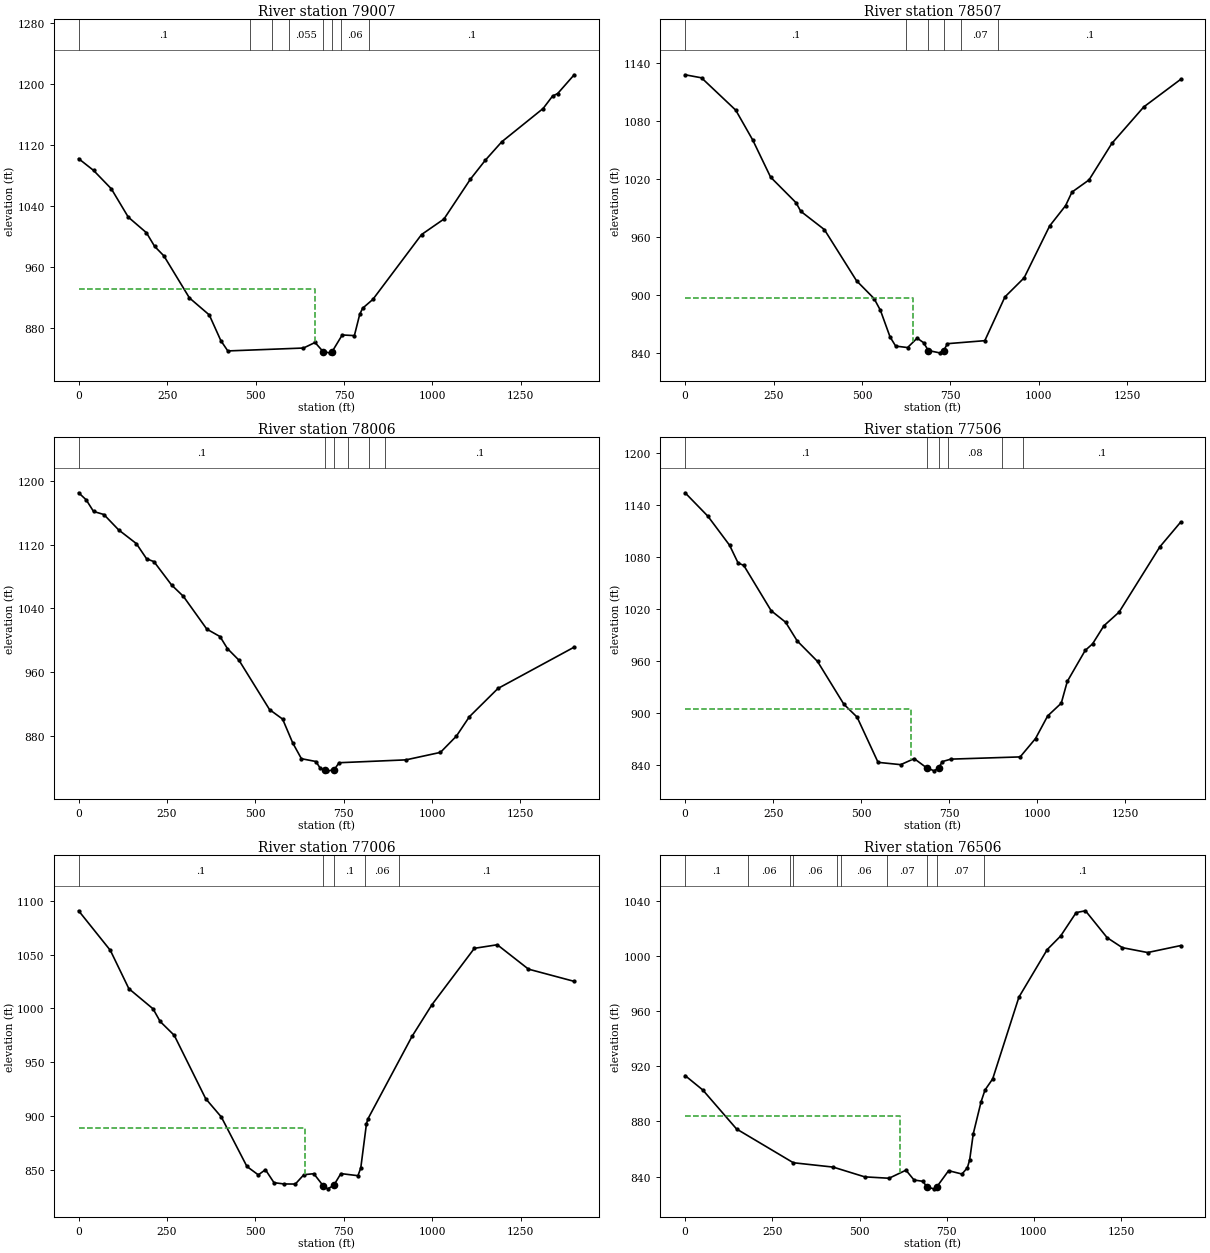
Type RM Length L Ch R = 1 ,79007   ,499.4,500,501.3
XS GIS Cut Line= 6
1671897.30863225362204.3976085931672000.05481784362374.620365262
1672194.64760451362697.0068595861672369.05375175362985.951491669
1672569.70197251 363318.370446251672620.42496817363404.102230176
#Sta/Elev= 30
       0 1102.09    42.2 1086.66    92.5 1062.47   140.3 1025.36   191.5 1004.92
   214.8  986.95   241.1   974.4   313.2  919.25   369.3   896.9     402  863.18
   421.7  849.64   635.6  853.45   668.3  860.74   691.6  848.49   710.3  847.14
     716  848.25   745.1  870.61   779.5  869.77   794.6  897.69   802.7  905.66
   831.8  917.33   969.4 1002.46  1032.7 1022.82  1107.5 1075.17  1149.5 1099.97
  1196.2 1124.27    1313 1167.95  1339.6 1184.21  1354.2 1187.62  1400.8 1212.23
#Mann= 8 ,-1,0
       0      .1       0  484.14     .06       0  547.89     .07       0
  595.39    .055       0   691.6    .045       0     716     .07       0
  740.39     .06       0  820.39      .1       0
#XS Ineff= 2 , 0
          667.15  931.12
Permanent Ineff=
       F       F
Bank Sta=691.6,716
XS Rating Curve= 0 ,0
Exp/Cntr(USF)=0,0
Exp/Cntr=0.3,0.1

Type RM Length L Ch R = 1 ,78507   ,498.2,501.4,505.8
XS GIS Cut Line= 6
1671499.32878518362416.5730372521671543.98223917362505.626993001
1671588.55990592362594.2800309211671632.98599817362682.130905092
1671677.10861334362768.3777798411672142.59980834363660.926519677
#Sta/Elev= 30
       0 1127.69    46.4 1124.55   143.2 1091.13   191.3 1060.23   241.7 1021.95
   313.5  995.58     327  986.67   393.6  967.81   484.6  914.92   534.2  896.54
   552.3  884.23   579.3  856.94   595.2  847.43   628.9  845.91     656  855.64
   674.1  850.94   687.6  842.84   719.2  840.45   730.8  842.74   741.7  849.92
   847.2  853.02   904.1  898.22   958.3  917.89  1030.4  971.46  1075.6  992.53
  1093.6 1006.49  1141.8 1019.06  1206.4 1056.82  1296.6 1094.49  1400.8 1122.94
#Mann= 6 ,-1,0
       0      .1       0  625.42    .055       0   687.6    .045       0
   730.8    .055       0  780.42     .07       0  885.42      .1       0
#XS Ineff= 2 , 0
          645.51  897.35
Permanent Ineff=
       F       F
Bank Sta=687.6,730.8
XS Rating Curve= 0 ,0
Exp/Cntr(USF)=0,0
Exp/Cntr=0.3,0.1

Type RM Length L Ch R = 1 ,78006   ,489.4,500.1,508.7
XS GIS Cut Line= 6
1671184.02167301362568.0596109181671268.01330292362854.668617755
1671293.81804134362948.1841787551671316.96432051363039.077697754
1671336.98199701363124.2638790911671516.03150767363929.999800429
#Sta/Elev= 30
       0  1184.7    21.4 1175.87    42.2 1161.35    71.4 1157.53   113.1 1138.34
   163.2  1121.2   192.4 1102.12   213.2 1098.58   263.1 1069.34   296.4  1055.2
   362.8 1014.18   400.2 1004.84   420.9  989.93   453.8  975.27   540.3  913.53
   577.3  901.63   605.9  871.81   630.5  852.11   671.5  848.61   683.8  840.15
   696.1  837.98   704.3  836.93  722.58838.0362   737.1  847.08   926.2  850.65
  1023.9  860.01    1069   880.3  1105.8  904.58  1186.6  939.93  1402.4  991.64
#Mann= 6 ,-1,0
       0      .1       0   696.1    .045       0  722.58      .1       0
  761.98     .06       0  821.98     .07       0  866.98      .1       0
Bank Sta=696.1,722.58
XS Rating Curve= 0 ,0
Exp/Cntr(USF)=0,0
Exp/Cntr=0.3,0.1

Type RM Length L Ch R = 1 ,77506   ,505.9,500.2,496.2
XS GIS Cut Line= 6
1671061.03963551362584.9683697521670999.40491626362879.825063512
1670948.36072701363065.4178681671670723.09050825 363638.50792934
1670693.22114542363732.4972426741670643.32459167363926.075923756
#Sta/Elev= 30
       0 1154.47    64.8 1127.41   126.5 1093.85   150.5 1073.51   166.8 1070.61
   244.6 1018.34   285.6  1005.1   318.5  983.52   376.3  959.85   451.1  910.46
   488.7  895.59   548.3  843.38   612.7  840.72     651  847.67   686.1  837.15
   707.7  833.58   720.6  837.07   730.8  844.24   755.2  847.09   952.1  849.66
   995.7  870.82  1030.3  896.96  1068.9  911.66    1086  936.76  1136.9  972.55
  1157.9  980.15    1190 1000.97  1233.2 1016.76    1349 1092.08  1408.1 1120.59
#Mann= 6 ,-1,0
       0      .1       0   686.1    .045       0   720.6      .1       0
  746.49     .08       0  901.49     .06       0  958.98      .1       0
#XS Ineff= 2 , 0
          641.84  905.52
Permanent Ineff=
       F       F
Bank Sta=686.1,720.6
XS Rating Curve= 0 ,0
Exp/Cntr(USF)=0,0
Exp/Cntr=0.3,0.1

Type RM Length L Ch R = 1 ,77006   ,508,500,482.6
XS GIS Cut Line= 6
1670453.11893535362499.4065330031670400.20401493362984.444604918
  1670333.854082363596.4643782531670326.72351883363694.704667345
1670321.36427759363793.9255975041670316.47353934363893.619295761
#Sta/Elev= 30
       0 1090.68    89.7 1053.84     142 1018.26   210.4  999.51   230.5  987.75
   270.4  974.85   359.2  915.99   403.5  898.92   475.9  852.91   508.1   845.1
   528.2  849.92   552.4  837.86   580.5  836.66   612.7  836.57   636.9  845.28
     665   846.2  691.02835.1795   704.4  832.12   721.4  835.34   741.5  846.29
   789.8  844.35   797.8  851.55   813.9  892.66   817.9  897.11   942.6  973.83
     999 1003.34    1119 1055.77  1183.8 1059.09    1272  1036.4  1401.2 1025.05
#Mann= 5 ,-1,0
       0      .1       0  691.02    .045       0   721.4      .1       0
  810.42     .06       0  905.42      .1       0
#XS Ineff= 2 , 0
          639.54  888.45
Permanent Ineff=
       F       F
Bank Sta=691.02,721.4
XS Rating Curve= 0 ,0
Exp/Cntr(USF)=0,0
Exp/Cntr=0.3,0.1

Type RM Length L Ch R = 1 ,76506   ,502.5,500,494.2
XS GIS Cut Line= 6
1669434.32930626362768.476204842 1669623.1963826363000.863535345
1670049.72276051363444.8327917611670103.44640633363523.202713758
1670151.63561442363610.4249802531670274.04809926363895.867322758
#Sta/Elev= 30
       0  913.21    50.7  902.78   147.6  874.51   310.3  850.07   424.4  846.92
   514.9  839.85   584.7  838.84   633.2  844.68   656.4  837.56   681.8  836.61
   693.2  832.53     713  831.17   721.5  832.57   755.4  844.32   793.8  841.89
   809.2  846.44   815.8  852.16   826.1  871.05   848.7  894.41   859.8  902.77
   881.8  910.82     957  970.03  1038.2 1004.48  1076.5 1014.26  1121.1 1031.26
  1147.8 1032.56  1209.9 1013.08  1253.5 1005.85    1326 1002.32  1420.6 1007.36
#Mann= 10 ,-1,0
       0      .1       0  180.52     .06       0  299.52      .1       0
  309.52     .06       0  436.44     .05       0  446.44     .06       0
  577.71     .07       0   693.2    .045       0   721.5     .07       0
  857.71      .1       0
#XS Ineff= 2 , 0
          616.53  883.62
Permanent Ineff=
       F       F
Bank Sta=693.2,721.5
XS Rating Curve= 0 ,0
Exp/Cntr(USF)=0,0
Exp/Cntr=0.3,0.1