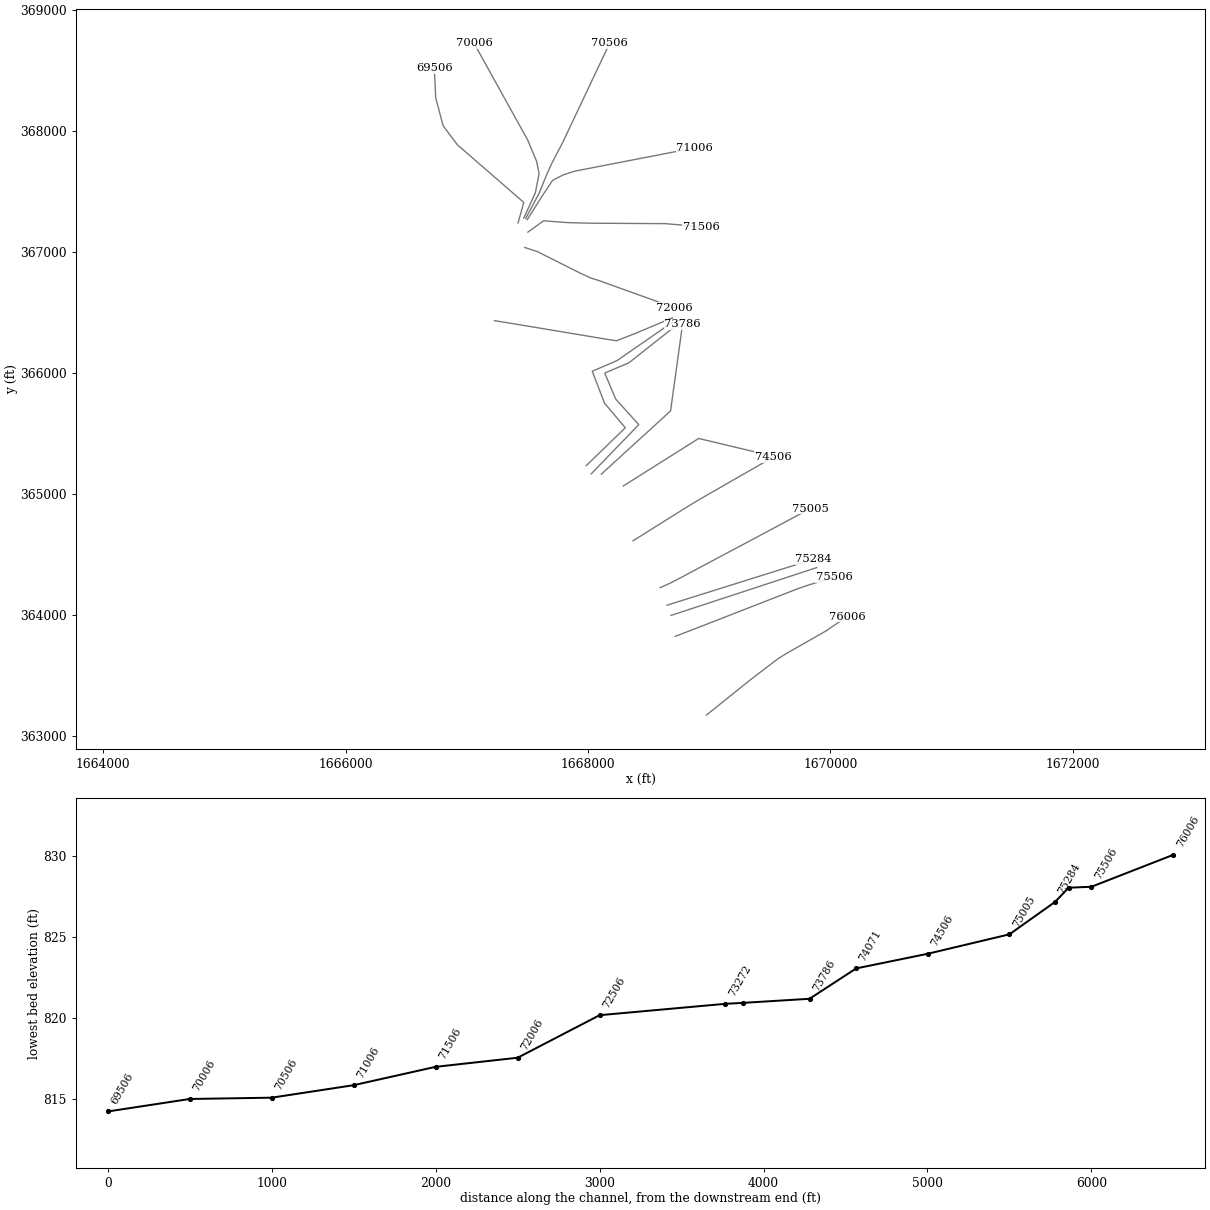
HEC-RAS study SFFSHGCK.prj: SFFSHGCK

--- SFFSHGCK.g01 (geometry) --- (continued)

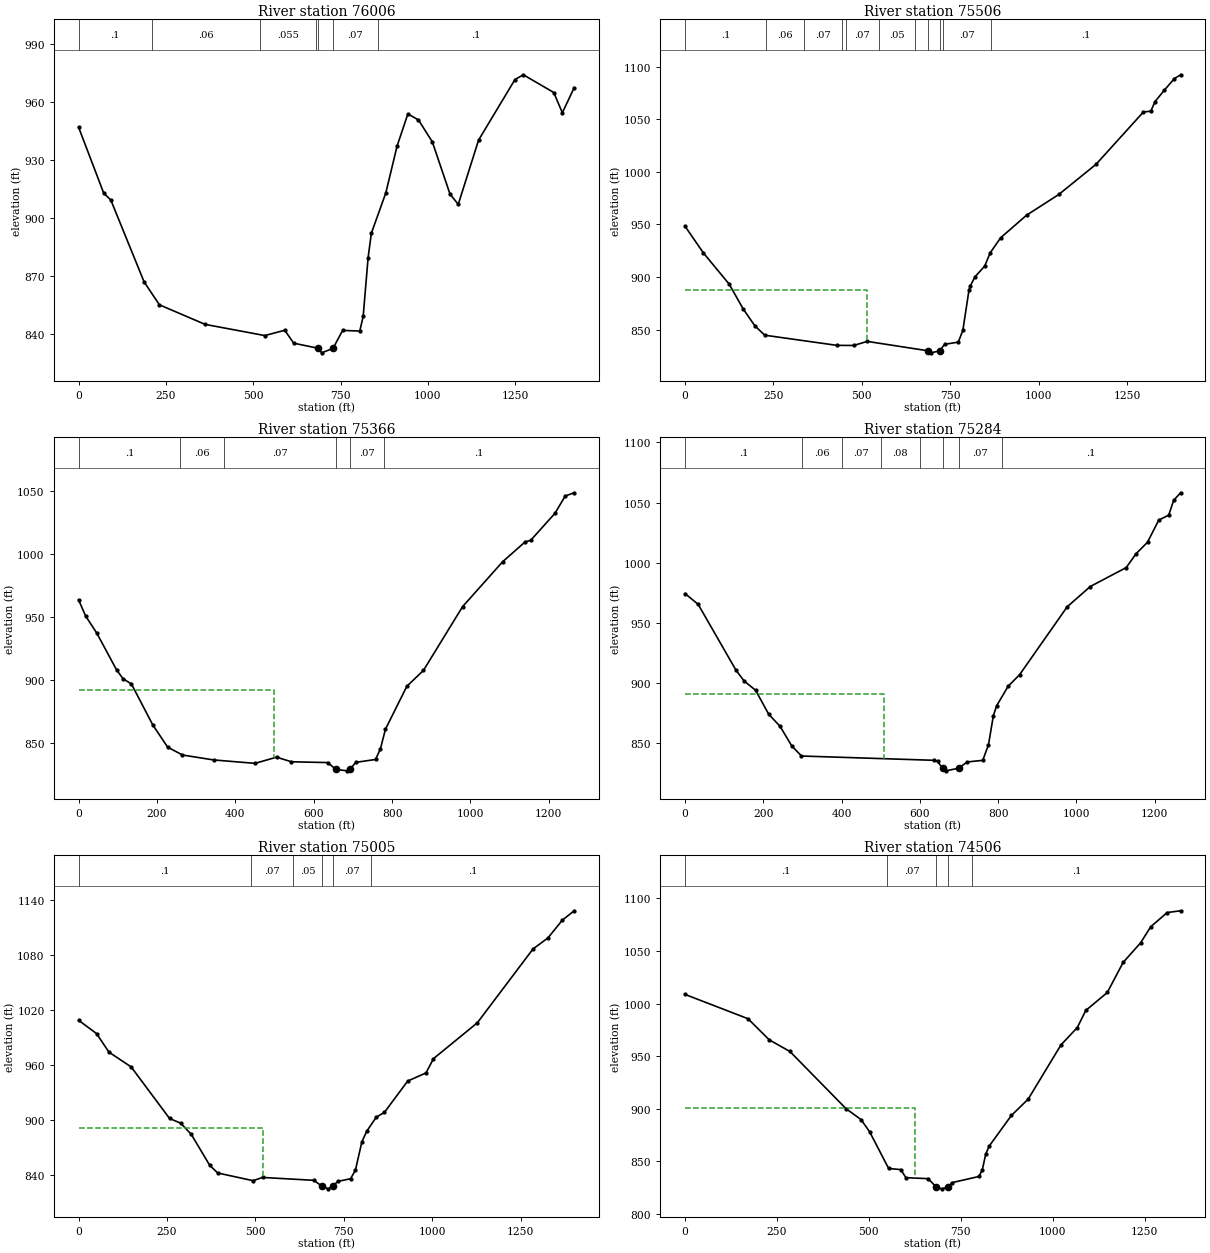
Type RM Length L Ch R = 1 ,76006   ,503,500,490.2
XS GIS Cut Line= 6
1668976.31283385363174.9363499281669356.99547142363480.376355842
1669565.84708785 363639.407205761669629.69472918363679.816573754
1669961.94636126363869.1206570861670135.77672225363987.628950253
#Sta/Elev= 30
       0  946.73    71.7  912.75    92.2  909.11   187.5  866.75   231.4   854.9
   362.3  844.78   533.1     839   590.2  841.75   615.9  835.05  686.87832.3895
   695.9  830.06   728.4  832.36     756  841.66   805.1  841.34   814.8   848.9
   828.9  879.27   838.2  891.93   879.7  912.85     912  937.11   942.8  953.69
   973.2  950.55  1012.9  939.19  1063.5  912.17  1087.1   906.9  1145.3  940.15
  1249.4  971.46  1273.4  973.93  1360.6  964.75  1385.1  954.27    1419  967.24
#Mann= 7 ,-1,0
       0      .1       0  208.89     .06       0  518.07    .055       0
  680.59      .1       0  686.87    .045       0   728.4     .07       0
  856.15      .1       0
Bank Sta=686.87,728.4
XS Rating Curve= 0 ,0
Exp/Cntr(USF)=0,0
Exp/Cntr=0.3,0.1

Type RM Length L Ch R = 1 ,75506   ,140.1,139.6,137.7
BEGIN DESCRIPTION:
Structure 22 XS 4
END DESCRIPTION:
XS GIS Cut Line= 6
1668719.92883217363825.289051846 1668905.3667815363896.961480677
1669658.01258592364190.3647652571669748.34869134364225.353540421
1669842.03190292364256.0582034291670032.84188876364313.923245177
#Sta/Elev= 30
       0  948.21    51.7     923   124.6  893.37   164.3  869.78   197.5  853.63
   225.3  844.84   429.3  835.19   476.5  835.08   515.2  838.95   686.9  830.04
   695.5  828.09   719.6  829.95   734.1  836.18   772.7  838.28   785.6  849.54
   802.8  887.47   807.1  891.96     820  900.35   847.4  910.49   862.9  923.09
   892.5   937.4   965.9  958.82  1056.9  978.48  1162.2 1007.12  1296.2 1056.81
  1317.1 1057.56  1329.2 1066.73  1354.7 1077.26    1384 1088.58  1401.5 1092.15
#Mann= 11 ,-1,0
       0      .1       0  228.81     .06       0  337.24     .07       0
  444.12      .1       0  454.12     .07       0  547.87     .05       0
  650.37      .1       0   686.9    .045       0   719.6      .1       0
  730.37     .07       0  865.37      .1       0
#XS Ineff= 2 , 0
          514.16  887.41
Permanent Ineff=
       F       F
Bank Sta=686.9,719.6
XS Rating Curve= 0 ,0
Exp/Cntr(USF)=0,0
Exp/Cntr=0.3,0.1

Type RM Length L Ch R = 1 ,75366   ,81.9,81.9,81.6
BEGIN DESCRIPTION:
Structure 22 XS 3
END DESCRIPTION:
XS GIS Cut Line= 2
 1668684.1734133363998.0101984811669885.84408918364392.547160274
#Sta/Elev= 30
       0  963.36    17.8  950.66    46.2  937.13    96.8     908   113.6  900.89
   134.7  896.84   189.4   864.3   227.3  846.78     265  840.57   344.3  836.66
   450.4  833.95   505.1  838.86     543  835.21   635.7  834.57   656.7  829.17
   685.4  828.03   692.9  829.31   707.2  834.73   757.8  837.04   770.4  845.57
     783   860.9   837.7  894.98   880.1  907.55     980  958.05  1081.9  993.49
  1139.8 1009.38  1153.5 1010.46  1215.9 1031.97  1241.9 1045.64  1264.8  1048.2
#Mann= 6 ,-1,0
       0      .1       0     260     .06       0     370     .07       0
   656.7    .045       0   692.9     .07       0     780      .1       0
#XS Ineff= 2 , 0
           498.2  891.81
Permanent Ineff=
       F       F
Bank Sta=656.7,692.9
XS Rating Curve= 0 ,0
Exp/Cntr(USF)=0,0
Exp/Cntr=0.3,0.1

Type RM Length L Ch R = 1 ,75284   ,276.5,278.8,281.8
BEGIN DESCRIPTION:
Structure 22 XS 2
END DESCRIPTION:
XS GIS Cut Line= 2
1668652.22147625364082.7522923871669860.83822541364462.007892984
#Sta/Elev= 30
       0  974.44    33.4  965.48   129.8  910.94   150.8   901.8   180.2  894.09
   213.7  874.22     243  864.03   272.4  847.99   297.5  839.48   637.1   835.9
   645.5  834.93   658.1  829.25   666.5  827.16  699.23829.3502     721  834.52
   760.8  835.89   775.5  848.77     788  873.03   796.4  881.22   825.8  897.46
   855.1  907.06   976.7  963.45  1035.7   980.3  1127.6  996.03  1152.8 1007.53
    1182 1017.09  1210.7 1035.46  1236.3 1039.64    1249 1052.04  1266.7 1058.18
#Mann= 8 ,-1,0
       0      .1       0     300     .06       0     400     .07       0
     500     .08       0     600     .07       0   658.1    .045       0
  699.23     .07       0     810      .1       0
#XS Ineff= 2 , 0
          508.27  891.03
Permanent Ineff=
       F       F
Bank Sta=658.1,699.23
XS Rating Curve= 0 ,0
Exp/Cntr(USF)=0,0
Exp/Cntr=0.3,0.1

Type RM Length L Ch R = 1 ,75005   ,499.3,499.8,500.3
BEGIN DESCRIPTION:
Structure 22 XS 1
END DESCRIPTION:
XS GIS Cut Line= 6
1668593.94811301364226.8046530041668685.33375701364267.933179677
1668773.23646834364314.1975228341669105.70266692364491.701761007
1669260.40248875364573.6356522591669833.71958359 364880.08156167
#Sta/Elev= 30
       0 1008.56    50.6  994.12    85.7  973.94   148.6   957.8   257.2  901.74
     289  896.53   318.7   884.4   370.6  850.85   393.3  842.43   493.2  834.03
   520.2  837.56   665.2  834.43   688.3  828.03   706.4  825.16  718.92828.1774
   733.1  833.24   769.3  836.16     783   845.7   801.1  876.24   814.7  887.74
   842.1  903.27   864.6  908.23   930.8  942.47   982.5  951.28  1003.7  966.84
  1127.6 1005.81  1285.4 1086.27  1327.2 1098.09  1368.2 1117.55  1401.6 1127.73
#Mann= 6 ,-1,0
       0      .1       0  488.86     .07       0  606.43     .05       0
   688.3    .045       0  718.92     .07       0  826.47      .1       0
#XS Ineff= 2 , 0
          522.21  891.12
Permanent Ineff=
       F       F
Bank Sta=688.3,718.92
XS Rating Curve= 0 ,0
Exp/Cntr(USF)=0,0
Exp/Cntr=0.3,0.1

Type RM Length L Ch R = 1 ,74506   ,433.6,435.2,435.1
XS GIS Cut Line= 6
1668370.95085558364613.8842594181668784.46216768364873.544173166
1668858.95873784364919.5266927631668923.27750684 364958.13061817
1669487.74422568365282.0036580861669527.66997499365305.435540896
#Sta/Elev= 30
       0 1008.77     171  985.71     229  965.58     285  954.58   437.9  900.13
   478.6  889.79   501.8  878.27   553.7   843.3   586.5  842.26   600.7  834.59
     661  833.63  683.58825.5283   697.9  823.96   716.4  825.62   725.6  829.82
   799.4  835.72   808.4     842   817.8  857.01     827  864.52   887.6  893.76
   933.1   909.2  1022.4  960.78  1066.9  977.33  1089.8  993.51  1148.4 1010.62
  1191.4 1039.18  1239.3 1057.96  1266.5 1073.13  1311.3 1086.63  1347.9 1088.31
#Mann= 5 ,-1,0
       0      .1       0  548.28     .07       0  683.58    .045       0
   716.4     .07       0  780.84      .1       0
#XS Ineff= 2 , 0
          625.02  900.34
Permanent Ineff=
       F       F
Bank Sta=683.58,716.4
XS Rating Curve= 0 ,0
Exp/Cntr(USF)=0,0
Exp/Cntr=0.3,0.1

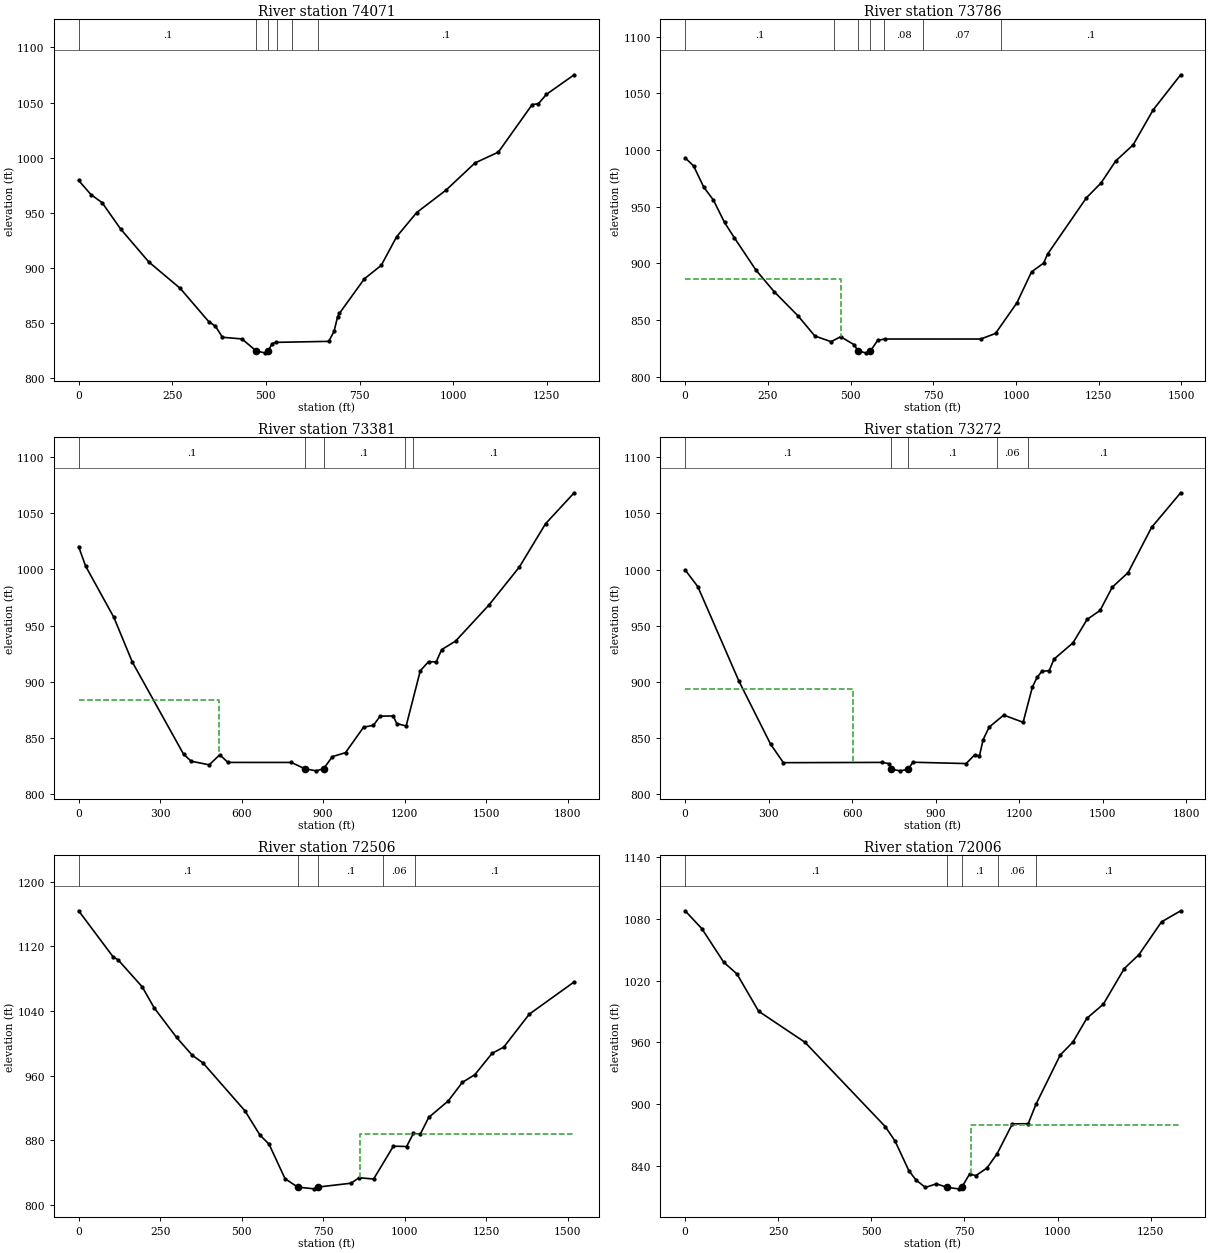
Type RM Length L Ch R = 1 ,74071   ,281.4,284.3,286.5
XS GIS Cut Line= 3
1668291.31151047365066.9755182321668912.87509576 365459.08338746
1669485.06213456365322.571758914
#Sta/Elev= 30
       0  979.38    32.9  966.59    62.9  959.18   111.9  935.45   187.3  905.49
   271.4  881.46   347.8   851.2   365.1  847.31     384  837.18   436.1  835.68
   474.4  824.68   497.5  823.06   506.3   824.7   516.5  831.44   527.7  832.57
   667.8  833.47     682   842.5   691.4  855.69   696.2  858.78   762.9  890.15
   808.1  902.41   849.3  928.44   902.7  950.28   980.9  970.57  1058.4  995.24
  1120.7 1005.03  1211.1 1048.19  1227.6 1048.92  1248.9 1057.38  1323.2 1075.19
#Mann= 6 ,-1,0
       0      .1       0   474.4    .045       0   506.3      .1       0
     530     .08       0     570     .07       0     640      .1       0
Bank Sta=474.4,506.3
XS Rating Curve= 0 ,0
Exp/Cntr(USF)=0,0
Exp/Cntr=0.3,0.1

Type RM Length L Ch R = 1 ,73786   ,364.1,405,438.8
BEGIN DESCRIPTION:
Structure 21 XS 4
END DESCRIPTION:
XS GIS Cut Line= 3
1668109.08939878365164.1354914731668680.78267212365686.282014451
1668779.87617283366402.804250363
#Sta/Elev= 30
       0  993.24    25.8  985.96    56.2  967.42    85.4  956.01   119.2  936.15
   148.9  922.66   214.1  894.17   269.5  875.04   342.2   853.5   392.1  836.05
   441.3  831.02     470  835.42   510.7  828.38   522.6  822.88   545.8  821.19
   560.2  822.86   581.9  832.17   602.7  833.38   893.6  833.39   938.1  838.29
  1002.7  865.26  1047.1  892.66  1083.4  900.28  1095.5  908.26  1212.6  957.83
  1257.1  971.01  1301.5  990.45    1354 1004.59  1414.5 1035.43  1497.6 1066.41
#Mann= 7 ,-1,0
       0      .1       0     450     .07       0   522.6    .045       0
   560.2     .07       0     600     .08       0     720     .07       0
  954.25      .1       0
#XS Ineff= 2 , 0
          470.45  886.38
Permanent Ineff=
       F       F
Bank Sta=522.6,560.2
XS Rating Curve= 0 ,0
Exp/Cntr(USF)=0,0
Exp/Cntr=0.5,0.3

Type RM Length L Ch R = 1 ,73381   ,117.7,108.9,109.8
BEGIN DESCRIPTION:
Structure 21 XS 3
END DESCRIPTION:
XS GIS Cut Line= 6
1668026.19387415 365166.99395784 1668418.7565885365572.896181907
1668228.19216406 365784.422693041668137.67406245365998.807670541
1668336.81388599366083.6088394191668746.52739855366407.568360975
#Sta/Elev= 30
       0 1020.03    25.8 1002.73   129.7  957.23   197.6  917.57   386.1  835.84
   413.9  829.53   480.7  826.26   519.7  835.25   549.4  828.41   783.3   828.4
   831.9822.8685   874.5  820.94     902  822.86   934.1  833.55   982.5  837.09
  1048.9  859.67  1085.5  861.42  1109.9  869.52    1158  869.67    1171  862.95
  1205.7  860.76  1257.8  909.81  1288.2  917.89  1316.4  917.69  1336.3  928.56
  1387.8  936.18  1510.2  968.13  1622.4  1001.9  1719.2 1040.48  1824.3 1067.88
#Mann= 5 ,-1,0
       0      .1       0   831.9    .045       0     902      .1       0
 1200.33     .06       0 1230.33      .1       0
#XS Ineff= 2 , 0
          517.61  883.79
Permanent Ineff=
       F       F
Bank Sta=831.9,902
XS Rating Curve= 0 ,0
Exp/Cntr(USF)=0,0
Exp/Cntr=0.3,0.1

Type RM Length L Ch R = 1 ,73272   ,814.6,766.7,676.2
BEGIN DESCRIPTION:
Structure 21 XS 2
END DESCRIPTION:
XS GIS Cut Line= 6
1667985.22252289365234.644328517 1668307.2764002365547.169984607
 1668135.7684182365751.0739187631668034.76927325366014.052824496
 1668238.6732074366101.7124597411668697.93347032366419.955048563
#Sta/Elev= 30
       0  999.71    45.8  984.71   193.5  900.64   307.1  844.61   353.1  828.14
   708.4  828.38   731.8  827.35   740.9  822.27   772.9  820.88   801.6822.1828
   818.1  828.54  1009.7  827.35  1040.1  835.07  1057.5  834.25  1070.6  848.64
  1092.4  859.79  1144.6  870.48  1214.3  864.06  1247.6  895.41  1264.7  904.13
  1281.6  909.37  1307.9  910.04  1325.4  920.29  1393.5  934.77  1444.1  955.58
  1490.8  963.57  1534.6  984.28  1591.6  997.28  1675.8 1037.47  1780.2 1068.27
#Mann= 5 ,-1,0
       0      .1       0   740.9    .045       0   801.6      .1       0
 1119.48     .06       0 1231.43      .1       0
#XS Ineff= 2 , 0
          603.88  893.62
Permanent Ineff=
       F       F
Bank Sta=740.9,801.6
XS Rating Curve= 0 ,0
Exp/Cntr(USF)=0,0
Exp/Cntr=0.3,0.1

Type RM Length L Ch R = 1 ,72506   ,503.7,499.9,488.1
BEGIN DESCRIPTION:
Structure 21 XS 1
END DESCRIPTION:
XS GIS Cut Line= 6
1667227.99316776366432.0430246741667521.30098009366383.539840832
1668128.54943751366282.3310537491668234.60312772366265.550811819
 1668385.1725495366324.3669922031668696.25872759366455.130460236
#Sta/Elev= 30
       0 1163.87   105.5 1107.03   121.8 1102.89   195.1 1069.78   231.2 1044.15
   300.1 1007.44   348.8   985.1   381.2  975.86   510.2  916.48   555.6  886.85
     584  875.26   632.8  832.77  671.76822.3203   721.9  820.18  735.44822.4538
   835.4  827.14   859.8  833.92   904.4  832.29   965.1  872.92  1005.6  872.48
  1026.2  888.59  1047.7  887.85  1073.4  908.43  1133.6  928.97  1176.5  951.79
  1214.9  961.32  1267.6  987.62  1303.5  995.34  1381.7 1036.06  1519.4 1075.94
#Mann= 5 ,-1,0
       0      .1       0  671.76    .045       0  735.44      .1       0
  932.92     .06       0 1030.29      .1       0
#XS Ineff= 2 , 0
                          861.54          888.28
Permanent Ineff=
       F       F
Bank Sta=671.76,735.44
XS Rating Curve= 0 ,0
Exp/Cntr(USF)=0,0
Exp/Cntr=0.3,0.1

Type RM Length L Ch R = 1 ,72006   ,489.4,500.1,504.6
XS GIS Cut Line= 6
1667477.32436201367035.9591396751667580.07842159367002.658681333
1667941.92152992366820.8847666681668024.56604968366783.292322174
1668096.82771617 366760.239874841668709.19689825366539.967021421
#Sta/Elev= 30
       0 1087.99      45  1070.6   103.8 1037.92   139.3  1026.5   197.4  990.29
   321.5   960.2   537.3  878.15   563.7  864.03   600.7  835.25   620.1  826.07
   645.3  818.92   674.6  822.43   704.3  818.92   734.1  817.56   742.6  818.98
   763.8  831.94   780.8  830.41   810.6  837.87     838  851.91   878.6  880.73
   921.1  880.92   942.1  899.87  1007.1  947.69  1041.5  960.45  1078.4  983.36
  1122.8   997.1    1179 1031.75  1218.7 1045.43  1279.1 1077.23  1330.4 1087.91
#Mann= 5 ,-1,0
       0      .1       0   704.3    .045       0   742.6      .1       0
   839.6     .06       0   942.1      .1       0
#XS Ineff= 2 , 0
                          766.93          879.66
Permanent Ineff=
       F       F
Bank Sta=704.3,742.6
XS Rating Curve= 0 ,0
Exp/Cntr(USF)=0,0
Exp/Cntr=0.3,0.1

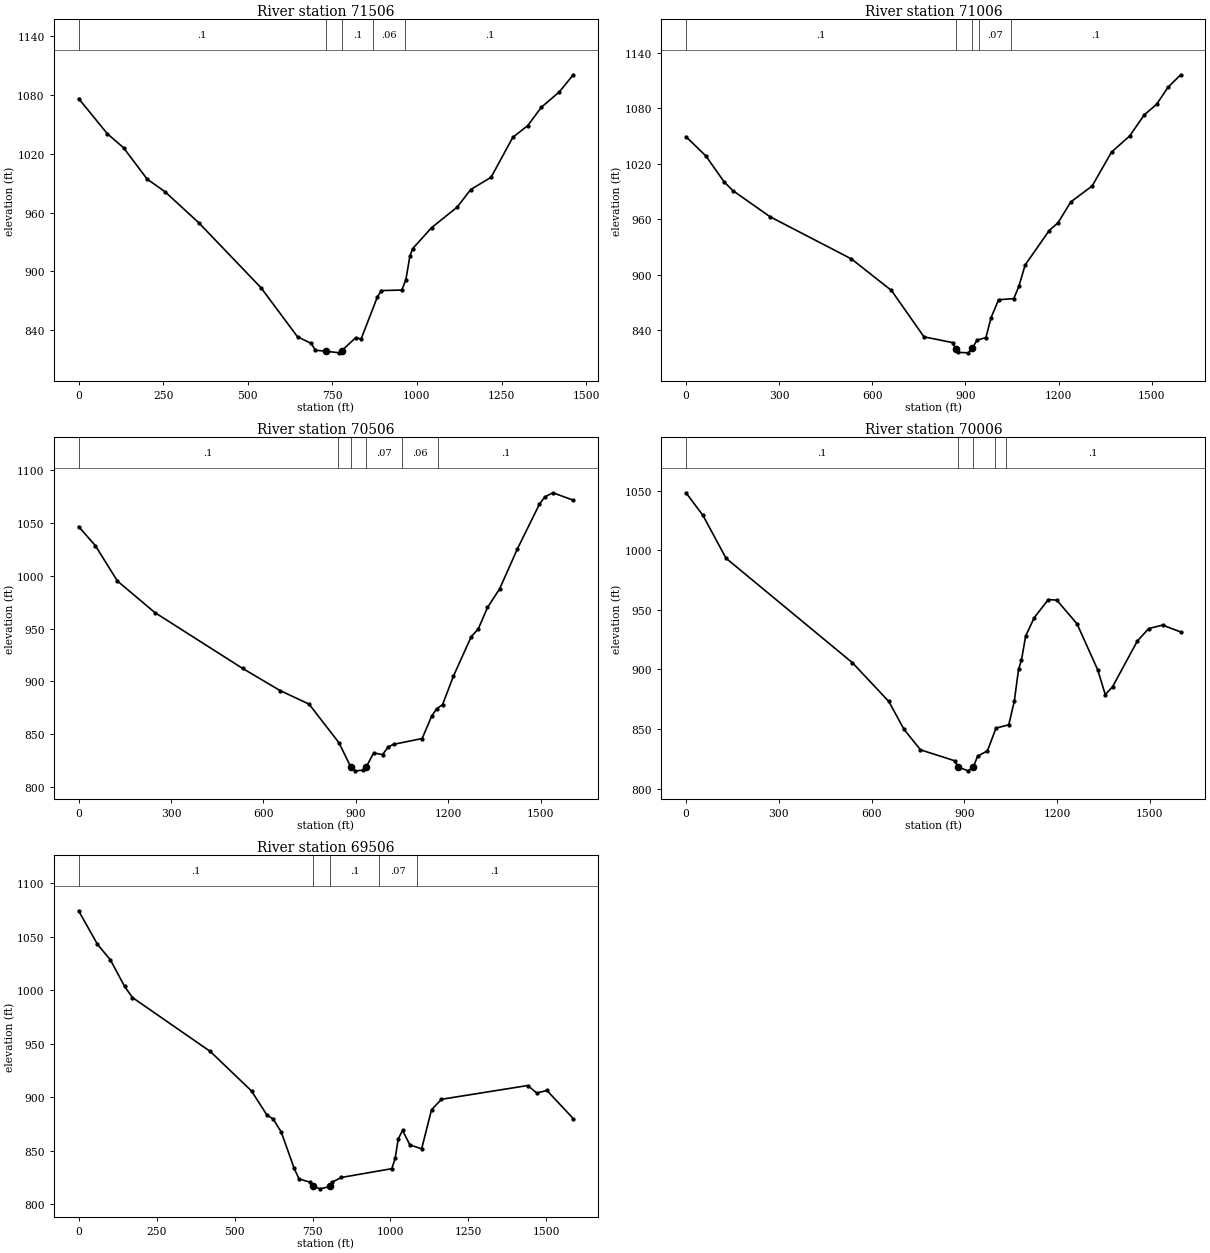
Type RM Length L Ch R = 1 ,71506   ,493.8,500,503.7
XS GIS Cut Line= 6
1667503.91650042367162.6813271791667633.26269843367256.103712499
1667830.91354984367241.1086637531668021.53849667367236.292072341
1668637.16324967367232.5732477611668933.97171117367207.363980591
#Sta/Elev= 30
       0  1076.4    85.1 1040.43     133 1026.13   202.6  994.21   254.8   981.5
     355  949.75   539.1  883.44   647.1  833.35   687.1  826.73   699.9  819.66
   730.4  818.67   771.1     817  777.18818.9785   819.1  832.45   835.1   831.2
   883.1  874.03   895.1   880.5   955.1  881.04   967.1  891.25   979.1  915.36
   987.1  923.14  1043.1   944.6  1119.1  965.67    1159  983.57  1219.2  996.04
  1283.3 1036.77  1327.5 1048.73  1367.7 1067.43  1420.9 1083.19  1462.1  1100.6
#Mann= 5 ,-1,0
       0      .1       0   730.4    .045       0  777.18      .1       0
  871.01     .06       0  966.01      .1       0
Bank Sta=730.4,777.18
XS Rating Curve= 0 ,0
Exp/Cntr(USF)=0,0
Exp/Cntr=0.3,0.1

Type RM Length L Ch R = 1 ,71006   ,477.3,500,526.3
XS GIS Cut Line= 6
1667497.93554126367264.8687868421667621.30045201367460.477975667
1667707.55880967367589.8848690841667798.70659326367636.949407503
1667891.70148601367666.2711992561668879.95475884367857.793782085
#Sta/Elev= 30
       0  1049.2    64.1 1028.37   123.1 1000.29   150.9  990.97   270.8  962.75
   532.8  917.24   661.9  883.17   766.6  833.16   858.8  826.92   868.4  820.44
   876.6  816.37   909.2  815.87  922.09820.5842   937.7  829.62   966.2  832.34
   982.5  853.61    1007   873.2  1055.9  874.35  1072.1  887.61  1092.5  910.65
  1169.9  947.86  1198.5  956.27  1239.2  978.64  1308.5  996.02  1370.7 1032.54
  1428.8 1049.82  1476.5 1072.82  1516.3 1084.22  1552.9 1102.58  1593.5 1115.97
#Mann= 5 ,-1,0
       0      .1       0   868.4    .045       0  922.09      .1       0
  943.12     .07       0 1048.12      .1       0
Bank Sta=868.4,922.09
XS Rating Curve= 0 ,0
Exp/Cntr(USF)=0,0
Exp/Cntr=0.3,0.1

Type RM Length L Ch R = 1 ,70506   ,479.6,500,527.1
XS GIS Cut Line= 6
1667485.66063142367276.4858895841667596.75063235 367483.71250926
1667658.45884226367636.3536081761667700.50731459367729.887213752
1667788.90182284367898.9557732491668179.10117367368724.252022922
#Sta/Elev= 30
       0 1046.83    54.5 1028.71   125.9  995.19   247.6  965.25   532.5  912.25
   654.4   891.2   748.1  878.42   845.5  841.67  883.37818.8769   898.5   815.1
   924.9  815.76     934  818.98     958  832.07     987  830.49  1004.7  837.78
  1022.4  840.21  1115.3  845.75  1146.3     867  1162.3  873.98  1181.6   877.9
    1217     905  1274.5  942.31  1297.5  949.66  1327.5  970.06  1366.6  987.58
  1424.9 1025.83  1495.7  1067.8  1513.4 1074.97    1540 1078.86    1606 1071.82
#Mann= 6 ,-1,0
       0      .1       0  840.61     .07       0  883.37    .045       0
     934     .07       0 1050.61     .06       0 1168.11      .1       0
Bank Sta=883.37,934
XS Rating Curve= 0 ,0
Exp/Cntr(USF)=0,0
Exp/Cntr=0.3,0.1

Type RM Length L Ch R = 1 ,70006   ,491.4,500,509.9
XS GIS Cut Line= 6
1667470.04452093367278.6886410861667565.51873942367488.118012249
1667595.99505642367645.1646141711667575.57941484367747.509225756
1667501.41092801367924.3769822571667058.99022493368722.896382585
#Sta/Elev= 30
       0 1048.11    54.8 1029.18   129.5  993.22   538.3   905.6   655.7  873.18
   704.9  849.79   758.2  832.63   869.6  823.39   878.8  818.36     912  815.02
     929  818.18   942.7  827.26   974.7  831.81  1002.2  850.81  1043.6  853.65
  1061.6  873.52  1075.3  900.31  1084.5  907.64  1098.2     928  1125.6   943.3
  1171.4   958.6  1198.8   958.1  1264.3  938.27  1331.4  899.54  1355.5  878.95
    1379  885.41  1459.5  923.93  1496.1  934.29  1540.9  937.19  1599.4  931.45
#Mann= 5 ,-1,0
       0      .1       0   878.8    .045       0     929     .05       0
  998.96     .07       0 1033.96      .1       0
Bank Sta=878.8,929
XS Rating Curve= 0 ,0
Exp/Cntr(USF)=0,0
Exp/Cntr=0.3,0.1

Type RM Length L Ch R = 1 ,69506   ,531,500,465.9
XS GIS Cut Line= 6
 1667422.3185665 367238.394102261667470.06650251367407.528934583
1666921.43571001367884.2189260871666804.45497283368040.764872834
1666743.13816634 368271.658111841666731.52467251368517.660900667
#Sta/Elev= 30
       0  1074.1    60.4 1042.83     102 1028.18   147.7 1003.34   172.6  993.04
     422  942.68   554.4  905.74   603.3  883.43   623.7   879.5   649.5  867.55
   691.3  833.35   706.8   823.5   743.3  820.34  752.97816.5524   774.3  814.25
   805.7  816.44   811.4   820.2   842.4  824.89  1004.4   833.1  1015.1  843.02
  1024.9  860.87  1038.7  868.91  1062.2  855.28  1099.9  851.67  1131.6  888.18
  1163.5  897.94    1440  910.81    1469  903.81  1501.7  906.16  1586.1  879.87
#Mann= 5 ,-1,0
       0      .1       0  752.97    .045       0   805.7      .1       0
  963.88     .07       0 1084.99      .1       0
Bank Sta=752.97,805.7
XS Rating Curve= 0 ,0
Exp/Cntr(USF)=0,0
Exp/Cntr=0.3,0.1