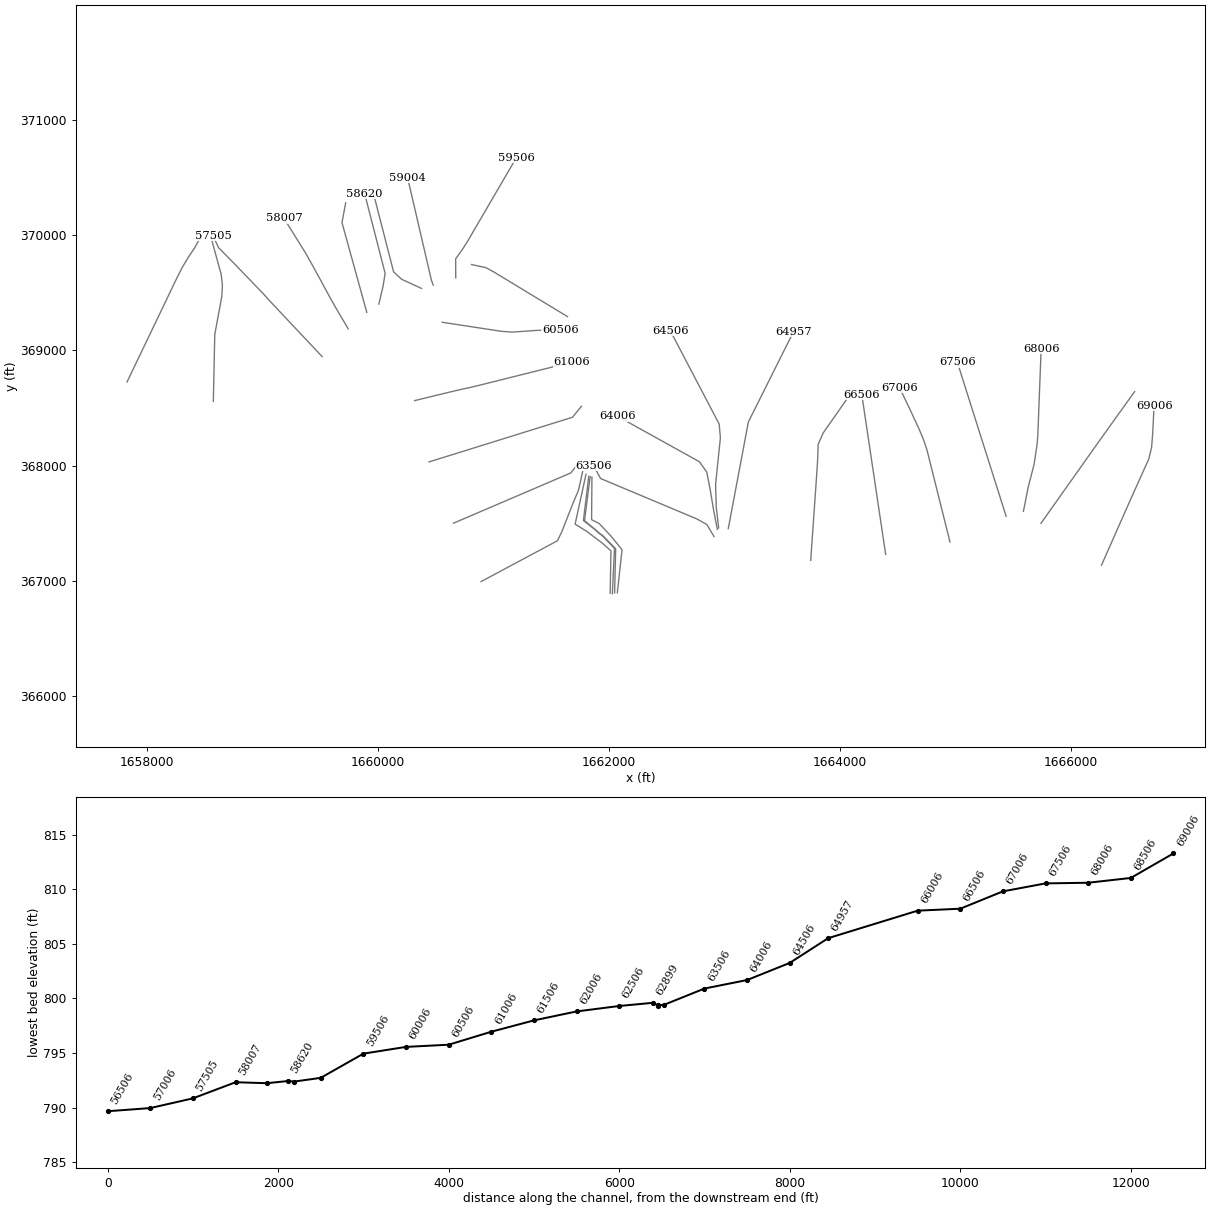
HEC-RAS study SFFSHGCK.prj: SFFSHGCK

--- SFFSHGCK.g01 (geometry) --- (continued)

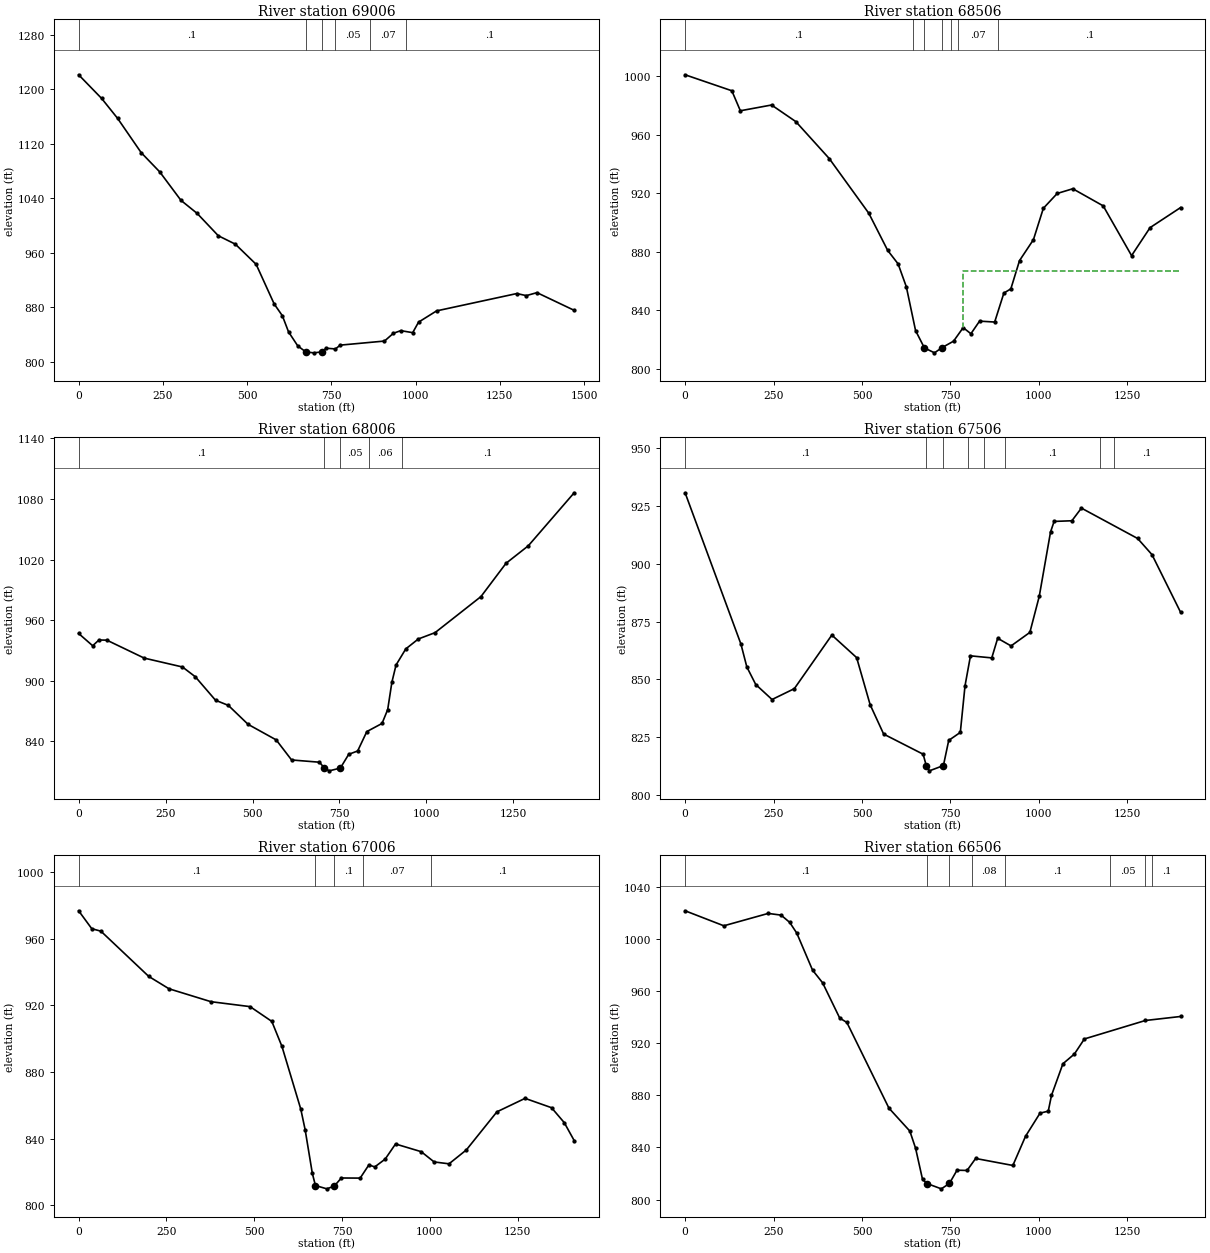
Type RM Length L Ch R = 1 ,69006   ,505,500,496
XS GIS Cut Line= 6
1666268.42487693367138.7637240891666531.44961335367733.405579418
 1666677.7337696368058.3580135111666702.35609567368159.891603082
1666711.45778351368276.0563970061666723.60474084368518.760307923
#Sta/Elev= 30
       0 1221.41    68.4 1186.62   115.7  1157.4   185.6 1107.15   240.7 1078.88
   303.7  1037.1   351.8 1017.92   414.5  985.16   465.1  972.79   526.8  943.19
   580.3  885.06   604.6  867.77     623     844   650.2  823.55   674.3  814.59
   697.5   813.3  721.32814.6077   734.8  820.14     762  818.98   776.4  824.61
   907.7   830.6   934.1  842.01   956.1  845.87   991.4  842.91  1008.8  858.36
  1062.3  874.87  1300.2  900.31  1328.6  897.29  1360.2  901.65  1470.6  875.69
#Mann= 6 ,-1,0
       0      .1       0   674.3    .045       0  721.32      .1       0
  760.22     .05       0  865.24     .07       0  972.76      .1       0
Bank Sta=674.3,721.32
XS Rating Curve= 0 ,0
Exp/Cntr(USF)=0,0
Exp/Cntr=0.3,0.1

Type RM Length L Ch R = 1 ,68506   ,488.7,500,515.4
XS GIS Cut Line= 6
1665743.81995501367501.0116872491666220.55653434368174.800694004
1666271.26345393368246.1105907561666325.76236068368322.393902749
1666439.49966601368481.1770497561666555.36951301368642.757763341
#Sta/Elev= 30
       0 1000.82   132.1  989.91   156.2  976.26   244.4  980.19     313  968.86
   407.4  943.67   519.3  906.31   572.7  880.95   602.1  871.77   625.4  856.12
   651.5  826.24  676.47814.4193     705  811.05   725.9  814.55   758.9  819.02
   786.1  828.25   807.9  824.08   832.4  832.69   875.1  832.07   901.1  851.84
   920.8  854.71   945.4  874.02   984.7   888.3  1012.7  909.69  1051.9  919.82
  1095.9  923.03  1181.9  911.35  1262.1   877.4  1314.4   896.5  1400.8  910.22
#Mann= 7 ,-1,0
       0      .1       0  645.39    .025       0  676.47    .045       0
   725.9    .025       0  750.39      .1       0  770.39     .07       0
  885.39      .1       0
#XS Ineff= 2 , 0
                          786.77          866.81
Permanent Ineff=
       F       F
Bank Sta=676.47,725.9
XS Rating Curve= 0 ,0
Exp/Cntr(USF)=0,0
Exp/Cntr=0.3,0.1

Type RM Length L Ch R = 1 ,68006   ,493.5,500,509.6
XS GIS Cut Line= 6
1665591.92426142367604.7765715871665633.50587118367815.210862011
1665684.36403717368011.306270346   1665711.20191368191.657943755
1665716.82919534368266.4970329251665745.66968884369016.333131671
#Sta/Elev= 30
       0  946.71    40.4  934.55    58.4  940.24    81.1   940.1   188.6  922.31
   298.6  913.51   335.6  903.79   393.6  880.57   430.5  875.46   487.2  856.69
   568.1  841.27   612.3  821.39   692.6  819.15  706.48813.4243   720.6  810.61
   752.6  813.36   776.6  826.97   802.3  830.29   828.7  849.51   872.4  857.56
   888.7   871.3   900.7  898.36   912.7  915.46   940.7  931.43   976.8  941.26
  1024.8  947.51  1156.9  983.28    1229 1016.27    1293 1033.58  1424.9 1086.12
#Mann= 5 ,-1,0
       0      .1       0  706.48    .045       0   752.6     .05       0
  834.51     .06       0  929.51      .1       0
Bank Sta=706.48,752.6
XS Rating Curve= 0 ,0
Exp/Cntr(USF)=0,0
Exp/Cntr=0.3,0.1

Type RM Length L Ch R = 1 ,67506   ,502,500,497.4
XS GIS Cut Line= 6
1665442.33040051367562.1326280091665412.25926642367657.094708428
 1665295.0393565 368027.259322421665166.73515117368432.429771915
1665109.18638176 368614.160051511665019.44410717368897.556138262
#Sta/Elev= 30
       0  930.62   157.8  865.31   174.5  855.42   199.7  847.83   245.8  841.35
   308.8  846.04   414.8  869.18   484.9  859.44   523.1   839.1   561.3  826.42
   672.9  817.73   681.8  812.76   690.6  810.55   730.2  812.83   745.2  823.69
     778  827.15   791.3   847.3   806.7  860.21   866.9  859.32   883.6  867.79
   921.4  864.49   974.6  870.33  1001.1  885.88    1033  913.67  1043.1  918.25
  1093.4  918.54  1120.3     924  1279.3  910.88  1319.8  903.91  1400.8  878.98
#Mann= 8 ,-1,0
       0      .1       0   681.8    .045       0   730.2     .05       0
  800.39     .07       0  845.39     .06       0  905.39      .1       0
 1173.52     .06       0 1211.95      .1       0
Bank Sta=681.8,730.2
XS Rating Curve= 0 ,0
Exp/Cntr(USF)=0,0
Exp/Cntr=0.3,0.1

Type RM Length L Ch R = 1 ,67006   ,502.3,500,497
XS GIS Cut Line= 6
1664956.04528384367339.0579429271664755.85900442   368139.804701
1664727.90138318 368223.00794667  1664691.526784368310.549766332
1664608.25267234368491.0549827521664520.03565717368674.782305583
#Sta/Elev= 30
       0  976.63    37.4  965.88    63.4  964.39   199.4  937.29   257.2  929.84
   376.7  922.09   488.1  919.13   549.9  910.27   578.8  895.24   632.4  857.62
   644.7  845.35   665.3  819.04   674.1   811.8   706.6  809.82   727.8   811.5
   747.8  816.33   801.4  816.26   826.2  824.17     843  822.97   872.6  827.66
   902.1  836.73   975.2  832.11    1012  825.95  1054.4  824.83  1103.6  833.15
  1190.7  856.02  1270.8   864.1  1346.1   858.5  1382.4  849.53  1410.6  838.79
#Mann= 5 ,-1,0
       0      .1       0   674.1    .045       0   727.8      .1       0
  810.39     .07       0 1003.17      .1       0
Bank Sta=674.1,727.8
XS Rating Curve= 0 ,0
Exp/Cntr(USF)=0,0
Exp/Cntr=0.3,0.1

Type RM Length L Ch R = 1 ,66506   ,505.9,500,491.2
XS GIS Cut Line= 6
1664398.72323576 367232.211043761664384.01919693367330.729219422
1664326.70172626367714.7566665861664263.96366276368135.100314096
1664221.29281634368420.9960677621664191.94182517368617.645936921
#Sta/Elev= 30
       0  1021.9   109.5 1010.36   234.9 1019.87   271.3 1018.57   295.6 1013.01
   315.8 1004.68   360.3  976.28   388.6   966.6   437.1  939.45   457.3  936.08
   576.2  870.25   635.3  852.61   651.5  839.47   671.2  815.45   683.8  812.31
   724.3  808.23   747.2 812.366   768.7  822.56   797.1  822.35   821.3  831.57
   926.5  826.19   962.3  848.59  1003.3  866.38  1026.6  867.94  1035.7  880.02
    1068  904.34  1100.5  911.84  1128.7  923.41  1301.1  937.59  1400.8  940.68
#Mann= 8 ,-1,0
       0      .1       0   683.8    .045       0   747.2      .1       0
  810.39     .08       0  905.39      .1       0 1201.95     .05       0
 1301.17     .07       0 1321.17      .1       0
Bank Sta=683.8,747.2
XS Rating Curve= 0 ,0
Exp/Cntr(USF)=0,0
Exp/Cntr=0.3,0.1

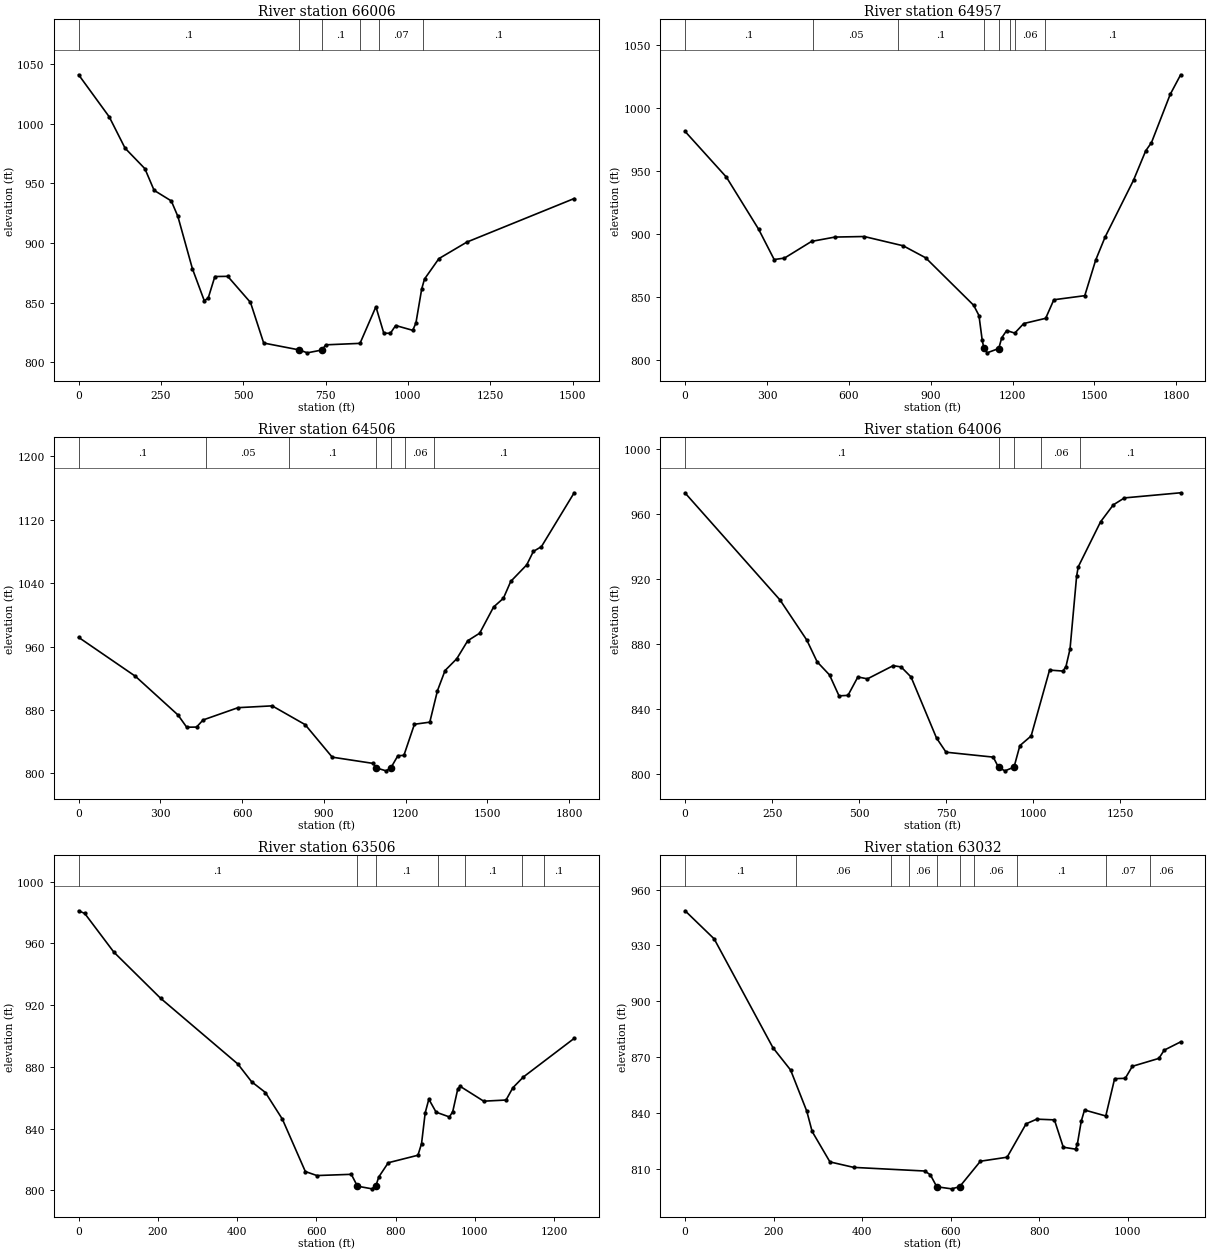
Type RM Length L Ch R = 1 ,66006   ,1057,1048.8,1020.9
XS GIS Cut Line= 6
1663749.65498009367179.8541930911663806.93472117368003.254777253
1663811.25459443368090.6660197531663813.87433983368184.460123509
1663856.99302001368283.5606470851664080.57000068368603.160401583
#Sta/Elev= 30
       0 1040.97    92.9 1005.75     141  979.49   201.2  962.33   229.2  944.18
   281.4   935.3   301.4  922.32   345.5  878.54   381.6  851.69   393.6  854.02
   413.7  871.96   452.8  872.14   521.9  850.26     562  816.26   670.4  810.47
   694.4  808.05  738.64810.4058   750.5  814.76   854.5  815.99   902.8  846.65
   926.8  824.49   946.8  824.44   962.8  830.95  1014.6  826.91  1024.3  832.99
  1041.9  861.63  1050.4  869.88  1094.1  886.97  1179.1  900.83  1504.9   937.3
#Mann= 6 ,-1,0
       0      .1       0   670.4    .045       0  738.64      .1       0
  855.39     .06       0  912.91     .07       0 1046.74      .1       0
Bank Sta=670.4,738.64
XS Rating Curve= 0 ,0
Exp/Cntr(USF)=0,0
Exp/Cntr=0.3,0.1

Type RM Length L Ch R = 1 ,64957   ,425.1,451.2,475.8
XS GIS Cut Line= 4
1663035.63023112367455.7377055231663209.59482137368379.385888302
1663541.76298314369044.7368624781663601.58883412369162.714721626
#Sta/Elev= 30
       0   981.4   151.4  945.09   269.5  903.69   326.4  879.65   364.2  880.81
   463.5  894.07   549.1   897.5   656.1  897.94   799.2  890.57   881.4  881.04
  1057.4  843.31  1076.8  835.18  1088.7  815.58 1094.82809.1712  1106.5  805.53
1149.237808.9604  1160.2  817.45  1178.2  823.25    1208  821.21  1240.8  828.79
  1321.2  832.96  1351.2   847.7  1464.5  850.94  1504.5  879.22    1539   897.5
  1643.1  942.65  1687.8     966    1709  972.58  1777.4 1010.78  1815.8 1026.42
#Mann= 8 ,-1,0
       0      .1       0     470     .05       0     780      .1       0
 1094.82    .045       01149.237     .05       0 1189.89     .07       0
 1209.89     .06       0 1319.89      .1       0
Bank Sta=1094.82,1149.237
XS Rating Curve= 0 ,0
Exp/Cntr(USF)=0,0
Exp/Cntr=0.3,0.1

Type RM Length L Ch R = 1 ,64506   ,485.7,500,515
XS GIS Cut Line= 6
1662952.45119393367461.3503492621662931.54473968 367639.69349651
1662925.56509285367838.390933752 1662967.2605475368242.246425256
1662956.77008292368361.2422502491662533.01797767369171.318386003
#Sta/Elev= 30
       0  971.74   208.4  922.59   364.5  873.79   396.5  858.33   432.6  858.49
   456.7  867.48     585  882.99   710.2  885.28   831.1  861.59   930.5  820.53
  1080.6  812.64  1092.5  806.95  1128.1  803.26    1146  807.24  1171.5   822.4
  1193.5  822.76  1232.1  862.04  1288.5   864.7  1316.7  904.48  1344.6  929.87
  1387.6  944.79  1427.8   967.5  1471.5  976.98  1522.6 1010.03  1558.6 1021.04
  1585.6 1042.36  1644.2 1063.21  1668.5 1080.17  1698.2 1086.25  1818.3 1154.21
#Mann= 7 ,-1,0
       0      .1       0  468.35     .05       0   770.3      .1       0
  1092.5    .045       0    1146      .1       0 1197.95     .06       0
 1302.95      .1       0
Bank Sta=1092.5,1146
XS Rating Curve= 0 ,0
Exp/Cntr(USF)=0,0
Exp/Cntr=0.3,0.1

Type RM Length L Ch R = 1 ,64006   ,497.8,500,502.8
XS GIS Cut Line= 6
1662941.06735842367448.406149417 1662908.7767406367613.804768756
1662880.02942276367786.6138063371662849.19746342367946.278185174
1662785.11655484368035.1379155961662078.96081492368427.445529923
#Sta/Elev= 30
       0  972.85   272.7  906.95   349.7  882.23   379.4  868.83   414.9  860.77
   442.2  847.89   467.9  848.17   496.4  859.52   523.9  858.36   597.9  866.49
   620.6  865.69   649.1  859.52   722.3  821.92   749.7  813.17   885.3  810.14
   900.7  803.76     919  801.69  945.01803.9861   961.8  817.22   994.2  823.17
  1047.1  863.75  1085.4  863.16  1094.2  865.91  1105.9  876.72  1124.9  921.71
  1129.5  927.36  1193.6  955.07  1230.2  965.53  1262.2  969.82  1423.7  972.98
#Mann= 5 ,-1,0
       0      .1       0   900.7    .045       0  945.01      .1       0
 1022.12     .06       0 1134.62      .1       0
Bank Sta=900.7,945.01
XS Rating Curve= 0 ,0
Exp/Cntr(USF)=0,0
Exp/Cntr=0.3,0.1

Type RM Length L Ch R = 1 ,63506   ,479.4,473.9,462.3
BEGIN DESCRIPTION:
Structure 21 XS 4
END DESCRIPTION:
XS GIS Cut Line= 6
1662911.94536942367386.5532547531662850.53309068367490.098979428
1662763.54146676367539.2022276671662583.46669567367614.833310008
1661929.43585151367889.526330173 1661869.7512596368000.142906845
#Sta/Elev= 30
       0  981.13    15.4   979.4    88.9  954.33   206.7  924.46   401.9  881.81
   436.6  870.32   471.4  863.35   514.2  846.09   572.2  812.12   601.4  809.52
   688.2  810.32   703.6  802.65   740.3  800.91  750.33802.9811   757.6  808.63
   781.5  817.83   856.4  822.69   865.5  830.24   874.7  850.19   883.9  859.01
   902.2   850.6   935.8  847.51   944.2  850.95   957.1  865.85   963.3  867.29
  1022.3  857.73  1078.7  858.47    1096  866.44  1122.4  873.38  1250.7  898.42
#Mann= 7 ,-1,0
       0      .1       0   703.6    .045       0  750.33      .1       0
  906.84     .07       0  974.34      .1       0 1118.09     .06       0
 1174.97      .1       0
Bank Sta=703.6,750.33
XS Rating Curve= 0 ,0
Exp/Cntr(USF)=0,0
Exp/Cntr=0.3,0.1

Type RM Length L Ch R = 1 ,63032   ,71.8,67,67.8
BEGIN DESCRIPTION:
Structure 21 XS 3
END DESCRIPTION:
XS GIS Cut Line= 6
1662074.48658005366899.266425746 1662115.4895352367271.860837737
1662016.70093757367393.8030129391661917.91233993367498.765897924
 1661851.5387509 367532.724478361661854.62589458367901.638147642
#Sta/Elev= 30
       0  948.62    65.7  933.53   198.5  875.13   238.3  863.18   274.9  841.07
     287  830.19   327.2  813.87   380.9  810.93     541  808.99   553.9     807
   568.5  800.53     602  799.42   620.2  800.57   667.1  814.24   727.4  816.39
   770.3   834.3   794.3  836.81   834.3  836.43   854.3  821.75   882.3  820.71
   886.3  823.73   894.9  835.72   902.3  841.72   950.3  838.52   970.3  858.54
   994.3  858.72  1010.3  865.16  1070.3  869.42  1082.3  873.84  1119.4  878.28
#Mann= 10 ,-1,0
       0      .1       0     250     .06       0  464.84      .1       0
  504.84     .06       0   568.5    .045       0   620.2      .1       0
  651.78     .06       0  750.48      .1       0  950.48     .07       0
 1050.48     .06       0
Bank Sta=568.5,620.2
XS Rating Curve= 0 ,0
Exp/Cntr(USF)=0,0
Exp/Cntr=0.3,0.1

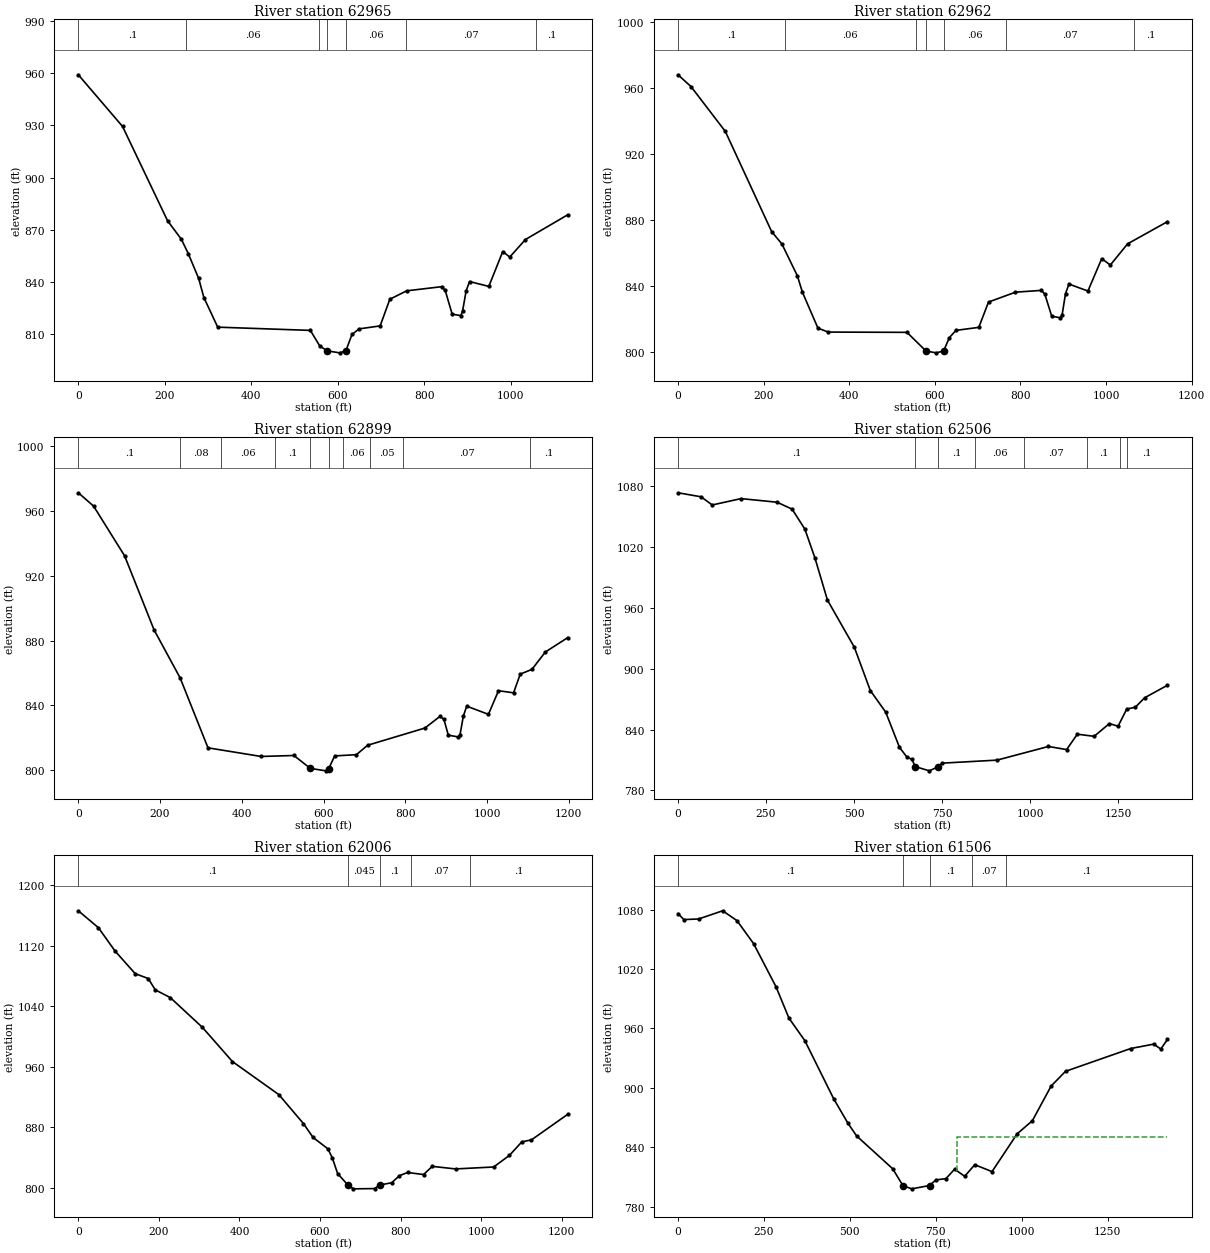
Type RM Length L Ch R = 1 ,62965   ,2.9,2.6,2.4
BEGIN DESCRIPTION:
Structure 21 XS 2
END DESCRIPTION:
XS GIS Cut Line= 6
1662051.30743704366898.3884439461662060.05093493367281.270554567
1661945.41259645 367396.987458471661918.64893829367413.603678423
1661790.42509027367524.9555193611661839.27665052367905.464730832
#Sta/Elev= 30
       0  959.05   102.2  929.39   206.3  875.21   238.2  864.59   254.2  856.32
   278.2  842.09   290.2  831.13   322.2  814.13   536.3  812.27   558.1  803.32
   575.5  800.51   603.8  799.38   618.4800.5208   632.6  809.96   649.1  813.15
   697.6  814.84   720.1  830.18     759  834.99   839.9  837.37     848  835.27
   864.1  821.58   884.3  820.75   888.3  823.49   896.4     835   904.4  840.32
   948.8  837.53   981.1  857.56   997.2  854.38  1033.5  864.45  1131.2  878.65
#Mann= 7 ,-1,0
       0      .1       0     250     .06       0  555.87      .1       0
   575.5    .045       0   618.4     .06       0  757.58     .07       0
 1057.58      .1       0
Bank Sta=575.5,618.4
XS Rating Curve= 0 ,0
Exp/Cntr(USF)=0,0
Exp/Cntr=0.5,0.3

Type RM Length L Ch R = 1 ,62962   ,58.8,63.3,64.9
BEGIN DESCRIPTION:
Structure 20 XS 3
END DESCRIPTION:
XS GIS Cut Line= 6
1662031.36559036366890.1374773911662050.23146838367282.890756171
 1661952.5723678367385.4582334661661877.00840656367452.683658351
1661780.96393664367524.7170107911661827.27109178367908.894890472
#Sta/Elev= 30
       0  967.94    30.4  960.76   110.5   933.6   218.7  872.85   242.7  865.33
   278.7  846.09   290.7  836.04   326.8  814.34   350.8  811.94   534.8  811.77
   579.3  800.44   603.3  799.35   620.4  800.48   633.9   808.6   649.3  812.97
   702.6   814.8   725.3  830.15   788.3  836.13   848.7  837.22   856.8  835.01
   872.9  821.54   893.1  820.61   897.1  822.16   905.2  835.31   913.2  841.04
   957.5  836.83   989.8  856.46  1009.9  852.59  1050.2  865.44  1143.2  878.87
#Mann= 7 ,-1,0
       0      .1       0     250     .06       0  554.83      .1       0
   579.3    .045       0   620.4     .06       0  766.26     .07       0
 1066.26      .1       0
Bank Sta=579.3,620.4
XS Rating Curve= 0 ,0
Exp/Cntr(USF)=0,0
Exp/Cntr=0.5,0.3

Type RM Length L Ch R = 1 ,62899   ,439.9,393.4,323.6
BEGIN DESCRIPTION:
Structure 20 XS 2
END DESCRIPTION:
XS GIS Cut Line= 6
1662012.49971234366895.2827168511662019.36003162367262.309798331
  1661949.041759367325.7677516711661808.40521376367432.102700511
 1661708.9305842367493.845574031 1661803.2599743367926.045688672
#Sta/Elev= 30
       0  971.31    37.3  963.09   113.3  932.36   185.3  886.68   249.3  856.89
   317.3  813.81   447.4  808.47   527.5  809.08   567.9801.0828   606.5   799.6
     613  801.02     613  801.06   627.3  808.81   680.6  809.59   707.9   815.4
   848.1  826.02   884.9  833.21   894.6  831.47   905.4  821.63   929.9  820.54
     934  821.79   942.2   833.4   950.4  839.55  1003.6  834.48  1028.2  849.08
  1065.1  847.77  1081.4  859.31  1110.1  862.27  1142.8  872.97  1197.6  881.85
#Mann= 10 ,-1,0
       0      .1       0     250     .08       0     350     .06       0
  481.81      .1       0   567.9    .045       0     613      .1       0
  648.15     .06       0  714.33     .05       0  795.24     .07       0
 1105.24      .1       0
Bank Sta=567.9,613
XS Rating Curve= 0 ,0
Exp/Cntr(USF)=0,0
Exp/Cntr=0.3,0.1

Type RM Length L Ch R = 1 ,62506   ,502.3,499.9,496.1
BEGIN DESCRIPTION:
Structure 20 XS 1
END DESCRIPTION:
XS GIS Cut Line= 6
1660894.37132059366995.9700464161661555.72006351367349.934889674
1661596.33874868367434.3497470921661687.00753058 367666.52940084
1661738.24889793367788.0160344991661774.15794684   367949.387759
#Sta/Elev= 30
       0 1073.07    65.5 1069.11    97.2 1061.06     179 1067.33   281.2 1063.78
     324 1056.97   360.3 1037.34   388.9 1008.94   424.4  967.48   500.9  920.94
   546.2  878.39   589.9  857.14   629.1  822.43   650.6  812.66   664.2  810.75
  673.78803.4865     714  799.31   738.8  803.35   750.1  806.88   906.1  809.86
  1052.2   823.3  1103.9  820.24  1134.3   835.4  1182.1  833.28  1225.4  845.86
    1250  843.23  1274.6   860.1  1299.2  861.98  1325.6  871.27  1390.2  883.55
#Mann= 8 ,-1,0
       0      .1       0  673.78    .045       0   738.8      .1       0
   843.8     .06       0  983.08     .07       0 1163.06      .1       0
 1254.91     .07       0 1274.91      .1       0
Bank Sta=673.78,738.8
XS Rating Curve= 0 ,0
Exp/Cntr(USF)=0,0
Exp/Cntr=0.3,0.1

Type RM Length L Ch R = 1 ,62006   ,504.7,500,496.8
XS GIS Cut Line= 6
1660656.51713751367502.6642430131660929.74756217367619.762434006
1661185.38484618367729.3215980831661254.32073192367758.865174174
1661670.80841601367937.3595678361661740.43754184368024.059525669
#Sta/Elev= 30
       0 1165.86    49.9 1143.51      91 1112.81   141.2 1082.85   173.6 1076.41
     191 1061.46   228.2 1051.29   307.9 1012.01   382.5  966.85   497.7  923.18
   558.6  885.06   582.7   866.6   619.5  851.61   630.6  839.38   643.6  819.05
   668.3  804.27   682.8  798.81   735.3  799.15   748.1   803.9   777.9  806.84
   796.8  816.15   817.1  820.38   856.9   817.7   878.6   828.5   936.3  825.09
    1031  827.65  1070.1  843.02  1100.8  860.82  1124.8  863.47  1214.7  897.19
#Mann= 5 ,-1,0
       0      .1       0   668.3    .045       0   748.1      .1       0
  825.39     .07       0  972.89      .1       0
Bank Sta=668.3,748.1
XS Rating Curve= 0 ,0
Exp/Cntr(USF)=0,0
Exp/Cntr=0.3,0.1

Type RM Length L Ch R = 1 ,61506   ,502.5,500,498
XS GIS Cut Line= 6
1660444.09630251368033.5194805121661160.53778301368256.672905594
1661497.68704309368361.6858189261661591.67110708368390.960038587
1661686.40090451368420.4652289151661763.29149875368515.467007428
#Sta/Elev= 30
       0  1076.1    16.8 1070.04    59.9 1070.65   129.9 1078.93   171.6 1068.94
   219.7 1045.79   284.9 1002.24   322.6  970.49   368.7   947.8   452.5  889.14
   494.4  864.15   519.5  851.41   624.3  818.31   654.1  801.28   679.7  797.99
  731.68801.3484   749.9  806.97   779.3  808.34   804.4  817.85   833.7  810.66
   863.1  822.36   913.3   815.4   986.3  853.56  1030.6   866.8  1085.1  901.81
    1127  916.72  1316.7  939.76  1383.6  944.21  1404.2   939.2  1423.4   948.9
#Mann= 5 ,-1,0
       0      .1       0   654.1    .045       0  731.68      .1       0
  855.39     .07       0  952.89      .1       0
#XS Ineff= 2 , 0
                          811.59          849.93
Permanent Ineff=
       F       F
Bank Sta=654.1,731.68
XS Rating Curve= 0 ,0
Exp/Cntr(USF)=0,0
Exp/Cntr=0.3,0.1

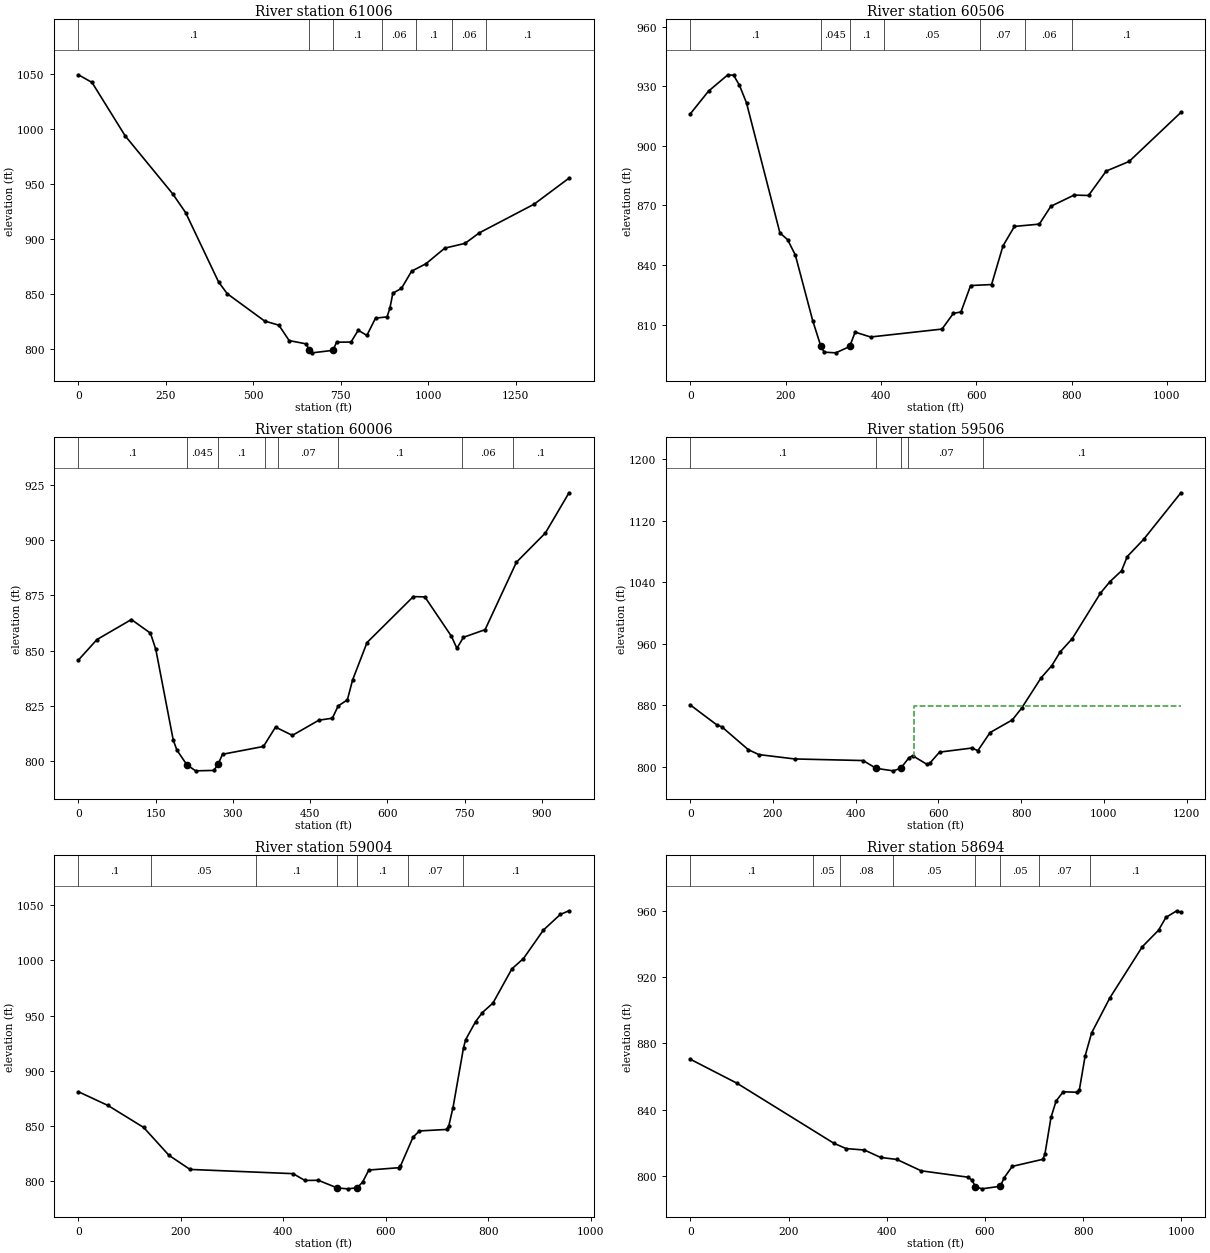
Type RM Length L Ch R = 1 ,61006   ,511,500,488
XS GIS Cut Line= 6
1660318.34852251368564.7297041711660608.67996284368635.493670255
1660703.19060059368657.5015002491660794.77571926368677.702247262
1660879.92285867368697.8856058421661680.66863251368898.075166091
#Sta/Elev= 30
       0 1049.02    38.9 1042.08   133.5  993.77   269.4  941.19   306.5  924.12
   400.9  861.12   425.5  850.58   532.1  825.85   573.2  822.01   602.6  808.05
   651.6  805.06   659.8  799.18   668.1  796.95  727.76799.1964   738.2  806.63
   779.4  806.71     800  817.46   824.7  812.74   849.5  828.44   882.5  829.51
   890.7  837.74     899  850.99   923.7  855.43   952.6  870.96   993.8  877.76
  1047.4  891.86  1105.3  896.17  1146.3  905.73  1302.9  931.73  1402.6  955.32
#Mann= 7 ,-1,0
       0      .1       0   659.8    .045       0  727.76      .1       0
  867.16     .06       0  964.66      .1       0 1068.41     .06       0
 1165.29      .1       0
Bank Sta=659.8,727.76
XS Rating Curve= 0 ,0
Exp/Cntr(USF)=0,0
Exp/Cntr=0.3,0.1

Type RM Length L Ch R = 1 ,60506   ,513.8,500,490.1
XS GIS Cut Line= 6
1660558.15447333369243.7230968331661070.97529809369165.482111588
1661164.75463809369158.5795663451661365.61053559369172.612674758
1661471.55126859369177.7845804241661580.71968542369176.926970586
#Sta/Elev= 30
       0  916.06    38.4  927.54    78.9  935.75      91  935.49   103.1  930.52
     118   921.6   188.1  856.15   204.3  852.71   220.5  844.98   256.9  811.97
274.1301798.9822   281.2  796.09   305.5  795.76334.4801798.9576   345.9  806.18
   378.3  803.74   528.2  807.72     552  815.63     568  816.34   588.2  829.64
   632.2  830.14   656.2  849.62   680.2  859.41   732.4  860.56   756.5  869.53
   805.3  875.18   835.6  874.98   872.7  887.27   920.8  892.11  1029.4  916.79
#Mann= 7 ,-1,0
       0      .1       0274.1301    .045       0334.4801      .1       0
  406.27     .05       0  608.76     .07       0  702.79     .06       0
  801.64      .1       0
Bank Sta=274.1301,334.4801
XS Rating Curve= 0 ,0
Exp/Cntr(USF)=0,0
Exp/Cntr=0.3,0.1

Type RM Length L Ch R = 1 ,60006   ,435,500,531.7
XS GIS Cut Line= 6
1660811.46224675369744.0409367991660935.63436143369717.597805262
 1661001.6857385369681.6966303441661087.20590867369629.867009595
1661389.19841492369446.8430974191661643.42001934369292.771227092
#Sta/Elev= 30
       0  845.72      36  855.01   102.9  864.08   139.9  857.92   150.3  850.57
   184.1  809.55   191.2  804.97210.5648798.3286   227.5  795.56     263  795.75
271.3448 798.593   279.8  803.06   359.3   806.6   382.7  815.37   415.5  811.62
   466.8  818.49   493.1   819.4   504.3  824.94   522.2   827.7   532.4  836.75
   560.4  853.67   650.3  874.48   672.7  874.32   724.2  856.52   734.8  851.06
   747.5  856.03   789.6   859.5   850.4  890.04   906.6  903.27   952.5  921.49
#Mann= 8 ,-1,0
       0      .1       0210.5648    .045       0271.3448      .1       0
  362.13     .05       0  387.13     .07       0  504.63      .1       0
  745.26     .06       0   843.7      .1       0
Bank Sta=210.5648,271.3448
XS Rating Curve= 0 ,0
Exp/Cntr(USF)=0,0
Exp/Cntr=0.3,0.1

Type RM Length L Ch R = 1 ,59506   ,478.6,501.2,518.6
XS GIS Cut Line= 6
1660674.93145174  369628.21553771660674.32042685369794.130489317
 1660736.8791815369881.1742497531660783.17994192369955.591095671
1660871.35496242370106.7538510861661199.06657735370668.548003092
#Sta/Elev= 30
       0  880.59    64.3  854.65    76.3  852.15   140.3  822.45   165.9  816.05
   252.6  810.39   417.7  808.32449.6522798.1326   490.8  794.94508.6821798.1972
   528.8  812.01   537.6  814.64   572.7  803.22   579.5  805.13   602.6  819.26
   680.9  824.59   695.3  821.19   724.8   844.7   778.6  861.15   800.8  876.21
   848.1   915.8     874  931.66   894.4  949.61   923.7  966.96   991.6  1025.9
  1014.3 1040.68  1042.6 1054.98  1056.5  1073.5  1096.2 1095.92  1186.1 1156.39
#Mann= 5 ,-1,0
       0      .1       0449.6522    .045       0508.6821      .1       0
  525.75     .07       0  708.25      .1       0
#XS Ineff= 2 , 0
                          541.77          878.79
Permanent Ineff=
       F       F
Bank Sta=449.6522,508.6821
XS Rating Curve= 0 ,0
Exp/Cntr(USF)=0,0
Exp/Cntr=0.3,0.1

Type RM Length L Ch R = 1 ,59004   ,310.3,310.3,310.9
BEGIN DESCRIPTION:
Structure 19 XS 4
END DESCRIPTION:
XS GIS Cut Line= 6
1660479.76550832 369565.886204151660464.37508113369607.831325414
1660444.58903145369693.0650788271660427.62909163369766.122347402
 1660347.0705257 370113.144291151660257.94406354370497.075937989
#Sta/Elev= 30
       0  880.86    57.7   868.4   127.5   848.4   176.8  823.14   217.9  810.34
   419.1   806.5   442.1  800.33   468.4  800.47   505.4  793.49   525.8  792.72
   544.2793.7086   554.6  798.75   566.9  809.79   625.4   811.9   628.5  813.24
   653.1  839.53   665.5  845.26   718.8  846.62     723     850   731.2  866.47
   751.7  920.76   755.8  928.04   775.3  944.51   788.6  952.76   809.2  961.36
   846.1  992.38   868.7 1001.73   907.7 1027.62   940.6 1041.75   957.6 1045.09
#Mann= 7 ,-1,0
       0      .1       0  142.18     .05       0  347.18      .1       0
   505.4    .045       0   544.2      .1       0  643.43     .07       0
   750.3      .1       0
Bank Sta=505.4,544.2
XS Rating Curve= 0 ,0
Exp/Cntr(USF)=0,0
Exp/Cntr=0.3,0.1

Type RM Length L Ch R = 1 ,58694   ,74.6,74.3,74.3
BEGIN DESCRIPTION:
Structure 19 XS 3
END DESCRIPTION:
XS GIS Cut Line= 6
1660378.68760935 369537.061547041660206.46582646369616.370538619
1660136.67886871369681.0346224231660071.39717512369935.287394755
1660007.67026846 370183.487029591659959.09753096370372.663160421
#Sta/Elev= 30
       0  870.51    95.3     856   292.5  819.82   317.3  816.64   354.4  815.78
   387.5  811.31   420.5   810.1   470.1  803.25   565.1  799.42   573.3   797.7
   580.5  793.73   593.7  792.38   631.1  793.93   639.4  799.21   655.5  805.92
   717.9  810.19     722  813.35   734.4  835.44   744.8  845.33   759.2  850.87
   788.1  850.58   792.2  852.19     804  872.64   817.1  886.37   854.1  907.42
   920.2  938.28   953.3  948.25   968.3  955.96   990.4  959.97   998.8  958.94
#Mann= 8 ,-1,0
       0      .1       0  249.61     .05       0  304.75     .08       0
  412.25     .05       0   580.5    .045       0   631.1     .05       0
  709.75     .07       0   813.5      .1       0
Bank Sta=580.5,631.1
XS Rating Curve= 0 ,0
Exp/Cntr(USF)=0,0
Exp/Cntr=0.3,0.1

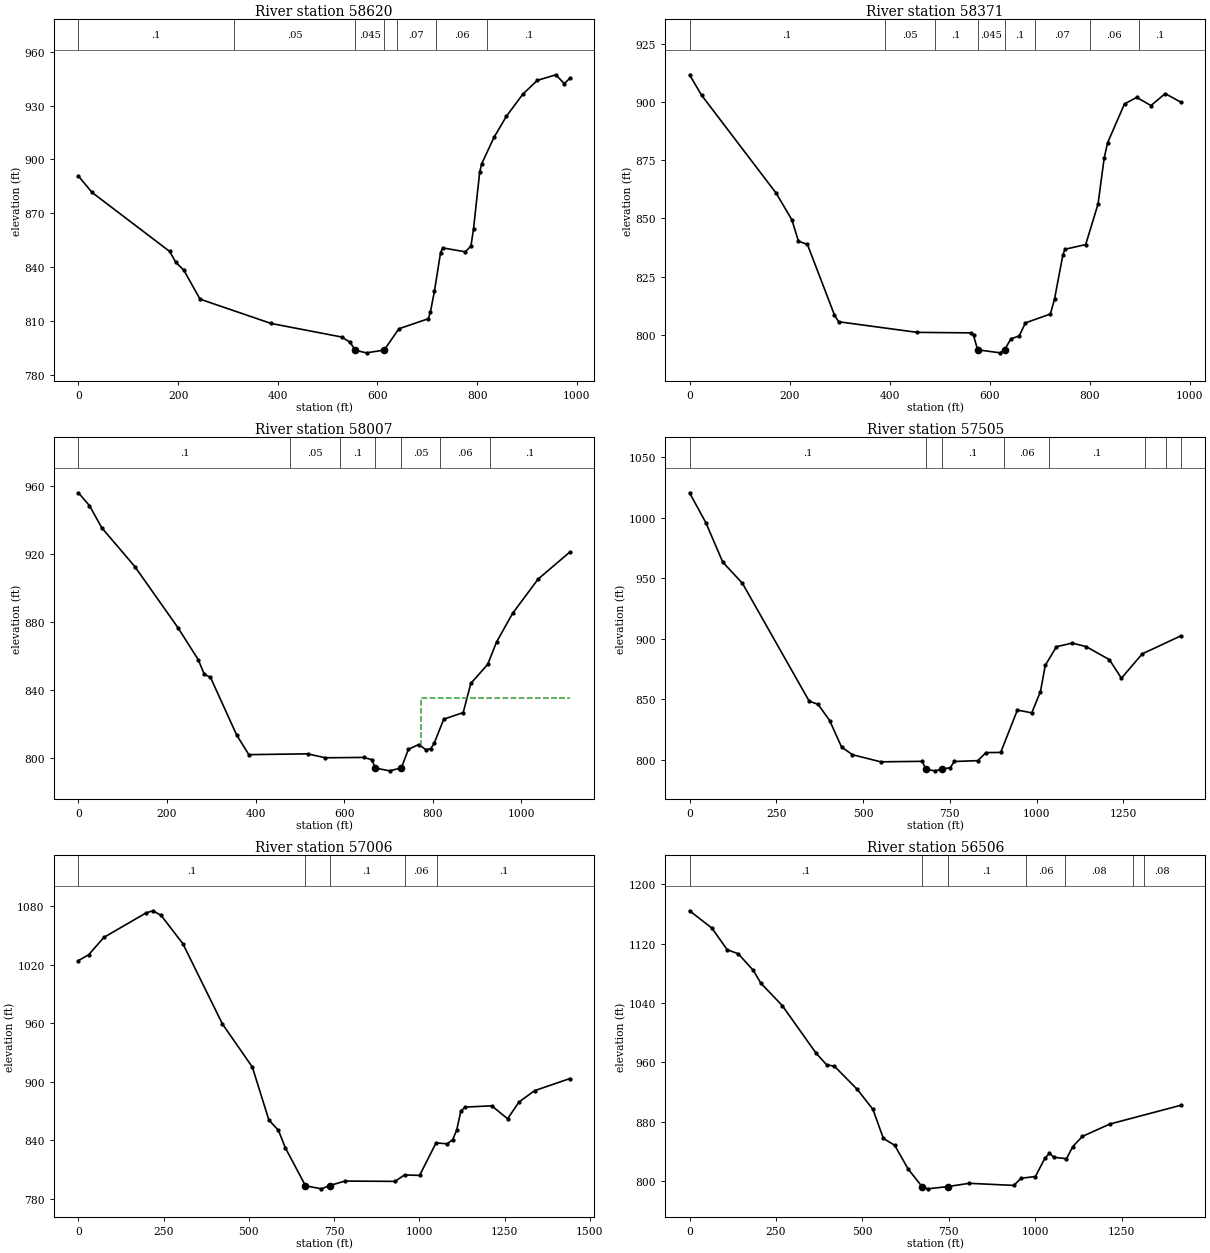
Type RM Length L Ch R = 1 ,58620   ,248.4,248.8,249.3
BEGIN DESCRIPTION:
Structure 19 XS 2
END DESCRIPTION:
XS GIS Cut Line= 6
1660009.11794165369401.8271348821660046.02035568369559.557700306
1660063.36847998369667.7893251361659998.08678639369922.042097468
1659934.35987973370170.2417323031659885.78714223370359.417863134
#Sta/Elev= 30
       0  890.79    27.4  881.65   183.2  848.81   195.4  842.81   211.6  838.37
     244   822.3   386.6  808.77   528.4  801.22   544.9  798.33  555.47793.8076
     578  792.43   613.4  793.96   642.9  805.81   701.9   811.4     706   814.9
   714.3  826.81   726.6  848.25   730.8  850.81   776.2  848.64   787.5  851.83
   792.7  861.46   805.1  893.08   809.2   897.7     834  912.42   858.8   924.1
   891.8  936.41   920.7     944   957.9  947.12   974.8  942.19   985.7  945.11
#Mann= 7 ,-1,0
       0      .1       0   311.6     .05       0  555.47    .045       0
   613.4     .05       0   639.1     .07       0   716.6     .06       0
  820.35      .1       0
Bank Sta=555.47,613.4
XS Rating Curve= 0 ,0
Exp/Cntr(USF)=0,0
Exp/Cntr=0.3,0.1

Type RM Length L Ch R = 1 ,58371   ,355.5,364,369.6
BEGIN DESCRIPTION:
Structure 19 XS 1
END DESCRIPTION:
XS GIS Cut Line= 3
1659904.62720207369329.4100517141659689.69399968370107.816784699
1659721.64352976370279.182446065
#Sta/Elev= 30
       0  911.75      24  902.99   173.4  860.77   204.6  849.37   217.6  840.25
   235.6  838.81   289.6  808.51   297.9  805.59     455  801.03   563.5  800.81
   567.6  799.69  575.76 793.531   620.8  792.23   629.8  793.64   642.3  798.25
   658.9   799.5   671.3  805.11   721.1  808.92   729.4   815.3     746  834.19
   750.2  836.75   791.7  838.76   816.4  856.19   828.6  875.85   835.4  882.48
   869.3  899.25   893.7  902.03   922.2  898.52   950.7  903.67   981.9  899.98
#Mann= 8 ,-1,0
       0      .1       0     390     .05       0     490      .1       0
  575.76    .045       0   629.8      .1       0     690     .07       0
     800     .06       0  897.54      .1       0
Bank Sta=575.76,629.8
XS Rating Curve= 0 ,0
Exp/Cntr(USF)=0,0
Exp/Cntr=0.3,0.1

Type RM Length L Ch R = 1 ,58007   ,493.2,501.9,506.4
XS GIS Cut Line= 6
1659743.78307059369187.076228499  1659640.855783369360.866235256
 1659591.9523375369447.3060230021659458.67996626369693.276987761
1659372.91438976369846.2113931781659186.38950033370146.167814255
#Sta/Elev= 30
       0   956.1      25  948.51    52.9  935.42   127.4  912.64   224.6  876.71
   270.5  857.85   284.3  849.17   298.1  847.44   357.4  813.43   384.8  801.86
   517.5  802.33   557.5  800.01   644.2  800.22   662.6  798.89   670.6  793.95
   702.9  792.32   729.3  794.05   745.3  805.01   768.6  807.83   784.8  804.73
   795.8  805.46   803.4  808.54   825.1  822.75     869  826.65   886.3  843.83
   924.2  854.98   944.5   868.3   980.5  885.03  1038.2  905.27  1109.6  921.13
#Mann= 7 ,-1,0
       0      .1       0  478.85     .05       0  591.06      .1       0
   670.6    .045       0   729.3     .05       0   816.4     .06       0
  929.04      .1       0
#XS Ineff= 2 , 0
                          772.97          835.24
Permanent Ineff=
       F       F
Bank Sta=670.6,729.3
XS Rating Curve= 0 ,0
Exp/Cntr(USF)=0,0
Exp/Cntr=0.3,0.1

Type RM Length L Ch R = 1 ,57505   ,530,499.5,468.9
XS GIS Cut Line= 6
1659517.52696143368946.3755944221659072.18106735369420.036064416
1659005.04143783369494.1559949221658760.05800392 369748.91303134
1658620.07107918369891.1834160831658572.56559676369993.482096002
#Sta/Elev= 30
       0  1020.5    46.9  995.84    95.9  963.17   152.5   945.7   344.9  848.37
   370.4  845.78   403.8   832.4   438.3  810.43   469.6  804.17     551  798.28
   670.4  798.69   681.7  792.04   707.2  790.84     727  792.12   751.5  793.51
   763.1  798.56   830.9  799.25   854.3   805.9   896.8  806.04   944.9  841.05
   986.3  838.73  1011.4  856.28  1025.2  877.93  1057.4  893.36  1103.1  896.36
  1142.9  893.46  1209.9  882.71  1244.7  867.35  1304.7  887.44    1416  902.34
#Mann= 8 ,-1,0
       0      .1       0   681.7    .045       0     727      .1       0
  905.21     .06       0 1036.62      .1       0 1313.23     .08       0
 1373.23      .1       0 1416.02     .08       0
Bank Sta=681.7,727
XS Rating Curve= 0 ,0
Exp/Cntr(USF)=0,0
Exp/Cntr=0.3,0.1

Type RM Length L Ch R = 1 ,57006   ,502.6,499.9,485.6
XS GIS Cut Line= 6
1658575.41992176368558.0994680821658587.67120959   369136.948376
1658648.82692717369468.8358355911658653.99784859369563.397326261
1658642.53625734369662.8531640921658554.78413625369979.977857918
#Sta/Elev= 30
       0 1024.31    30.4 1030.34    74.5 1048.08   198.4 1073.23   218.4 1075.43
   242.5 1070.72   306.5 1041.56   422.5  959.15   510.1  914.98   558.6  860.65
   586.6  850.02   606.7  832.23     666  793.09   712.8  789.95     737  793.36
     782  797.93   928.6  797.61   956.7  804.27  1000.7  803.74    1049  837.14
  1081.2  836.15  1097.4  840.26  1109.4   850.1  1121.7  869.88    1134  873.85
  1212.2   875.2  1258.8  861.87  1292.3  879.14    1338  890.76    1441  903.11
#Mann= 5 ,-1,0
       0      .1       0     666    .045       0     737      .1       0
  956.89     .06       0 1051.59      .1       0
Bank Sta=666,737
XS Rating Curve= 0 ,0
Exp/Cntr(USF)=0,0
Exp/Cntr=0.3,0.1

Type RM Length L Ch R = 1 ,56506   ,521.2,499.7,465
XS GIS Cut Line= 6
 1657827.6802755368726.1493288431658262.61706968369633.984127343
1658306.69670592369720.2936660051658357.48564634369805.349926338
1658414.08395834369889.6470018331658469.57170826369992.714052916
#Sta/Elev= 30
       0 1164.32    64.7    1141   108.9 1111.86   140.8 1106.42   184.2 1084.15
   206.4 1066.74   268.4 1036.48   365.8  972.57   396.8  956.71     419  954.94
   485.4  923.56   530.5  896.68   560.7  857.63   593.5   848.3   632.5  816.26
  672.34 792.788   689.1  789.66   746.7  792.68   808.7   797.1   937.9  794.29
     959  803.92  1000.6  806.27  1027.5  830.62    1041  837.49  1054.3  832.16
  1090.4  830.26  1108.5   846.6  1136.5  860.34  1215.5  876.91  1421.2  902.28
#Mann= 7 ,-1,0
       0      .1       0  672.34    .045       0   746.7      .1       0
   972.9     .06       0 1086.67     .08       0 1282.65      .1       0
 1314.18     .08       0
Bank Sta=672.34,746.7
XS Rating Curve= 0 ,0
Exp/Cntr(USF)=0,0
Exp/Cntr=0.3,0.1