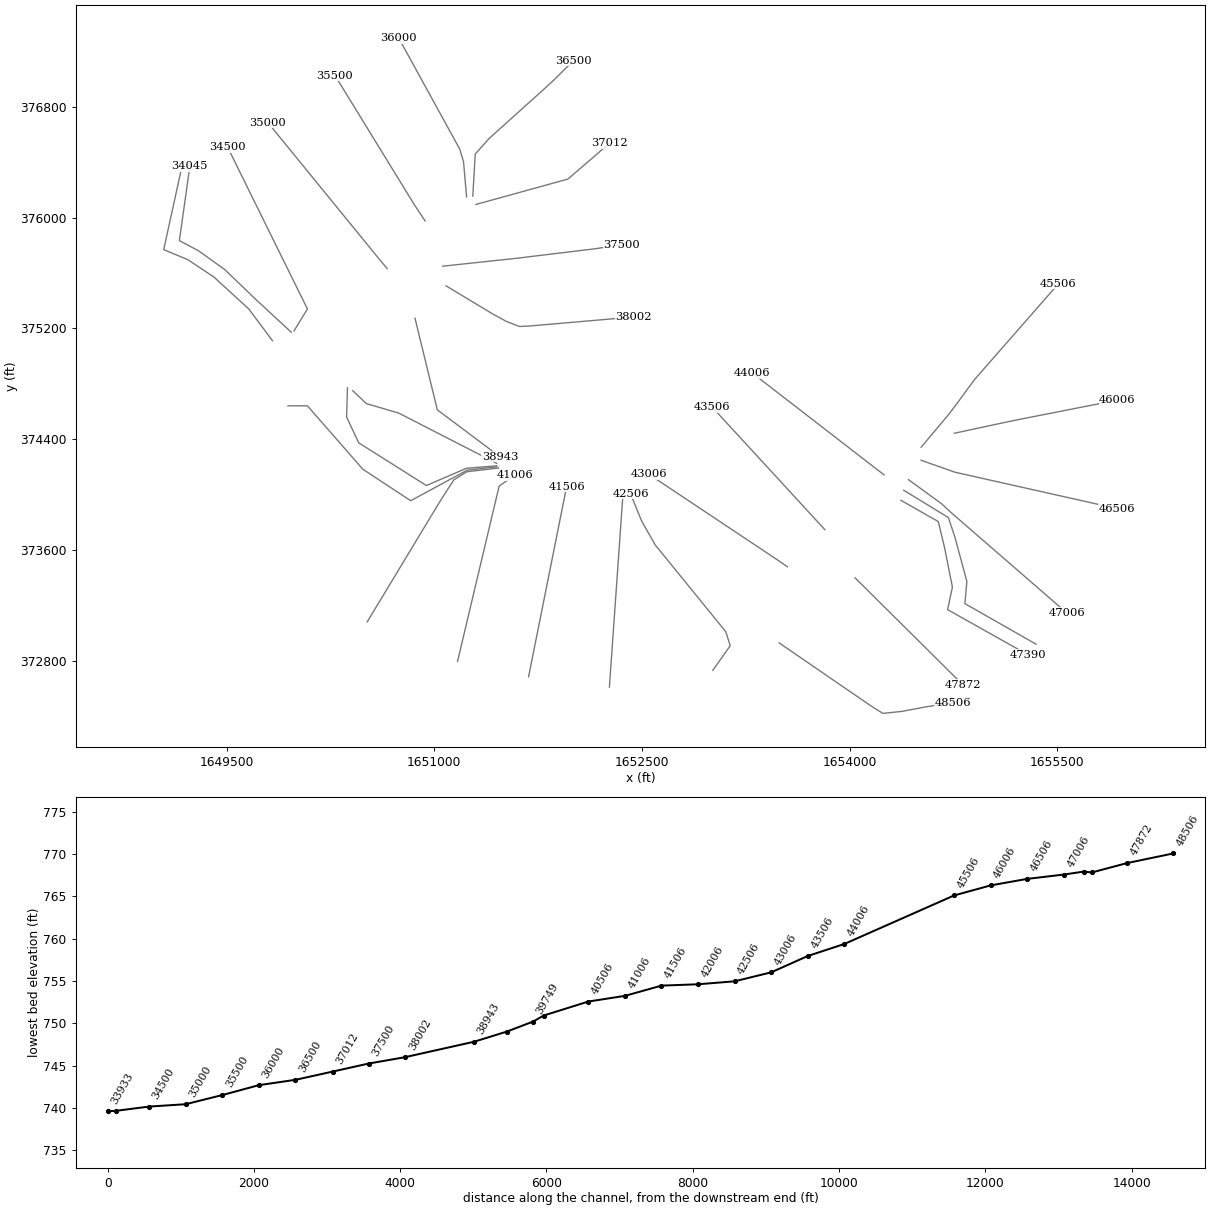
HEC-RAS study SFFSHGCK.prj: SFFSHGCK

--- SFFSHGCK.g01 (geometry) --- (continued)

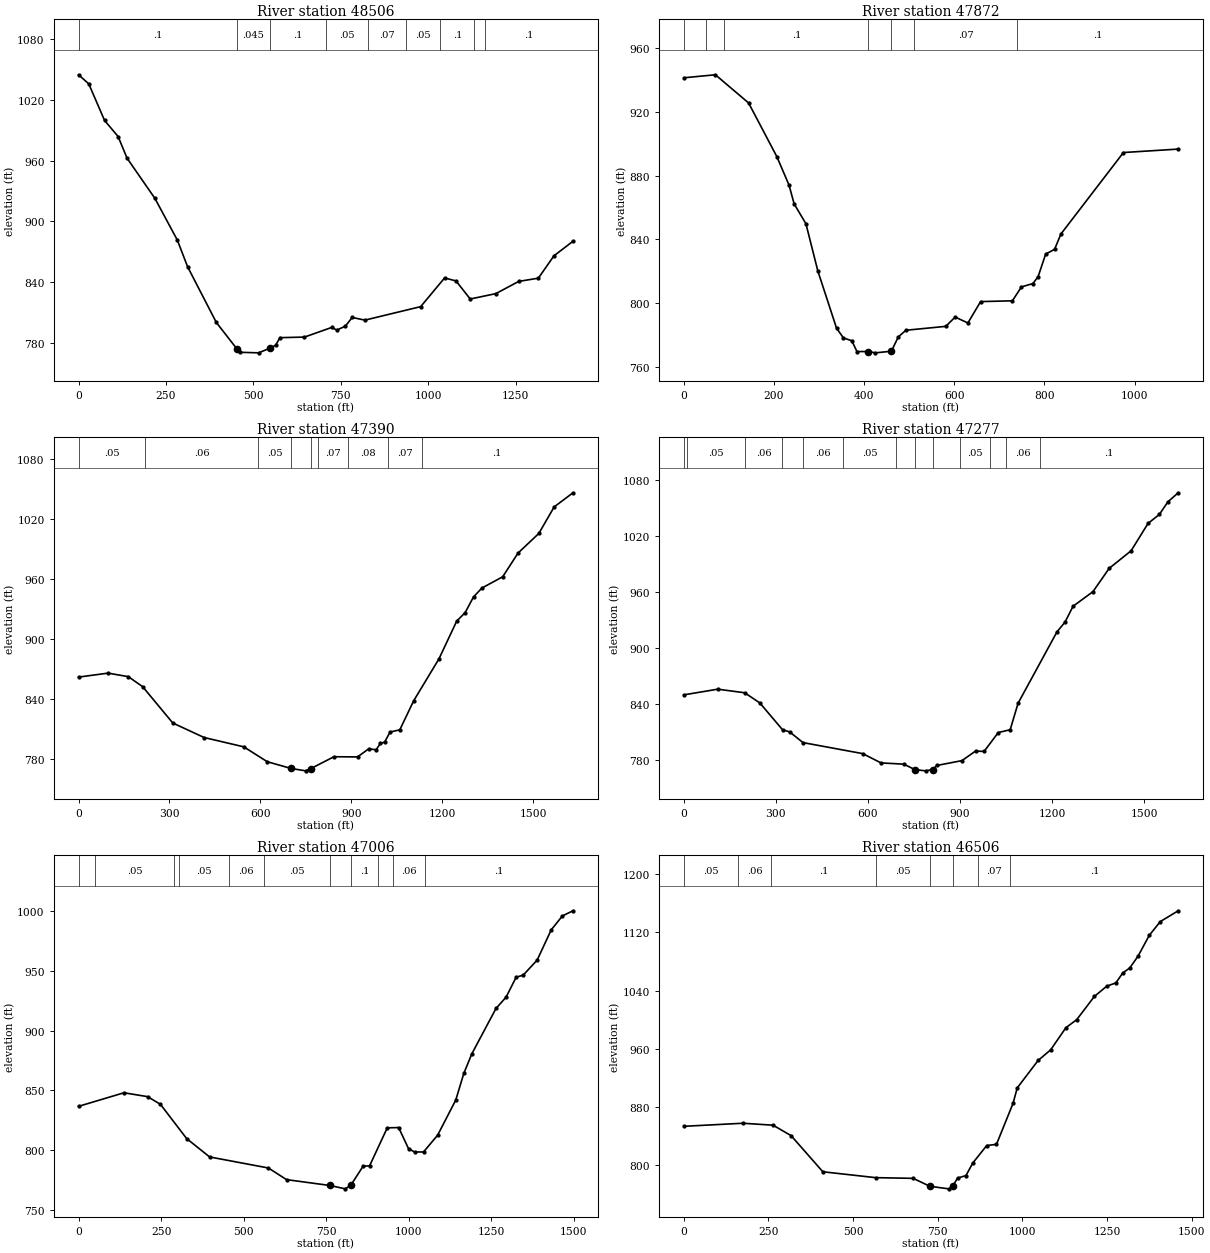
Type RM Length L Ch R = 1 ,48506   ,642.3,633.2,625.3
XS GIS Cut Line= 6
1653490.73652159372927.6727499221654156.67055717372470.401682839
1654239.12019542372418.795814916  1654375.303322372432.974920422
1654549.45028342372465.6198682491654742.01092193372496.052222088
#Sta/Elev= 30
       0 1044.74    29.2 1035.74    74.3  999.64   113.1  983.74   138.5  962.45
   218.3  922.65   282.6  881.36   311.7  855.18     394  800.07452.2098774.2237
   460.9  770.61   515.1  770.06546.0898 774.514   563.5  777.52     576  785.05
     646  785.62   723.8  795.13   738.5  792.58   762.9  796.33   782.6  805.02
   818.9  802.37   978.5   815.7  1046.9  844.06  1079.5   841.1  1120.2  823.24
  1193.4  828.55    1259  840.63  1315.1  843.83  1359.6  865.88  1414.1  880.28
#Mann= 9 ,-1,0
       0      .1       0452.2098    .045       0546.0898      .1       0
  706.56     .05       0  827.83     .07       0  935.09     .05       0
 1035.09      .1       0 1132.01     .05       0 1162.01      .1       0
Bank Sta=452.2098,546.0898
XS Rating Curve= 0 ,0
Exp/Cntr(USF)=0,0
Exp/Cntr=0.3,0.1

Type RM Length L Ch R = 1 ,47872   ,504,482.7,468.4
BEGIN DESCRIPTION:
Structure 17 XS 4
END DESCRIPTION:
XS GIS Cut Line= 2
1654038.39073557373397.9866865951654816.79746855 372625.38895908
#Sta/Elev= 30
       0  941.33    70.1  943.22   143.7  925.58   206.5  891.86   233.5  874.02
   244.8  862.26   270.9  849.88   297.3  820.28   338.8   784.4   354.1  778.27
   372.8  776.47   384.1  769.73   409.5  769.72   425.1  768.92   460.5  769.93
   475.8   778.9   492.7  783.08   581.2  785.52   601.9  791.37   630.2  787.63
   658.4  801.04   728.9  801.53     749  810.25   774.4  812.35   785.8  816.56
   802.7  830.82   822.5  833.81   836.6  843.44   975.2  894.48  1096.7  896.64
#Mann= 7 ,-1,0
       0      .1       0      50     .05       0      90      .1       0
   409.5    .045       0   460.5      .1       0     510     .07       0
     740      .1       0
Bank Sta=409.5,460.5
XS Rating Curve= 0 ,0
Exp/Cntr(USF)=0,0
Exp/Cntr=0.3,0.1

Type RM Length L Ch R = 1 ,47390   ,107.5,112.8,113.8
BEGIN DESCRIPTION:
Structure 17 XS 3
END DESCRIPTION:
XS GIS Cut Line= 6
1654369.50404736373958.5557144541654639.62280172373804.617069498
1654686.09484548373610.0153862511654741.28039744 373331.18312369
1654706.42636462373168.5309705291655290.23141436372840.322161472
#Sta/Elev= 30
       0  861.56    97.2  865.52   164.1  862.01   211.6  851.93   310.9  815.64
   414.3  801.13   545.1  791.82   622.6  776.93   701.2  770.19     749  767.81
   765.8  769.98   842.6  781.91   920.4  781.73   957.5  789.85     982  788.87
   995.7  795.24  1009.9   796.5  1027.8  806.63    1060  808.82  1105.8  837.93
  1189.1  879.76  1247.8   917.6  1275.6  926.04  1303.2  941.75  1330.7  950.59
  1399.5   961.9    1450  985.56  1518.8 1005.25  1569.3 1031.74  1631.4 1045.89
#Mann= 9 ,-1,0
       0     .05       0     220     .06       0  590.98     .05       0
   701.2    .045       0   765.8     .05       0  790.98     .07       0
  887.83     .08       0 1021.66     .07       0 1131.66      .1       0
Bank Sta=701.2,765.8
XS Rating Curve= 0 ,0
Exp/Cntr(USF)=0,0
Exp/Cntr=0.3,0.1

Type RM Length L Ch R = 1 ,47277   ,251.4,271.2,286.3
BEGIN DESCRIPTION:
Structure 17 XS 2
END DESCRIPTION:
XS GIS Cut Line= 6
1654389.83556651374031.1682828291654712.23537009373833.662096848
1654758.70741385373694.2459655671654845.84249591 373371.84616198
1654831.31998223373212.0985115541655345.41696633372918.743735317
#Sta/Elev= 30
       0  849.53   110.6  855.63   198.5  851.78   247.9  840.83   321.7  812.09
   345.1  809.73   388.4  798.26   583.2   786.4   642.7  776.43   717.1   775.1
   752.9  769.25   787.8  767.91   810.6 769.315   825.1  773.71   906.5  778.88
   950.7   789.1   978.8  788.82  1024.9  809.06  1063.7  812.06  1089.4  840.49
  1216.1  917.14  1242.5  927.72  1268.7  944.74  1333.5  960.39  1386.2  985.37
  1457.8 1004.31  1513.1 1033.75    1550 1043.37  1577.6 1056.87  1611.3 1066.62
#Mann= 13 ,-1,0
       0      .1       0      10     .05       0     200     .06       0
     320     .05       0  388.09     .06       0  518.09     .05       0
  692.29     .06       0   752.9    .045       0   810.6     .07       0
  899.02     .05       0  999.02      .1       0 1049.42     .06       0
 1159.42      .1       0
Bank Sta=752.9,810.6
XS Rating Curve= 0 ,0
Exp/Cntr(USF)=0,0
Exp/Cntr=0.3,0.1

Type RM Length L Ch R = 1 ,47006   ,482.4,500,514.6
BEGIN DESCRIPTION:
Structure 17 XS 1
END DESCRIPTION:
XS GIS Cut Line= 6
1654423.58664321374108.0684464451654662.23319434373934.343636841
1654734.96467617373867.0488239231654808.12627526373803.549607083
1654945.01018783373684.7457108351655568.36064717373143.724811256
#Sta/Elev= 30
       0  836.69   137.5  848.06   209.1  844.81     248  838.38   327.3  809.71
   396.9  794.29   575.1  785.03     630  775.28 761.294770.3796     808  767.56
 824.794 770.617   861.8  786.45   881.7  786.88   935.1  818.65   969.6  818.93
   999.6   801.2  1017.8  798.45    1045  798.45  1087.7  812.51  1142.6  841.88
    1167  864.23  1191.4  880.72  1264.5  918.68  1295.2  928.19  1325.7  944.95
  1346.8  946.58  1389.3  959.25  1431.8  984.54  1465.8  996.26  1497.8 1000.56
#Mann= 11 ,-1,0
       0      .1       0      50     .05       0     290     .06       0
  305.18     .05       0  454.27     .06       0  561.15     .05       0
 761.294    .045       0 824.794      .1       0   907.4     .07       0
   952.4     .06       0  1049.9      .1       0
Bank Sta=761.294,824.794
XS Rating Curve= 0 ,0
Exp/Cntr(USF)=0,0
Exp/Cntr=0.3,0.1

Type RM Length L Ch R = 1 ,46506   ,485,500,515.2
XS GIS Cut Line= 6
1654515.54975673374247.8294787321654759.02433933374161.585308343
1654855.07139134374140.0236716721655041.06741042374098.269818172
1655834.59928793373920.1317230021655931.79003842373898.313853249
#Sta/Elev= 30
       0  853.12   174.6  857.34   263.5  854.67   316.8  840.34   410.7  790.55
   566.9  782.44   677.6   781.5726.8083770.5375   782.4  767.05793.9084770.5114
   808.8  781.88   833.4  785.31   853.9   802.8   894.8   826.7   923.5  828.23
   972.4  884.66     985  906.09  1046.5  943.76  1083.7  958.43  1128.5  988.81
  1160.7 1000.02  1212.7 1031.87  1249.2 1046.02  1276.1 1050.51  1296.6 1064.22
  1317.1    1071  1341.5 1087.16    1375 1116.08  1407.3 1134.89  1460.3 1149.81
#Mann= 8 ,-1,0
       0     .05       0     160     .06       0   258.3      .1       0
  567.36     .05       0726.8083    .045       0793.9084     .05       0
  869.86     .07       0  964.86      .1       0
Bank Sta=726.8083,793.9084
XS Rating Curve= 0 ,0
Exp/Cntr(USF)=0,0
Exp/Cntr=0.3,0.1

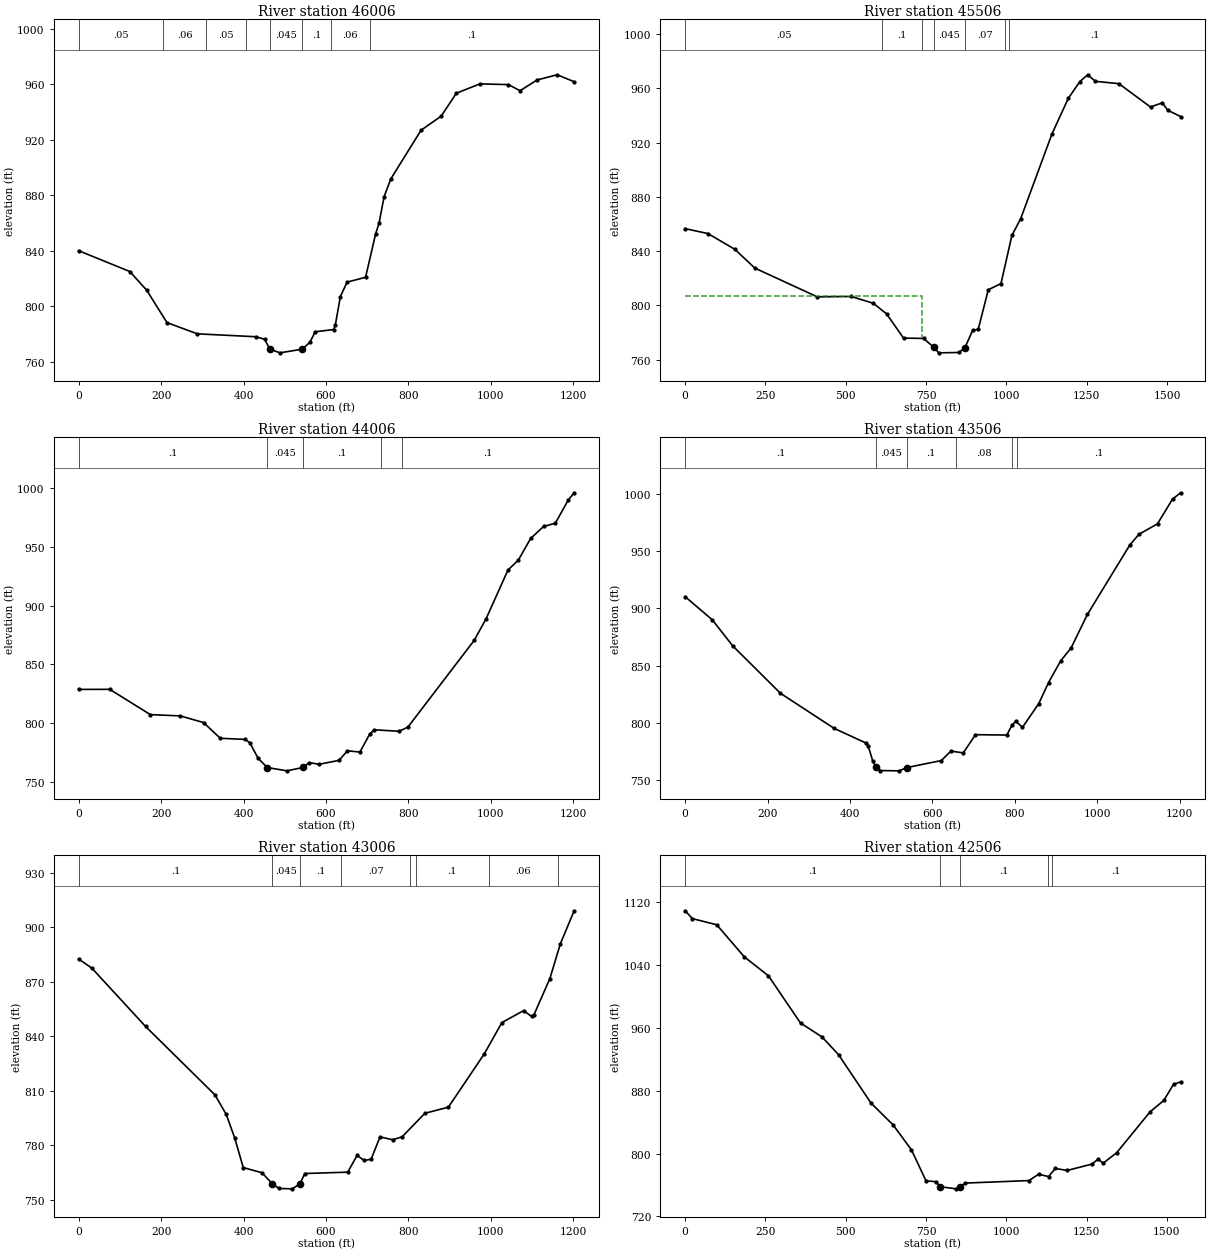
Type RM Length L Ch R = 1 ,46006   ,461.5,500,521.3
XS GIS Cut Line= 6
1654754.66411184374442.8846145121655037.32135493374503.601684675
1655122.91075067374521.8372125031655196.31677184374537.244990096
1655294.41303234374556.6642425951655932.54233351374682.358216926
#Sta/Elev= 30
       0  839.95   124.2  824.94   165.1  811.44   214.2   788.1   287.9  779.99
   430.6  777.88   451.4  775.98463.6933768.9807   488.3  766.28542.7934768.9415
   561.5   774.1   573.7  781.48   618.6  783.07   622.7   786.5   634.9  806.88
   651.2  817.27     696  820.78   720.5  852.22   728.7   859.8   740.9   878.8
   757.3  891.78   830.6  926.84   879.5  937.03   916.2  953.53   973.3  960.26
  1042.6  959.76  1070.7  955.32  1111.9  963.09  1160.8  966.84    1202  961.83
#Mann= 8 ,-1,0
       0     .05       0  205.34     .06       0   309.1     .05       0
  406.62      .1       0463.6933    .045       0542.7934      .1       0
  611.62     .06       0  706.62      .1       0
Bank Sta=463.6933,542.7934
XS Rating Curve= 0 ,0
Exp/Cntr(USF)=0,0
Exp/Cntr=0.3,0.1

Type RM Length L Ch R = 1 ,45506   ,1394.6,1500,1551.2
XS GIS Cut Line= 6
1654515.64540495374342.2063439061654712.74424817374576.889595836
1654783.15486851374669.710932508  1654847.215764374758.162855342
1654905.54471558 374836.105284751655506.68491751 375523.12753275
#Sta/Elev= 30
       0  856.65      71  853.02   154.5  841.45   217.2  827.54   411.4  806.35
   517.3  806.64     586   801.6   627.2  793.79   679.9  775.95   742.2  775.72
773.3629769.3186   789.6  765.09   852.8  765.35 871.243769.0146   895.3  781.84
   912.3  782.33   943.7  811.57   983.2  816.15  1017.2  851.62  1044.7  864.08
  1141.9  926.43  1192.9  952.77  1228.7     965    1253  970.04  1277.3  965.22
  1350.2  963.49  1448.6  946.28  1485.8  949.42  1501.9  943.92  1542.4  939.28
#Mann= 7 ,-1,0
       0     .05       0  612.19      .1       0  737.04    .025       0
773.3629    .045       0 871.243     .07       0  997.04     .06       0
 1007.04      .1       0
#XS Ineff= 2 , 0
          738.46   806.9
Permanent Ineff=
       F       F
Bank Sta=773.3629,871.243
XS Rating Curve= 0 ,0
Exp/Cntr(USF)=0,0
Exp/Cntr=0.3,0.1

Type RM Length L Ch R = 1 ,44006   ,507.4,500,492.4
XS GIS Cut Line= 6
1654247.81440376 374142.123405011654093.33078884374261.629727677
1653949.96952701374372.5310806781653683.02157009374579.037885502
1653375.90833917374816.6164785921653297.12109518374877.564191341
#Sta/Elev= 30
       0  828.63    75.5   828.7   173.9   807.2   246.7  806.09   303.1  800.41
   343.5  787.06   403.6  786.11     415  783.39   435.4  770.02457.7254762.1767
   505.3  759.36543.8754 762.216   559.6  766.36   583.2  764.93   631.7  768.29
     652  776.42   682.3  775.33   705.8  790.45   717.2   794.3   777.1     793
   798.7  796.58   959.6  870.41   988.1  888.55  1041.4  930.18  1066.7  938.69
  1096.4  957.06  1127.8  967.22  1156.3  970.01  1187.7  989.79    1202   995.9
#Mann= 5 ,-1,0
       0      .1       0457.7254    .045       0543.8754      .1       0
  734.06     .06       0  784.06      .1       0
Bank Sta=457.7254,543.8754
XS Rating Curve= 0 ,0
Exp/Cntr(USF)=0,0
Exp/Cntr=0.3,0.1

Type RM Length L Ch R = 1 ,43506   ,492,500,508.3
XS GIS Cut Line= 6
  1653820.615455373745.9434230921653754.01027326373818.425889671
1653515.07669601374078.4411176741653274.02862167 374340.75785026
1653141.87501459   374484.5715391653007.34313142374630.974133343
#Sta/Elev= 30
       0  910.37    65.8  890.15   115.4  867.33   231.3  825.78   361.7  795.06
   438.2  782.34   444.1  779.73   455.1  766.65463.6339760.9252   473.7  758.17
   519.6  757.94537.2339760.7487   621.5  766.95   644.8  775.24   674.7  773.62
   704.3  789.57   780.4  789.26   792.9  797.87   802.1  801.29   818.4  796.02
   857.9  816.79   881.6   835.2   910.9  854.08   936.4  865.53     976   894.9
  1079.1  955.75  1100.9  964.91  1145.9  974.07  1182.3  995.71    1202 1001.23
#Mann= 6 ,-1,0
       0      .1       0463.6339    .045       0537.2339      .1       0
  656.56     .08       0  794.06     .06       0  804.06      .1       0
Bank Sta=463.6339,537.2339
XS Rating Curve= 0 ,0
Exp/Cntr(USF)=0,0
Exp/Cntr=0.3,0.1

Type RM Length L Ch R = 1 ,43006   ,509.4,500,489.8
XS GIS Cut Line= 6
1653550.26855476373477.6670567541653469.27298184373533.634464502
1652879.03728567373927.1251473431652798.43278809373980.862244591
1652716.52776818374035.465153754 1652551.0927316374145.755287498
#Sta/Elev= 30
       0  882.46    31.8   877.5   162.3  845.37   330.6  807.73   358.1  796.92
   378.7  783.94   399.3  767.71   444.6  764.88469.9897758.7625   485.9  756.23
   518.1  756.01536.8896758.7258   548.5  764.44   652.7  765.18   675.4  774.36
   692.7  771.64   709.4  772.25     731  784.59   761.9  783.03     785  784.69
   839.8  797.57   896.9  800.94     984  830.28  1026.7   847.5  1079.2  854.04
  1098.8  850.84  1104.6  851.86  1143.1  871.72  1168.6   890.9    1202     909
#Mann= 8 ,-1,0
       0      .1       0469.9897    .045       0536.8896      .1       0
  636.58     .07       0  804.08     .06       0  817.83      .1       0
   994.7     .06       0 1162.36      .1       0
Bank Sta=469.9897,536.8896
XS Rating Curve= 0 ,0
Exp/Cntr(USF)=0,0
Exp/Cntr=0.3,0.1

Type RM Length L Ch R = 1 ,42506   ,523.1,500,476.1
XS GIS Cut Line= 6
1653011.34246726372729.8476862611653136.70770209372907.492016003
1653105.05192551373008.6781653311652595.65366609373635.634916678
 1652497.4232195373808.2904112491652417.33184426374005.023941666
#Sta/Elev= 30
       0 1109.44    22.9 1099.47    98.5 1091.57   184.4 1050.68   259.6 1026.48
   359.3  966.33   426.4  948.57   477.9  925.91   578.7  864.33     648  836.25
   704.7   804.6   749.9  765.25     782  763.96   793.2  757.73   843.8  754.95
   855.8   757.6   872.8  762.31  1070.6  765.47  1100.3  773.56  1131.6  770.58
  1152.4  780.89  1189.6  778.42  1265.7  786.39  1285.9  792.67  1301.6  787.64
  1343.7  801.05  1447.5  853.07  1490.5  867.74  1520.6  888.22  1542.7  891.25
#Mann= 5 ,-1,0
       0      .1       0   793.2    .045       0   855.8      .1       0
 1131.26     .07       0 1141.26      .1       0
Bank Sta=793.2,855.8
XS Rating Curve= 0 ,0
Exp/Cntr(USF)=0,0
Exp/Cntr=0.3,0.1

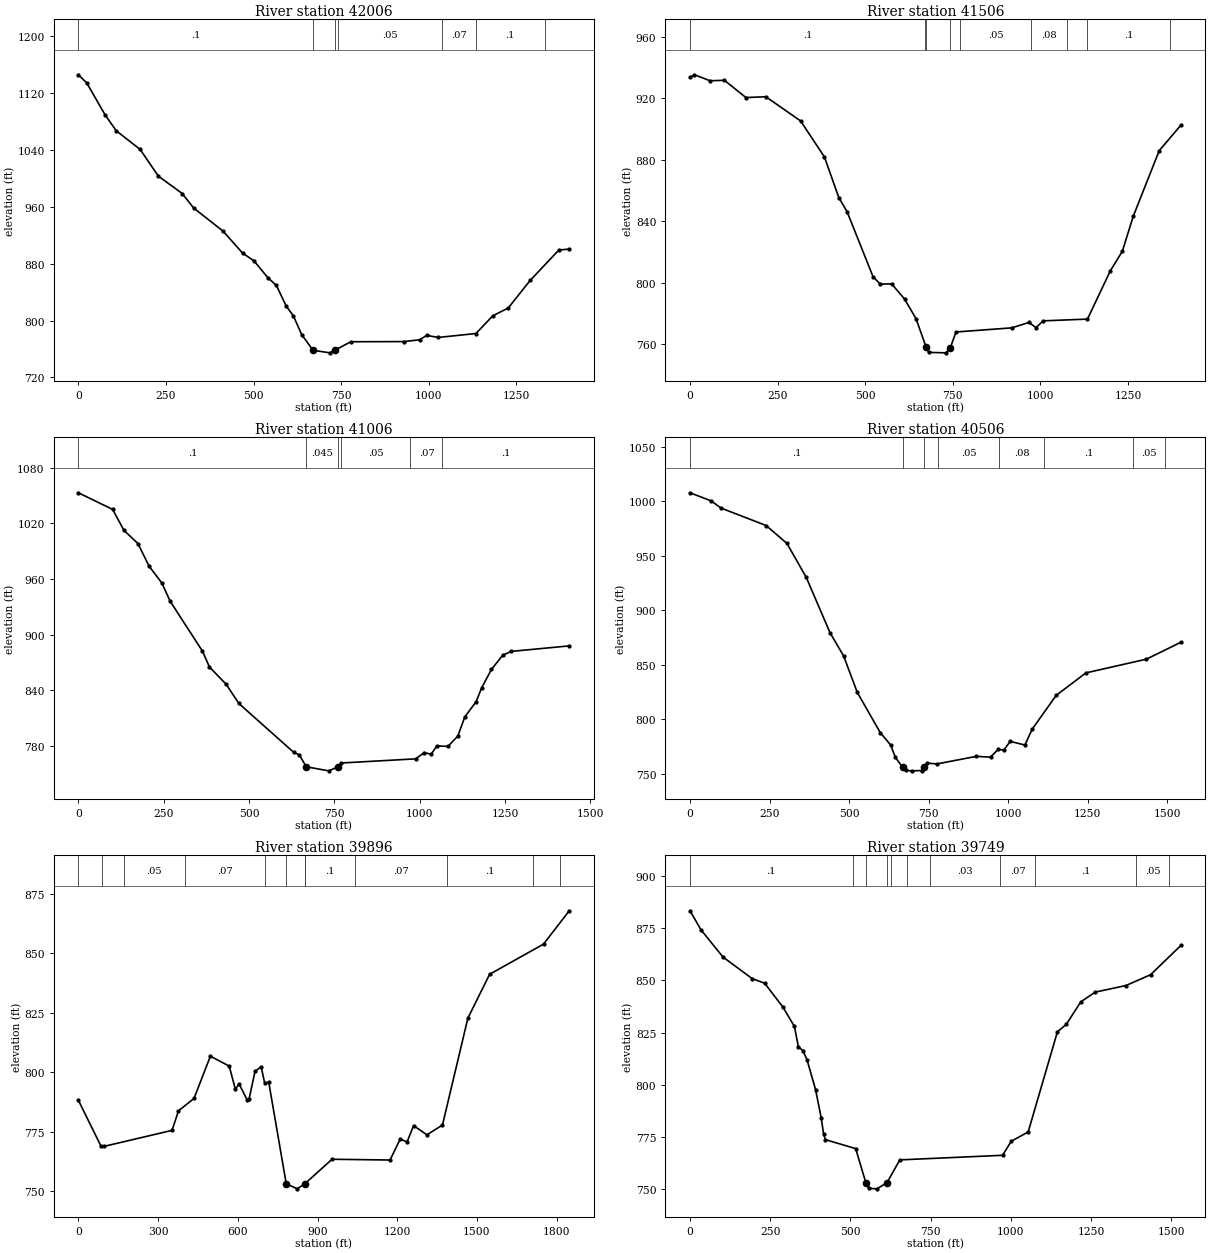
Type RM Length L Ch R = 1 ,42006   ,503.6,500,495.3
XS GIS Cut Line= 6
1652264.37644151372608.8000280861652271.36330417372708.163674504
1652322.26937035373432.1576333341652341.77753343373709.597695261
1652355.64069468373906.7672484221652362.62788543374006.131222919
#Sta/Elev= 30
       0 1145.63    23.8 1134.18    75.9 1089.47     108  1066.9   176.2 1040.66
   228.3 1003.07   296.5  978.64   328.5  958.41   412.8  925.77   468.9  894.68
     501  884.03   541.1  859.99   565.1  849.39   593.2  820.18   613.2  806.91
   637.3  780.31   669.4  758.22   717.5   754.6  731.34758.1982   777.7  770.21
     930  770.43   974.1  773.02   994.2  779.19  1026.3  776.23  1134.5  781.75
  1182.6  806.66  1226.8  817.72  1289.6  856.63  1371.1  899.18  1400.8  900.49
#Mann= 7 ,-1,0
       0      .1       0   669.4    .045       0  731.34      .1       0
  740.39     .05       0 1036.64     .07       0 1133.52      .1       0
 1331.17     .06       0
Bank Sta=669.4,731.34
XS Rating Curve= 0 ,0
Exp/Cntr(USF)=0,0
Exp/Cntr=0.3,0.1

Type RM Length L Ch R = 1 ,41506   ,501.1,500,498.5
XS GIS Cut Line= 6
1651680.88745101372684.2506645921651842.75917451373493.612891003
1651878.30503517373671.3435066791651897.30335675373766.337083086
1651936.06673068373960.155265003 1651955.6017966374057.830266505
#Sta/Elev= 30
       0  933.57    12.5  935.25    57.4  931.36    98.2  931.67   159.4  920.45
   216.5  920.96   315.7   905.2   383.6   881.8   424.5  855.44   448.3  846.15
   522.4  803.89   542.8  799.14   575.5  799.25   612.2  789.44   644.8  776.74
  674.13757.9317   681.5  754.73   730.3  754.44   742.7  757.66     759     768
   918.1  770.69   967.1  774.18   987.5  770.84  1007.9  775.25  1134.3  776.38
  1199.4  807.74  1233.6  820.39  1264.8   843.2  1338.9  885.87  1400.8  902.48
#Mann= 9 ,-1,0
       0      .1       0  670.39    .025       0  674.13    .045       0
   742.7    .025       0  770.39     .05       0  972.89     .08       0
 1076.64     .07       0 1133.52      .1       0 1371.17     .07       0
Bank Sta=674.13,742.7
XS Rating Curve= 0 ,0
Exp/Cntr(USF)=0,0
Exp/Cntr=0.3,0.1

Type RM Length L Ch R = 1 ,41006   ,509.8,500,484.5
XS GIS Cut Line= 6
1651167.94884434372794.8747871671651213.82178409372988.338967174
1651236.53269668 373084.120927841651400.19673942373774.357736334
1651468.15001559374060.9427930861651580.19834793374139.655890256
#Sta/Elev= 30
       0 1052.95   100.4 1035.01   133.3 1012.53   174.4  998.22   207.3  973.74
   244.3  955.83   268.9  936.04   363.5  882.21     384  865.14   433.4  846.33
   470.1  825.84   630.7  773.22   647.1  770.48   667.7   757.6   733.4  753.23
   759.2  757.25   770.4  761.69   988.3  766.16    1013  772.85  1033.5  771.16
    1050     780  1082.9  779.65  1111.7   790.7  1132.2  811.47  1165.1  827.58
  1181.5  842.72  1210.3  862.62  1243.2   877.8  1267.9  881.97  1438.1  887.92
#Mann= 6 ,-1,0
       0      .1       0   667.7    .045       0   759.2      .1       0
  770.39     .05       0  972.89     .07       0 1066.64      .1       0
Bank Sta=667.7,759.2
XS Rating Curve= 0 ,0
Exp/Cntr(USF)=0,0
Exp/Cntr=0.3,0.1

Type RM Length L Ch R = 1 ,40506   ,668.2,609.6,561.6
BEGIN DESCRIPTION:
Structure 16 XS 4
END DESCRIPTION:
XS GIS Cut Line= 6
1650515.31727558373079.5166063461651035.35823026373941.423019007
1651087.28857259   374023.2338791651140.84686442 374105.88725701
1651235.24332917374164.8375984281651463.74516876374191.603621006
#Sta/Elev= 30
       0    1008    66.6 1000.51    97.5  993.95   239.4  977.92   304.8  961.43
   365.5  930.28   440.2  879.42     483   858.1   525.8  824.68     598  787.74
   630.7  776.32   645.8   764.9   668.6  755.77   678.5   752.9   698.8  752.56
   729.7  752.87  736.17756.0813   744.4  759.62     777  758.93   900.2  765.86
   944.8  765.13   968.7  772.23   986.9  771.63  1006.5  779.62    1053  776.29
  1076.1  790.95  1151.4  821.91  1244.8  842.53    1435  855.14  1543.4  870.67
#Mann= 8 ,-1,0
       0      .1       0   668.6    .045       0  736.17      .1       0
  780.39     .05       0  972.89     .08       0 1113.54      .1       0
 1393.32     .05       0 1493.32      .1       0
Bank Sta=668.6,736.17
XS Rating Curve= 0 ,0
Exp/Cntr(USF)=0,0
Exp/Cntr=0.3,0.1

Type RM Length L Ch R = 1 ,39896   ,141.9,146.9,144
BEGIN DESCRIPTION:
Structure 16 XS 3
END DESCRIPTION:
XS GIS Cut Line= 6
1649943.59331778374641.1683029961650083.63725732374641.416899385
1650483.25085538374183.4905874451650829.69697902373955.384971385
1651237.88597618374176.6302681651651452.27095368374200.641385645
#Sta/Elev= 30
       0  788.16    84.5     769    96.5  768.79   352.5  775.52   376.6  783.73
   435.2  788.97   496.8  806.74   567.7  802.56   590.6   792.9     605  795.03
   635.9  788.16     642  788.52   664.9  800.41   687.8  802.27   701.2  795.43
   716.4  795.81  782.27753.0626   823.6  750.91   852.2  753.03   954.6  763.36
    1173  763.04  1211.3  771.91    1237  770.62  1261.5  777.53  1311.7  773.63
  1370.3  777.77  1465.9  822.77  1547.7  841.21  1750.7  853.92  1847.4  867.95
#Mann= 12 ,-1,0
       0     .05       0      90     .06       0  170.04     .05       0
  400.38     .07       0  701.49      .1       0  782.27    .045       0
   852.2     .08       0  852.22      .1       0 1041.78     .07       0
  1387.4      .1       0  1711.7     .05       0  1811.7      .1       0
Bank Sta=782.27,852.2
XS Rating Curve= 0 ,0
Exp/Cntr(USF)=0,0
Exp/Cntr=0.3,0.1

Type RM Length L Ch R = 1 ,39749   ,352.3,358.3,372.8
BEGIN DESCRIPTION:
Structure 16 XS 2
END DESCRIPTION:
XS GIS Cut Line= 6
1650372.90568866374770.8966687191650366.62542762374560.808147845
1650454.09449844374373.8644474651650942.89224714374065.150079865
1651232.74073672374190.3509067251651450.55587386374207.501704925
#Sta/Elev= 30
       0   883.4    34.1  874.29   102.4  861.28   193.5  850.92   232.6  848.69
   289.2  837.31   325.3     828   337.9  818.13   351.8  816.46   364.7  812.01
   391.5  797.58   409.2  783.93   416.1  776.61   421.8  773.77   516.4  769.45
   547.9  753.15   557.3  750.42   582.3  750.19   613.8  753.11   653.9  764.06
   974.1  766.26  1001.3  772.99  1053.9  777.43  1145.1  825.42  1172.6  828.97
  1218.2  839.81  1262.8  844.42  1358.9   847.6  1435.6  852.78  1529.9  866.79
#Mann= 11 ,-1,0
       0      .1       0  506.58     .07       0   547.9    .045       0
   613.8     .07       0  626.58      .1       0  676.58     .07       0
  746.96     .03       0  966.96     .07       0 1075.64      .1       0
 1391.37     .05       0 1491.37      .1       0
Bank Sta=547.9,613.8
XS Rating Curve= 0 ,0
Exp/Cntr(USF)=0,0
Exp/Cntr=0.3,0.1

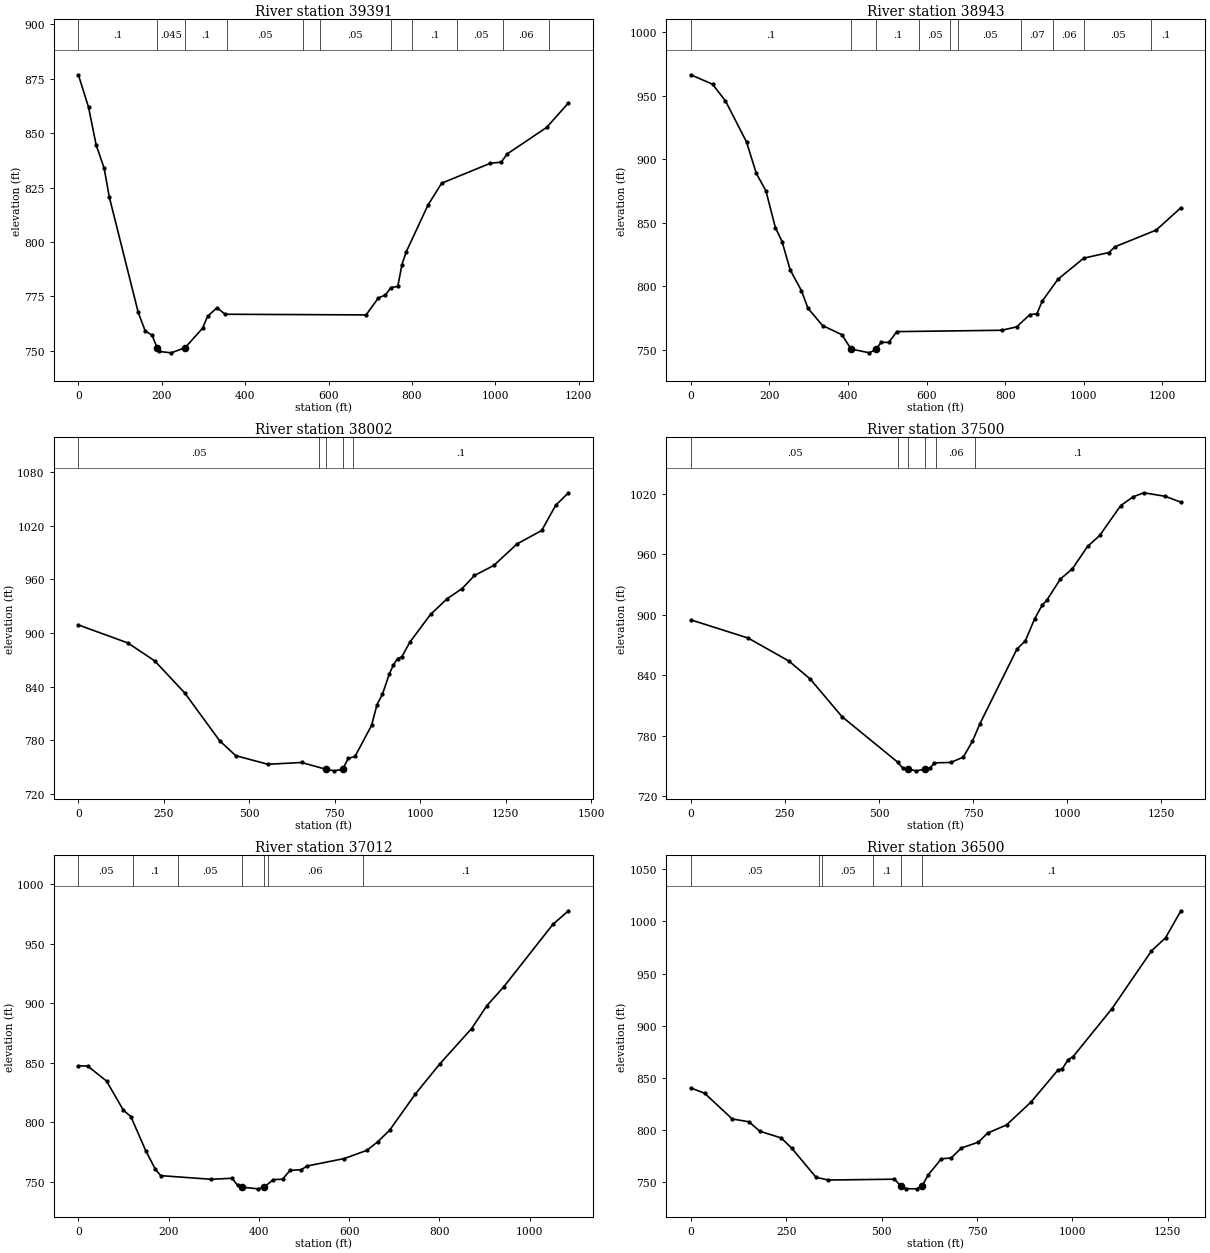
Type RM Length L Ch R = 1 ,39391   ,484.7,447.9,415.1
BEGIN DESCRIPTION:
Structure 16 XS 1
END DESCRIPTION:
XS GIS Cut Line= 4
1650410.31000182374751.1294492751650509.64399536 374657.02356066
1650742.29466443374589.058196661 1651450.7028815 374225.70490451
#Sta/Elev= 30
       0  876.86    24.5  861.86    42.7  844.56    61.9  833.88    74.1  820.74
   143.6  767.56   160.2  759.14   176.9  757.06  188.69751.4324     194  749.65
   222.7  749.01   256.1  751.39   297.8  760.33   310.1  765.89   332.7  769.74
   351.9  766.75     690  766.45   719.7  774.31   736.4  775.58   749.4  779.05
     766  779.52   776.1   789.6   785.8  795.25   838.5  816.95   871.2     827
   988.1  836.18  1013.9  836.68  1028.6  840.48    1123  852.64  1175.4  863.93
#Mann= 11 ,-1,0
       0      .1       0  188.69    .045       0   256.1      .1       0
  356.83     .05       0  539.21     .03       0  579.21     .05       0
  749.21     .06       0  799.21      .1       0  909.21     .05       0
 1019.21     .06       0 1129.21      .1       0
Bank Sta=188.69,256.1
XS Rating Curve= 0 ,0
Exp/Cntr(USF)=0,0
Exp/Cntr=0.3,0.1

Type RM Length L Ch R = 1 ,38943   ,910.1,941.6,980.3
XS GIS Cut Line= 3
1650860.56841578375274.2813529651651021.78591886374612.260542445
1651474.56699134374272.674738085
#Sta/Elev= 30
       0  966.29    55.3  958.89    88.3  945.72   141.8  913.49   166.6  888.93
   191.2  875.05   215.2  846.29   232.3  835.17   252.9  812.96   281.7  796.61
   298.2  782.81   335.3  769.27   384.7  762.01   407.7750.8408   454.6  747.81
   471.4  750.62   484.4  756.01   504.1  756.04   524.2  764.48   791.4  765.55
   829.3  768.22   862.8  777.83   880.9  778.53   894.2  788.36   934.2  805.59
    1000  822.21  1064.3  826.64  1079.3  831.13  1184.3  844.25  1247.3  861.81
#Mann= 10 ,-1,0
       0      .1       0   407.7    .045       0   471.4      .1       0
     580     .05       0     660     .08       0     680     .05       0
  841.37     .07       0  921.37     .06       0 1001.37     .05       0
 1171.37      .1       0
Bank Sta=407.7,471.4
XS Rating Curve= 0 ,0
Exp/Cntr(USF)=0,0
Exp/Cntr=0.3,0.1

Type RM Length L Ch R = 1 ,38002   ,500.7,501.5,502.4
XS GIS Cut Line= 6
1651084.64225243375508.4572865071651419.22458851375306.424226001
1651521.96290009375250.3534720091651615.52406467375214.353872091
1651690.47962342375218.1179721651652438.04965059375283.121779174
#Sta/Elev= 30
       0  908.99   144.8  888.84   223.7  868.72   311.2  832.98   413.5  779.49
   460.2  762.97   554.3  753.32   652.8  755.31724.9761747.6613   748.3  745.99
773.1762747.7731   789.2  759.78   809.3  762.14   857.5  796.65   873.5  819.78
   889.6   831.8   909.7  854.38   921.7   864.4   933.8  871.43   945.8  873.24
   969.9  889.84  1030.1  920.71  1078.3  938.11  1122.5  949.59  1158.6  964.23
  1215.2  975.41  1283.1  999.44  1355.4 1014.51  1396.2 1042.66  1433.6 1056.61
#Mann= 5 ,-1,0
       0     .05       0   703.2     .07       0724.9761    .045       0
773.1762     .07       0   803.2      .1       0
Bank Sta=724.9761,773.1762
XS Rating Curve= 0 ,0
Exp/Cntr(USF)=0,0
Exp/Cntr=0.3,0.1

Type RM Length L Ch R = 1 ,37500   ,482.9,487.8,490
XS GIS Cut Line= 6
1651060.75581726375650.098407418 1651608.2560346375708.916859344
1651707.51206967375721.1396039281652156.10762918375775.438707918
1652254.42829867375790.3395967481652353.53735243375804.760499671
#Sta/Elev= 30
       0  895.09   152.2  877.04   260.9  854.13   317.2  836.36   401.7     799
   550.2  753.69   562.6  748.18576.2505746.9208   598.9  745.23623.0205746.9347
   635.1  747.77   647.2  753.16   690.2  753.53   723.8   758.8     748  774.42
   768.1  791.97   866.3  865.92     889   874.4   913.2  895.89   933.3  909.59
   945.4  914.35   981.6  935.45  1013.9  945.83  1054.2  968.02  1086.4  978.83
  1142.1 1008.48  1175.4 1017.27  1203.7 1021.21  1260.3 1017.71  1302.1 1011.86
#Mann= 6 ,-1,0
       0     .05       0  550.65      .1       0576.2505    .045       0
623.0205      .1       0  650.65     .06       0  755.71      .1       0
Bank Sta=576.2505,623.0205
XS Rating Curve= 0 ,0
Exp/Cntr(USF)=0,0
Exp/Cntr=0.3,0.1

Type RM Length L Ch R = 1 ,37012   ,495.5,512.3,520.4
XS GIS Cut Line= 4
1651300.00557788376096.102057653 1651964.4632221376279.681067812
1652155.84732527376443.7604834531652263.88540568376539.468243305
#Sta/Elev= 30
       0  847.68    20.9  847.31    62.4  834.84    99.7  810.36   116.3  804.98
   149.5  776.12   170.3  760.97   182.5  755.38   294.8   752.3   340.4  753.18
   352.9  747.15363.1913745.6564   398.5  744.29  411.21745.6028   431.7  751.99
   452.4  752.43     469  759.81   493.9  760.35   506.4  763.44   589.4  769.76
   639.2  776.61   663.8  784.02   689.4  793.42   746.4  823.83   800.3     849
   871.3  878.93   905.3  898.24   942.2  913.83  1051.2  966.34  1085.8  977.79
#Mann= 7 ,-1,0
       0     .05       0     120      .1       0     220     .05       0
363.1913    .045       0  411.21      .1       0     420     .06       0
     630      .1       0
Bank Sta=363.1913,411.21
XS Rating Curve= 0 ,0
Exp/Cntr(USF)=0,0
Exp/Cntr=0.3,0.1

Type RM Length L Ch R = 1 ,36500   ,455.8,500,538.3
XS GIS Cut Line= 6
1651277.86312363 376156.165509691651295.55056585376460.705467928
1651398.10225542376575.1966228341651790.65527609376928.492832258
1651863.10723092  376995.13935251652004.49047834377135.264728427
#Sta/Elev= 30
       0  840.19    36.4  835.02   108.6  810.41   152.6  807.67   180.7  798.63
   236.8  792.17   264.8  782.22     328  754.44   359.9  751.77   533.8  752.56
550.4509745.9584   563.7  743.47   592.3  743.31605.5508745.9235   622.9  757.05
   656.6  772.13   682.1  772.94     709   782.5   753.8  788.12   777.7  796.83
   827.4  804.65   891.3  826.52   961.9  857.26   973.8  858.67   988.9  867.34
  1002.1  870.34    1104  916.43  1207.1  971.66  1244.2  984.38  1284.4 1010.27
#Mann= 6 ,-1,0
       0     .05       0  335.05      .1       0  345.05     .05       0
  478.76      .1       0550.4509    .045       0605.5508      .1       0
Bank Sta=550.4509,605.5508
XS Rating Curve= 0 ,0
Exp/Cntr(USF)=0,0
Exp/Cntr=0.3,0.1

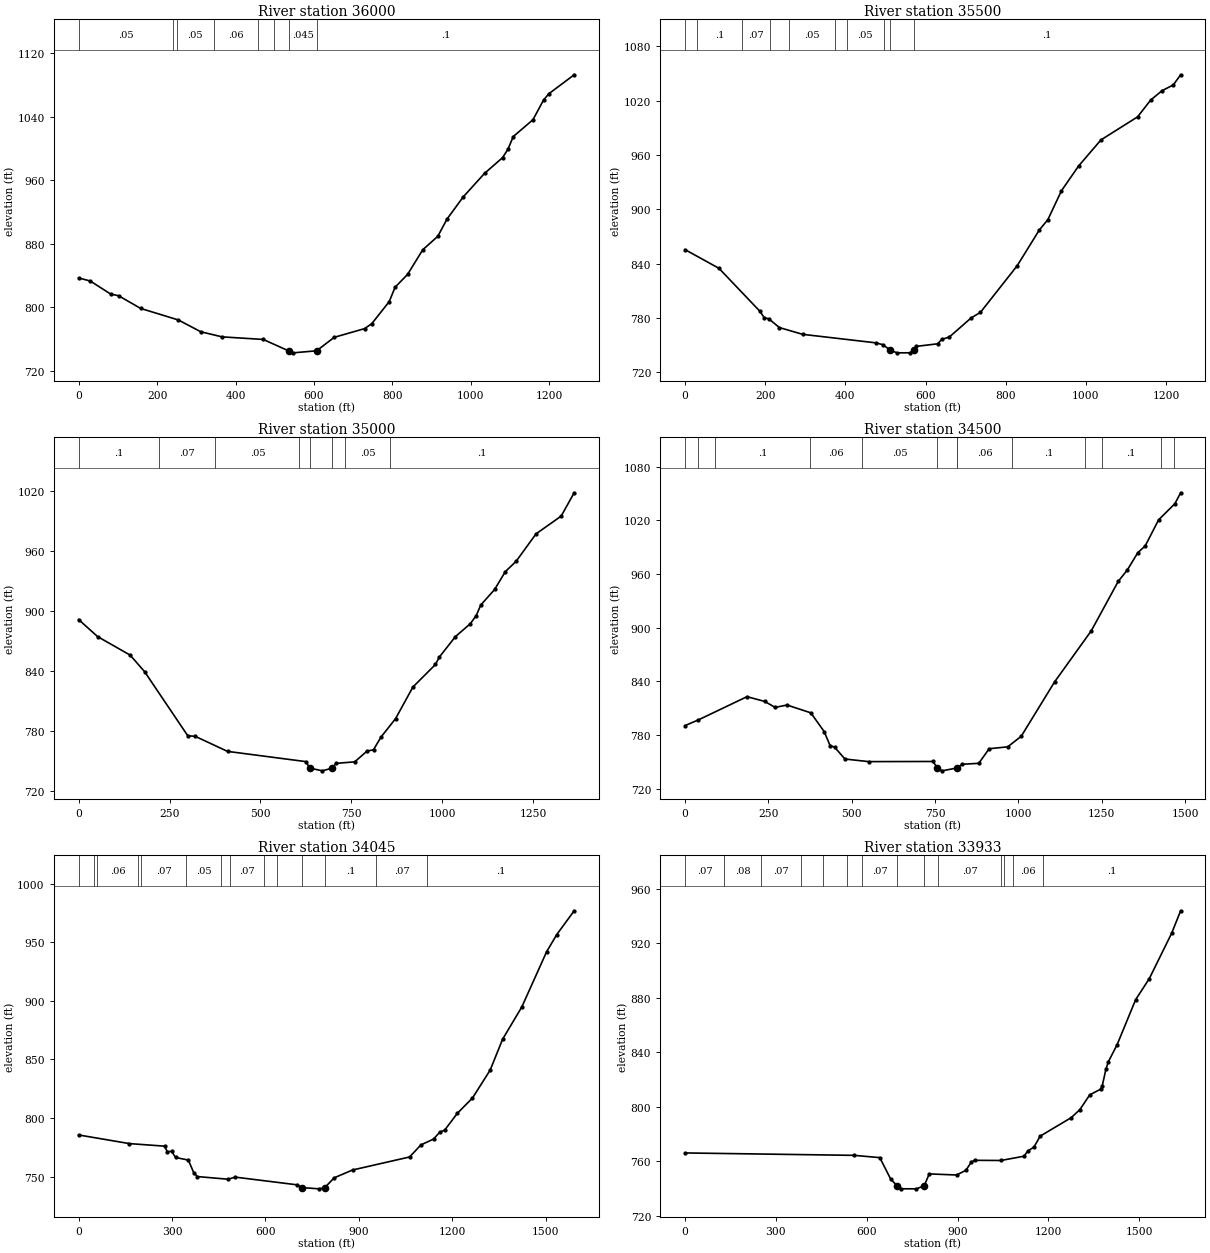
Type RM Length L Ch R = 1 ,36000   ,498.8,500,502
XS GIS Cut Line= 6
1651233.09685518376151.157954089  1651211.026186376404.621832758
1651183.52853759376496.4749955091651021.10333751376792.320204332
1650978.99285743376869.020510256 1650744.1905055377296.694851756
#Sta/Elev= 30
       0  836.91    29.5   833.1    81.7  816.61   101.8  814.56     158  798.59
   254.3  784.03   311.3  769.21   365.7  762.78   470.7  759.52536.2164 744.943
   546.6  742.68606.6965745.2485   651.5  762.21   729.1  773.18   747.4  779.45
   791.8   807.2   806.7  825.23   838.6  841.42   877.2  872.38   915.5  889.24
     939  910.96   980.3  938.85  1034.9  968.61  1080.5  988.18  1094.2   998.7
  1107.9  1014.8  1158.1    1036  1185.4 1060.99  1199.1 1068.88  1263.2 1092.57
#Mann= 8 ,-1,0
       0     .05       0     240     .06       0     250     .05       0
  344.42     .06       0   457.8     .05       0   497.8      .1       0
536.2164    .045       0606.6965      .1       0
Bank Sta=536.2164,606.6965
XS Rating Curve= 0 ,0
Exp/Cntr(USF)=0,0
Exp/Cntr=0.3,0.1

Type RM Length L Ch R = 1 ,35500   ,496.5,500,504.5
XS GIS Cut Line= 6
1650933.79262233375977.2228550571650860.15976176376087.676600501
1650809.47908884376170.2371309251650675.42095801376388.623177096
1650438.36631401376774.7933365111650282.85054892377028.134365261
#Sta/Elev= 30
       0  855.43    84.4  834.84   186.4   787.5   197.4  780.35     209  779.02
   235.2  769.41   293.3  761.94   476.4  752.52     494  750.42512.0489744.3096
   528.9  741.51   560.9  741.56570.2488744.3589   576.3  748.63   629.8  751.47
   640.7  756.37   659.4  759.02   713.9  780.14   736.9  786.21   828.5  837.66
   883.7  877.12   905.1  888.57     939  920.46   981.5  947.64  1037.4  976.52
  1128.8 1001.98  1161.6 1020.59  1189.8 1030.86    1218 1037.26  1236.3 1048.46
#Mann= 10 ,-1,0
       0     .05       0      30      .1       0  142.75     .07       0
  212.75     .06       0  259.62     .05       0  373.37     .06       0
  403.37     .05       0  495.87      .1       0512.0489    .045       0
570.2488      .1       0
Bank Sta=512.0489,570.2488
XS Rating Curve= 0 ,0
Exp/Cntr(USF)=0,0
Exp/Cntr=0.3,0.1

Type RM Length L Ch R = 1 ,35000   ,506.2,500,492.6
XS GIS Cut Line= 6
1650659.91484211 375632.922385381650619.83478309375679.601301178
1650557.16069584375756.5191263411650494.98070209375832.831309676
1650271.92078076376106.5860114991649797.91943218376688.314834923
#Sta/Elev= 30
       0  891.64    52.2  874.61   141.6  856.12   181.4  839.56   300.1   775.5
   320.8   774.9   409.4  759.88   624.9  749.65635.4561743.1761   670.4  740.43
697.3561743.2138   707.7   747.9   759.3  749.42   792.7  760.09   810.9  761.53
   831.5   774.2   871.6  792.63   919.2  824.19   981.2  846.73   991.9  854.14
  1036.3  874.68    1077  887.44  1093.3  895.59  1105.9  906.21  1143.9   921.7
  1173.6  939.66    1203  949.85  1257.9  977.34  1326.9  995.05  1362.7 1018.38
#Mann= 8 ,-1,0
       0      .1       0  220.74     .07       0  376.06     .05       0
  607.31      .1       0635.4561    .045       0697.3561      .1       0
  732.31     .05       0  857.31      .1       0
Bank Sta=635.4561,697.3561
XS Rating Curve= 0 ,0
Exp/Cntr(USF)=0,0
Exp/Cntr=0.3,0.1

Type RM Length L Ch R = 1 ,34500   ,436.9,454.5,470.1
BEGIN DESCRIPTION:
Structure 15 XS 4
END DESCRIPTION:
XS GIS Cut Line= 6
1649986.87345059375182.4435028431650083.87784976375340.862477332
1650040.00818685375429.8557376711649796.13269034375924.573908344
1649596.47298467376329.5980326681649508.56075892376507.934946343
#Sta/Elev= 30
       0  790.72      40   797.1   185.8  823.03   238.9  817.71   270.1  811.05
   305.8  813.69   377.2  804.97   417.3  784.03   435.1  768.28   448.5  766.63
   479.7  753.35   551.1  750.45   743.9  750.61   757.3  743.16   770.8  740.15
   815.6  743.32     832  747.52   881.1  748.53   912.3  764.84     968  766.97
  1008.5  778.75  1108.5  839.43  1218.9  896.69  1299.5  951.76  1327.1   964.7
  1358.3  983.89  1380.6  991.48  1420.7 1020.56  1469.8 1038.72  1486.9 1050.85
#Mann= 13 ,-1,0
       0      .1       0      40     .05       0      90      .1       0
  374.98     .06       0  530.29     .05       0   757.3    .045       0
   815.6     .05       0  816.54     .06       0  981.54      .1       0
 1199.67     .08       0 1249.67      .1       0 1427.32     .08       0
 1467.32      .1       0
Bank Sta=757.3,815.6
XS Rating Curve= 0 ,0
Exp/Cntr(USF)=0,0
Exp/Cntr=0.3,0.1

Type RM Length L Ch R = 1 ,34045   ,102.2,112.4,113.5
BEGIN DESCRIPTION:
Structure 15 XS 3
END DESCRIPTION:
XS GIS Cut Line= 6
1649967.01182956375173.091643585 1649713.1800162375408.057578925
1649486.78947996375625.8727160661649294.70054012375763.079101666
1649159.20923434375835.1124541061649234.67274642376371.932437766
#Sta/Elev= 30
       0   785.6     163  778.23   275.9  776.06   284.7  771.38   298.9  771.61
   311.3  766.38   352.4   764.2   369.6  753.51   381.2  750.12   480.6  747.84
   502.6  749.65   701.1   743.1   718.9  740.69   772.3  739.65  790.56740.6703
   820.8  749.05   879.9  755.72  1063.1  766.83  1099.5  777.13  1139.9  782.06
  1160.1  788.05  1175.6  789.66  1216.6  804.11  1265.1  817.11  1321.7  840.83
    1362  867.33  1423.5  894.75  1503.4  941.95  1535.7  956.46  1591.7  976.78
#Mann= 14 ,-1,0
       0      .1       0      50     .07       0      60     .06       0
     190     .08       0     200     .07       0  345.89     .05       0
  455.89     .08       0  485.89     .07       0  595.89     .08       0
  635.89     .05       0   718.9    .045       0  790.56      .1       0
  956.13     .07       0 1119.58      .1       0
Bank Sta=718.9,790.56
XS Rating Curve= 0 ,0
Exp/Cntr(USF)=0,0
Exp/Cntr=0.3,0.1

Type RM Length L Ch R = 1 ,33933   ,491.3,433,394.2
BEGIN DESCRIPTION:
Structure 15 XS 2
END DESCRIPTION:
XS GIS Cut Line= 6
1649831.52052378375111.348770065 1649661.7276216375339.454386125
1649409.61088806375570.9901618261649219.23702804375697.906068506
1649046.01396622375769.939420946 1649172.9298729376349.636400106
#Sta/Elev= 30
       0  765.96     558  764.19     643  762.53   678.9   746.8   700.1  741.89
   714.2  739.64   764.1   739.6     790  741.94   806.2  750.56   896.7  749.77
   927.3  753.19   945.4  759.29   956.1  760.55  1043.1  760.42  1119.5  763.58
  1131.8  767.37  1152.3  770.28  1172.7  778.31  1275.1  791.86  1303.8  797.79
  1336.5  808.64  1373.4  812.91  1377.5  814.99  1389.7  827.39  1397.9  832.97
  1426.7  845.41    1488  878.52  1533.1  893.99  1606.8  927.25  1636.6  943.81
#Mann= 14 ,-1,0
       0     .07       0     130     .08       0     250     .07       0
  384.36     .08       0  454.36      .1       0  534.36     .08       0
  584.36     .07       0   700.1    .045       0     790     .08       0
  835.54     .07       0 1043.14     .05       0 1053.14     .07       0
 1083.14     .06       0 1183.14      .1       0
Bank Sta=700.1,790
XS Rating Curve= 0 ,0
Exp/Cntr(USF)=0,0
Exp/Cntr=0.3,0.1