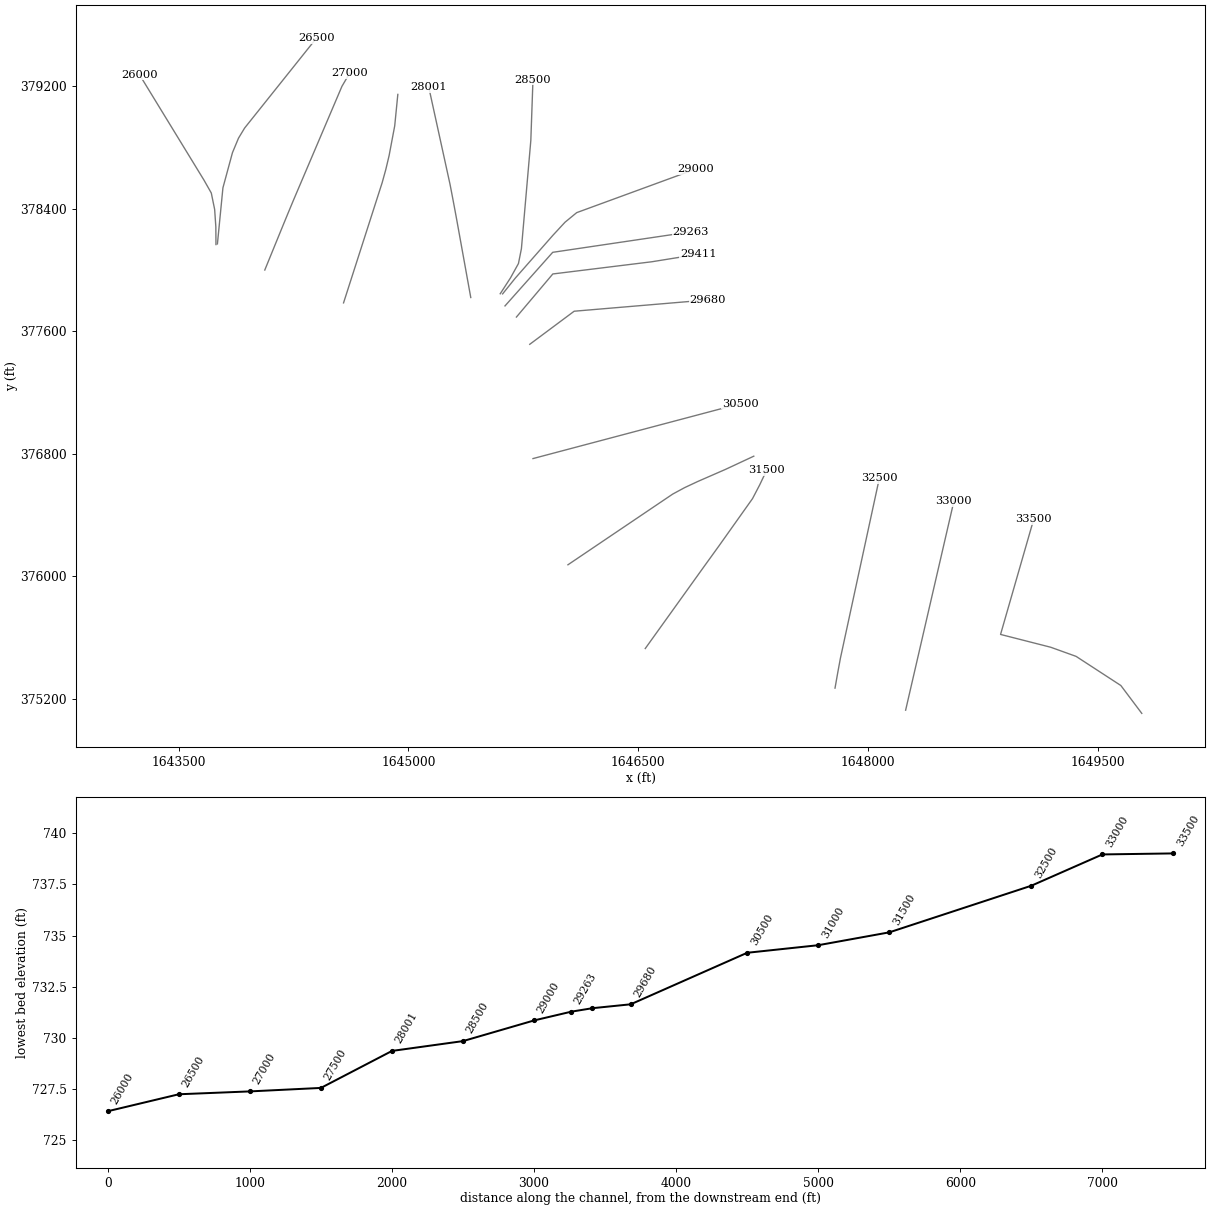
HEC-RAS study SFFSHGCK.prj: SFFSHGCK

--- SFFSHGCK.g01 (geometry) --- (continued)

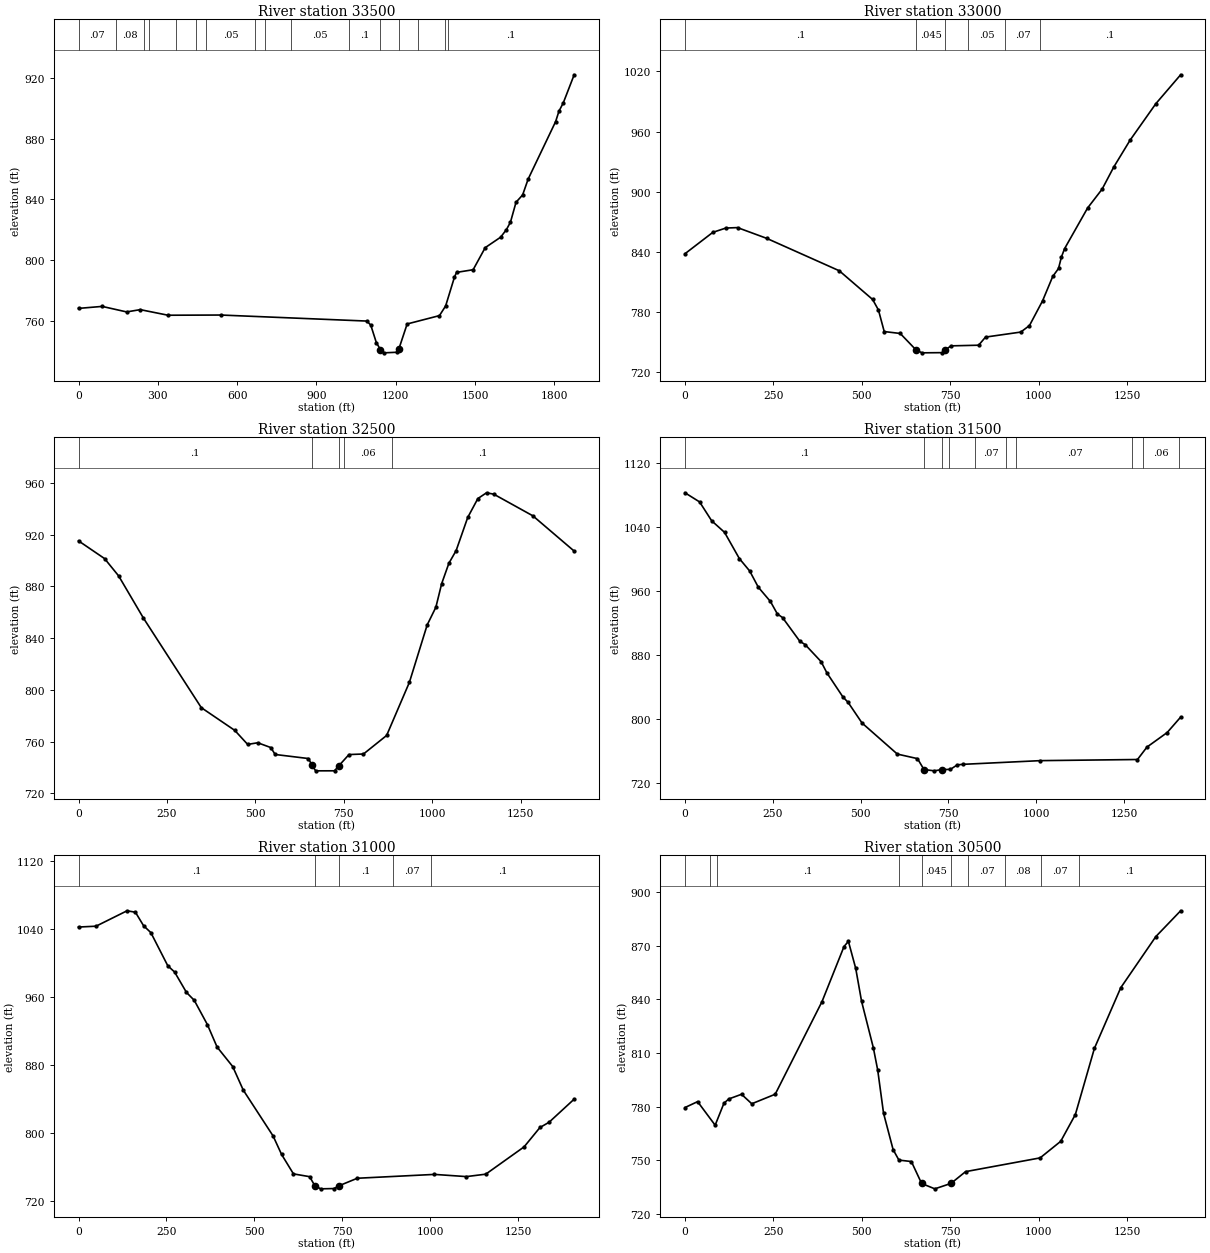
Type RM Length L Ch R = 1 ,33500   ,498.7,500,501.7
BEGIN DESCRIPTION:
Structure 15 XS 1
END DESCRIPTION:
XS GIS Cut Line= 6
1649787.78770182375103.0573862381649651.19099391375285.081825903
1649359.01422129375475.439420185 1649193.0046914375535.202850948
1648865.89499623375618.771485335 1649082.5248656376371.920454592
#Sta/Elev= 30
       0  768.28    89.4  769.59   181.9  765.96   233.6  767.46   338.5  763.78
   538.6  763.91  1090.5  759.94  1105.3  757.28  1126.4  745.761141.877741.1896
  1155.5  739.02  1205.4  739.411211.707741.6455  1242.9  758.03  1365.1  763.53
  1388.5   769.9  1421.8  788.85  1429.8  791.99  1492.5  793.74  1538.2  808.28
  1596.5  815.16  1618.3  820.14  1633.7  825.05  1654.7  838.16  1679.7  842.99
  1700.5  853.39  1804.5  891.27    1817  898.08  1833.6  903.66  1874.6  922.09
#Mann= 16 ,-1,0
       0     .07       0     140     .08       0  247.58     .06       0
  267.58     .07       0  367.58     .05       0  442.96      .1       0
  482.96     .05       0  666.67     .07       0  706.67      .1       0
  803.11     .05       0 1024.25      .1       01141.877    .045       0
1211.707     .05       0 1284.17     .08       0 1386.67     .05       0
 1396.67      .1       0
Bank Sta=1141.877,1211.707
XS Rating Curve= 0 ,0
Exp/Cntr(USF)=0,0
Exp/Cntr=0.3,0.1

Type RM Length L Ch R = 1 ,33000   ,500,500,500.4
XS GIS Cut Line= 6
 1648246.2033755375123.8504441681648392.44980218375757.585397169
1648431.80044526 375928.103756921648472.55594118376104.712327585
  1648494.338706376199.1064957531648561.18142009376488.759459749
#Sta/Elev= 30
       0  837.96    78.7  859.32   115.6  863.62   148.5  864.06   230.6  853.38
     436  820.96   530.3  792.28   546.7  781.81   563.1  760.23   608.3  758.32
   652.6  742.03   669.8  738.97   727.3  739.17     736  741.97   751.9  745.94
   829.9  746.59   849.4   754.7     949  759.71   973.6  766.23  1010.6   790.9
  1039.3  815.23  1055.7  823.24  1063.9   834.7  1072.8  843.03  1137.8  883.61
  1178.9  902.48  1211.7  924.49  1257.8  951.32  1330.8  987.87  1400.8 1016.71
#Mann= 6 ,-1,0
       0      .1       0   652.6    .045       0     736      .1       0
  800.39     .05       0  905.39     .07       0 1002.89      .1       0
Bank Sta=652.6,736
XS Rating Curve= 0 ,0
Exp/Cntr(USF)=0,0
Exp/Cntr=0.3,0.1

Type RM Length L Ch R = 1 ,32500   ,1004.7,999.5,986.9
XS GIS Cut Line= 6
1647785.23809008375267.9285680951647802.55695309   375366.227256
1647820.53460743375463.8517326711647861.81109968375654.752597585
1647881.62306793375746.3852883431648074.54886317376638.657125846
#Sta/Elev= 30
       0  915.27    73.7  901.55   113.4  888.18   183.5  855.55   347.1  786.29
   441.6  768.74   478.1  757.88   506.7  759.15   543.5  755.44   555.8  750.09
   649.9  746.95  660.21741.6554   670.4  737.44   723.6  737.47   735.9  741.39
   764.5  750.03   805.5  750.46   870.9  764.79   935.3  805.91   985.5  850.24
  1010.1  863.94  1026.5   882.2  1046.9  897.96  1067.4  907.76  1100.1  933.36
  1128.8  947.98  1153.3  952.45  1173.8  951.36  1284.3  934.62    1401  907.36
#Mann= 5 ,-1,0
       0      .1       0  660.21    .045       0   735.9      .1       0
  750.64     .06       0  885.64      .1       0
Bank Sta=660.21,735.9
XS Rating Curve= 0 ,0
Exp/Cntr(USF)=0,0
Exp/Cntr=0.3,0.1

Type RM Length L Ch R = 1 ,31500   ,508.6,500.5,488.5
XS GIS Cut Line= 6
1646546.52731292375526.7397302541646925.30969185376055.329880416
1647027.81703275376197.5018401741647246.60104401376505.874254927
1647293.81059526376596.2556358431647338.86332667376691.113385752
#Sta/Elev= 30
       0 1082.83    41.6 1071.39      76  1047.8   112.6 1033.38   154.8 1000.54
   184.3  984.96   208.7  964.76   243.2   946.9     263  931.28   277.6  926.82
     327  897.09   341.8   893.1   387.3  871.78   403.8  857.74   449.6  827.47
     464  820.94     504  794.93   604.4  756.11   661.7  750.43  680.27736.7881
   709.7  735.16   730.2  736.69   755.4     737   775.1  742.64   791.8  743.31
  1011.5  747.91  1287.9  749.33  1314.8  764.84  1372.4  783.04  1410.7  802.32
#Mann= 10 ,-1,0
       0      .1       0  680.27    .045       0   730.2      .1       0
   750.3     .05       0  825.57     .07       0  913.41     .05       0
  943.41     .07       0 1273.67     .05       0 1303.67     .06       0
 1405.64      .1       0
Bank Sta=680.27,730.2
XS Rating Curve= 0 ,0
Exp/Cntr(USF)=0,0
Exp/Cntr=0.3,0.1

Type RM Length L Ch R = 1 ,31000   ,509.2,500,485.7
XS GIS Cut Line= 6
1646041.76749568376073.7878487561646725.77761059376535.740993083
1646803.10521184376577.5991770921646889.04434443376617.884857669
1647071.08531892376697.3807616681647255.01605342376783.244107008
#Sta/Elev= 30
       0 1042.63    49.8 1043.62   138.1 1061.77   161.9 1060.06   185.1 1044.17
   205.7 1036.11     254  997.02   273.3  989.71   307.1  965.68   329.2  956.41
   366.6  927.82   394.1  901.46   438.6  878.48   468.7  850.69   553.5  796.75
   577.6  775.05   611.4  752.12   657.5  748.84   671.9  738.36   688.7  734.53
   726.7  734.86   741.9  738.31     793  746.99  1012.6  751.52  1103.3  748.93
  1158.4  751.79  1267.4  783.91  1312.6  806.72  1338.4  812.85  1409.9  840.09
#Mann= 5 ,-1,0
       0      .1       0   671.9    .045       0   741.9      .1       0
   895.4     .07       0 1003.33      .1       0
Bank Sta=671.9,741.9
XS Rating Curve= 0 ,0
Exp/Cntr(USF)=0,0
Exp/Cntr=0.3,0.1

Type RM Length L Ch R = 1 ,30500   ,825.2,819.8,812.9
XS GIS Cut Line= 6
1645813.63901493376767.6519465891646442.30573659376934.343542337
1646538.96564826376959.9734123351646880.29567426377050.477168337
1646975.44541834377075.7064485851647167.63236992377126.665008083
#Sta/Elev= 30
       0  779.55    35.7  782.85    85.3  769.69   110.2  781.99   123.8  784.34
   159.8  786.95   188.8  781.66     255  786.98   387.4  838.75   449.5  869.46
   461.9  872.34   482.6  857.19   499.1  838.84   532.3  812.97   544.7  800.46
   561.2  776.37   588.2  756.07   604.6  750.21   639.8  749.41   668.8  737.15
   706.1  734.16   751.8  737.19     793  743.76  1003.7  751.44  1061.9   760.7
  1103.3  775.66  1157.1  812.59  1231.6  846.46  1330.7     875  1400.8  889.41
#Mann= 10 ,-1,0
       0      .1       0      70     .05       0      90      .1       0
  605.39     .05       0   668.8    .045       0   751.8      .1       0
  800.39     .07       0  905.39     .08       0 1006.64     .07       0
 1113.52      .1       0
Bank Sta=668.8,751.8
XS Rating Curve= 0 ,0
Exp/Cntr(USF)=0,0
Exp/Cntr=0.3,0.1

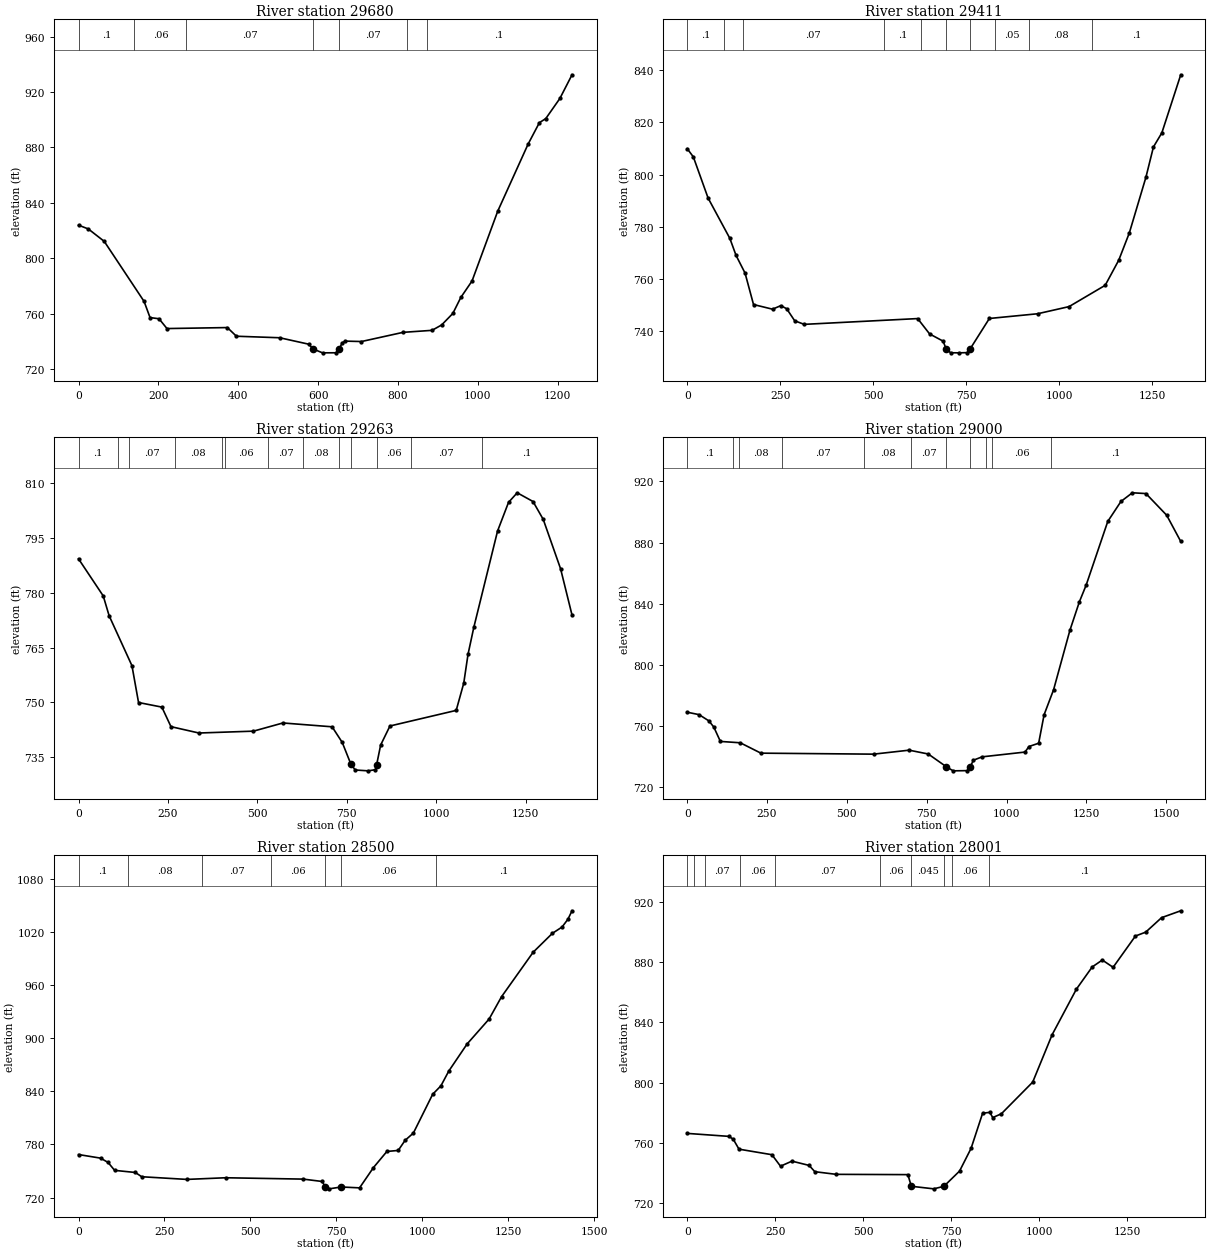
Type RM Length L Ch R = 1 ,29680   ,267.5,268.8,269.9
BEGIN DESCRIPTION:
Structure 14 XS 4
END DESCRIPTION:
XS GIS Cut Line= 3
1645792.50754768377514.1755978861646082.35603726377730.275655206
1646953.61658582377804.024087467
#Sta/Elev= 30
       0  823.81    24.5  821.08    64.4  812.11   164.2  768.75   179.1  757.09
   201.5  756.26   221.5  749.17   372.7  749.88   395.4  743.63   503.8  742.53
   576.1  737.91   588.1  734.36     611  731.64   644.3  731.68   652.3  734.15
   660.4  738.88   668.4   740.1   708.5   739.8   812.9  746.44   885.2  747.88
   909.3  751.76   937.4  760.08   957.4  771.63   985.5  783.52  1049.9  833.96
    1126  882.39  1154.1  897.78  1170.2  900.77  1205.4  915.25  1235.9  932.37
#Mann= 7 ,-1,0
       0      .1       0     140     .06       0     270     .07       0
   588.1    .045       0   652.3     .07       0  821.54     .08       0
  871.54      .1       0
Bank Sta=588.1,652.3
XS Rating Curve= 0 ,0
Exp/Cntr(USF)=0,0
Exp/Cntr=0.3,0.1

Type RM Length L Ch R = 1 ,29411   ,148.7,148.9,149.8
BEGIN DESCRIPTION:
Structure 14 XS 3
END DESCRIPTION:
XS GIS Cut Line= 4
1645705.38792245377692.181881583 1645943.0730083377973.735262725
1646588.85554574378053.3391893041646892.62618987378102.351969786
#Sta/Elev= 30
       0  809.92    16.4  806.77    56.1  790.94   114.5  775.47   131.3  768.89
   155.5  762.09   178.2  750.02   229.3  748.23   251.7   749.6   267.4  748.39
   288.9  743.77   314.5   742.4   619.5  744.62   651.6  738.72   687.9  735.94
     696  732.98   708.1  731.48   730.7  731.45   752.2  731.53   760.5  732.94
   812.3  744.66   941.8  746.47  1026.5  749.22  1123.7  757.41  1160.2  767.09
  1188.6  777.55  1233.1   798.9  1253.4   810.6    1276  816.01  1326.8  838.34
#Mann= 10 ,-1,0
       0      .1       0     100     .08       0     150     .07       0
  528.47      .1       0  628.47     .07       0     696    .045       0
   760.5     .08       0  828.47     .05       0  918.47     .08       0
 1089.14      .1       0
Bank Sta=696,760.5
XS Rating Curve= 0 ,0
Exp/Cntr(USF)=0,0
Exp/Cntr=0.3,0.1

Type RM Length L Ch R = 1 ,29263   ,255.6,262.6,270.4
BEGIN DESCRIPTION:
Structure 14 XS 2
END DESCRIPTION:
XS GIS Cut Line= 3
1645630.83693549377764.925488882 1645942.2704536378115.082062824
1646843.80140021378248.844009345
#Sta/Elev= 30
       0  789.29    69.1  779.14    85.6  773.71   149.4  760.05   167.8  749.98
     233  748.72   258.5  743.37   336.7  741.63   489.1  742.14   571.6  744.38
   709.1  743.33   737.4  739.06   761.6  733.11   773.8  731.51   809.6  731.28
   830.4  731.59   833.6 732.954   844.8  738.33   870.8  743.55  1056.1  747.82
  1077.2  755.27  1089.2  763.19  1105.3  770.53  1171.8  796.92  1202.4  804.74
  1226.7  807.37  1270.9  804.98  1299.5  800.08    1348  786.57    1380   773.9
#Mann= 13 ,-1,0
       0      .1       0     110     .08       0     140     .07       0
     270     .08       0     400     .07       0     410     .06       0
  528.62     .07       0  628.62     .08       0  728.62     .07       0
   761.6    .045       0   833.6     .06       0  928.62     .07       0
 1128.62      .1       0
Bank Sta=761.6,833.6
XS Rating Curve= 0 ,0
Exp/Cntr(USF)=0,0
Exp/Cntr=0.3,0.1

Type RM Length L Ch R = 1 ,29000   ,461.9,500,543.1
BEGIN DESCRIPTION:
Structure 14 XS 1
END DESCRIPTION:
XS GIS Cut Line= 6
1645615.34413593377843.5808970931645698.01391809377946.513762087
 1645943.3874431378226.0112345961646022.38433234378311.450368166
1646098.96488784378374.3842974161646874.66543618378658.551380008
#Sta/Elev= 30
       0  769.15    37.1  767.56    67.9  763.47    83.3  759.42   103.8  750.06
   166.1  749.18   230.7   742.4   583.7  741.75     695  744.35   754.8  741.85
     811  733.59   832.8  730.85   876.6  730.98   885.9  733.45   896.5  737.81
   923.4  739.99  1057.8  743.11  1070.3  746.75  1100.6  748.88  1117.6  767.47
  1147.4  783.85  1198.4  822.61  1228.2   841.3  1249.5  852.25  1317.1   893.8
  1358.3  906.81  1394.1   912.5  1436.6  911.98  1501.5  897.85  1545.6  880.72
#Mann= 11 ,-1,0
       0      .1       0  142.02     .07       0  162.02     .08       0
  296.23     .07       0  553.96     .08       0  700.32     .07       0
     811    .045       0   885.9     .05       0  935.25     .07       0
  955.25     .06       0 1137.75      .1       0
Bank Sta=811,885.9
XS Rating Curve= 0 ,0
Exp/Cntr(USF)=0,0
Exp/Cntr=0.3,0.1

Type RM Length L Ch R = 1 ,28500   ,492.4,499.4,507.3
XS GIS Cut Line= 6
1645599.72441651377844.3620635121645666.77447926377948.076094925
1645718.72155385378041.8767603341645738.01580659378138.966133088
1645799.43267851 378845.683223591645813.45299168379241.494767919
#Sta/Elev= 30
       0  768.57    64.1  764.51    85.9  759.65     105  750.71   165.2  748.31
   183.7  743.51     315  740.49   427.7  742.36   653.4  740.83   708.8  738.14
  717.59731.9154   728.9  729.84   763.9  731.93   817.3  730.94   857.8  753.91
   896.8  772.07   929.7   773.2   949.7  784.59   973.8  792.83  1029.9  836.61
    1054  846.23  1076.7   862.8    1130  893.43  1194.1  921.64  1230.1  946.76
  1322.2  997.09  1378.2 1018.43  1406.2 1025.52  1423.2 1034.29  1435.2 1043.87
#Mann= 7 ,-1,0
       0      .1       0   143.5     .08       0  359.71     .07       0
  560.34     .06       0  717.59    .045       0   763.9     .06       0
 1039.11      .1       0
Bank Sta=717.59,763.9
XS Rating Curve= 0 ,0
Exp/Cntr(USF)=0,0
Exp/Cntr=0.3,0.1

Type RM Length L Ch R = 1 ,28001   ,520.9,500.6,490.9
XS GIS Cut Line= 6
1645407.37407942377819.8522700071645320.62261251378300.753867254
1645304.83097742378386.9443116781645290.97044083378460.744689003
 1645272.1266465378558.9600437581645133.03112417379194.267172083
#Sta/Elev= 30
       0  766.23   118.6  764.25   130.8  762.31     147  755.74   240.5  752.06
   264.9  744.41   297.4  747.78   346.2  744.94   362.4  740.76   423.2     739
   626.7  738.81   636.5  731.07     700  729.36   728.8  731.01   773.5  741.18
   806.2  756.28     839  779.66   859.5  780.22   867.7  776.75   892.2  779.27
   981.2  800.33  1036.5   831.9  1105.4  862.18  1150.2  876.92  1178.9  881.52
  1209.6  876.69    1273  897.49  1302.2  900.07  1347.3  909.71  1401.7  914.28
#Mann= 10 ,-1,0
       0      .1       0      20     .06       0      50     .07       0
  149.77     .06       0  249.15     .07       0  548.66     .06       0
   636.5    .045       0   728.8      .1       0  751.38     .06       0
  856.42      .1       0
Bank Sta=636.5,728.8
XS Rating Curve= 0 ,0
Exp/Cntr(USF)=0,0
Exp/Cntr=0.3,0.1

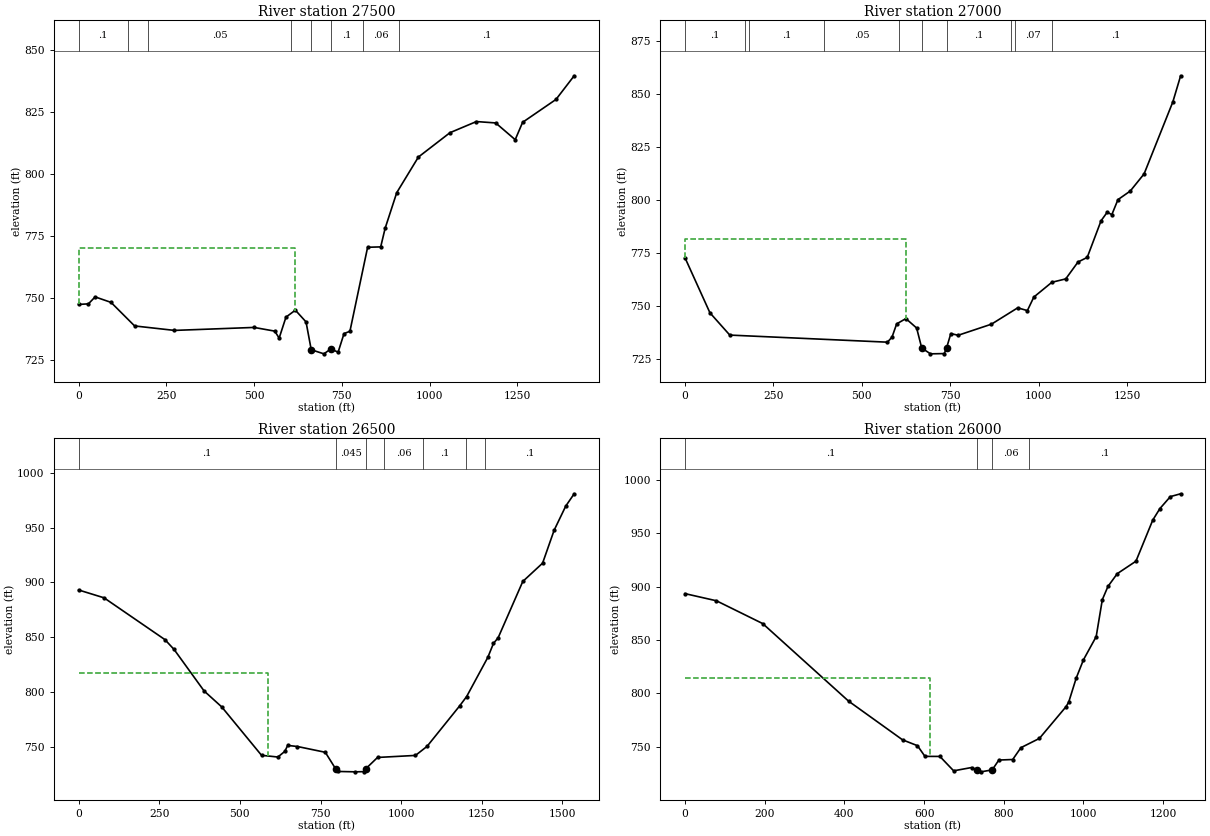
Type RM Length L Ch R = 1 ,27500   ,503.5,500,499
XS GIS Cut Line= 6
1644576.84391634 377784.676815421644829.13868734378570.563038915
1644852.46245959378654.9749435931644874.18551326378746.466558501
1644910.89508551378941.1033083351644931.24281384379146.825337842
#Sta/Elev= 30
       0  747.47    27.9  747.71      47  750.51    92.3   748.3   159.5   738.8
     273     737   499.8   738.2   558.7  736.71   571.3   733.9   590.7  742.35
   617.5  745.16   647.9  740.42  662.67729.2023   698.8  727.55   718.3  729.51
   739.3  728.23   756.1  735.72   772.9  736.64   823.3  770.52   860.6  770.68
   873.1  778.12   906.3  792.55     968  806.91    1058  816.73  1133.3  821.22
  1188.2  820.66  1243.8  813.91  1264.9  820.91    1360  830.14  1411.8  839.68
#Mann= 8 ,-1,0
       0      .1       0  139.61     .06       0  198.83     .05       0
  605.39     .07       0  662.67    .045       0   718.3      .1       0
  810.39     .06       0  912.97      .1       0
#XS Ineff= 2 , 0
          615.38  770.07
Permanent Ineff=
       F       F
Bank Sta=662.67,718.3
XS Rating Curve= 0 ,0
Exp/Cntr(USF)=0,0
Exp/Cntr=0.3,0.1

Type RM Length L Ch R = 1 ,27000   ,507,499.8,489.3
XS GIS Cut Line= 6
1644062.74520701377999.452632591  1644175.107187378274.699457422
1644211.94044667378364.3068897581644247.89772384378450.891034171
1644566.28586659379199.2592880871644616.96325867379285.947434917
#Sta/Elev= 30
       0  772.56    70.3  746.71   126.4  736.22   572.3  732.88   585.3  735.27
   598.4   741.5   624.5  743.99   654.9  739.55   669.3  730.11     694  727.38
   733.1   727.5   739.4  730.07   751.6  736.93   772.3  736.13   866.6  741.37
   940.7  749.06   968.1  747.77   986.4  754.14  1037.4  761.11  1076.6   762.7
  1111.3  770.66  1137.4  772.84  1176.5  790.09  1193.9  794.13    1207  792.99
  1224.3  800.06  1259.1  804.11  1298.3  812.21  1379.5  846.11  1401.6  858.44
#Mann= 10 ,-1,0
       0      .1       0  169.62     .05       0  179.62      .1       0
  394.18     .05       0  605.43     .07       0   669.3    .045       0
   739.4      .1       0  922.93     .06       0  932.93     .07       0
 1036.68      .1       0
#XS Ineff= 2 , 0
          623.44  781.31
Permanent Ineff=
       F       F
Bank Sta=669.3,739.4
XS Rating Curve= 0 ,0
Exp/Cntr(USF)=0,0
Exp/Cntr=0.3,0.1

Type RM Length L Ch R = 1 ,26500   ,458.6,500.2,558.9
XS GIS Cut Line= 6
1643753.49680975378170.0251260851643789.50165901378536.468947008
1643851.68198083 378766.087582261643891.12087834378860.800319344
1643930.85833168378926.6771560911644399.04112235379513.035891503
#Sta/Elev= 30
       0  893.12    78.7  885.98   267.5  847.84   295.8  838.91   388.9  801.03
   443.6  786.47     567  742.32   617.6  740.75   639.3  745.91     648  751.35
   678.3  750.35   764.7  745.07  796.63730.0212   803.6   727.6   858.1  727.24
   883.7  727.42   890.1  730.03   926.6  740.36  1044.2  742.21  1080.1  750.47
  1180.8  787.25  1202.9  795.95  1268.5  831.65  1286.1  844.45  1300.4  849.46
  1376.9  900.88  1438.3  917.59  1474.1  947.62    1510  969.59  1536.2  980.87
#Mann= 7 ,-1,0
       0      .1       0  796.63    .045       0   890.1    .025       0
  945.84     .06       0 1068.33      .1       0 1202.07     .05       0
 1258.94      .1       0
#XS Ineff= 2 , 0
          587.78  817.41
Permanent Ineff=
       F       F
Bank Sta=796.63,890.1
XS Rating Curve= 0 ,0
Exp/Cntr(USF)=0,0
Exp/Cntr=0.3,0.1

Type RM Length L Ch R = 1 ,26000   ,503.6,500,495.2
XS GIS Cut Line= 6
1643743.99617259378165.7984285061643743.21008493378281.325756505
1643735.42269893378395.3635861721643713.49721783378502.656022504
1643665.66037126378586.9547384231643244.42433709379276.245354593
#Sta/Elev= 30
       0   893.5    78.7  886.81   194.9  865.42   410.5  792.69   545.9  756.43
   583.4  750.93   602.2  740.91   639.7  740.85   674.2  727.36   719.4  730.47
   733.3728.2346   742.8  726.41     771  728.24   787.7  737.47   822.5  737.97
     843  749.05   889.5  757.75   956.5  787.55   963.2  791.92   981.9  814.29
  1000.1  831.45  1032.1  853.23  1047.5  887.89  1061.6  900.26    1085  912.24
  1131.9  923.92  1174.1  962.47  1192.1   973.3  1218.3   984.5  1244.1  987.15
#Mann= 4 ,-1,0
       0      .1       0   733.3    .045       0     771     .06       0
  862.52      .1       0
#XS Ineff= 2 , 0
          614.67  814.66
Permanent Ineff=
       F       F
Bank Sta=733.3,771
XS Rating Curve= 0 ,0
Exp/Cntr(USF)=0,0
Exp/Cntr=0.3,0.1