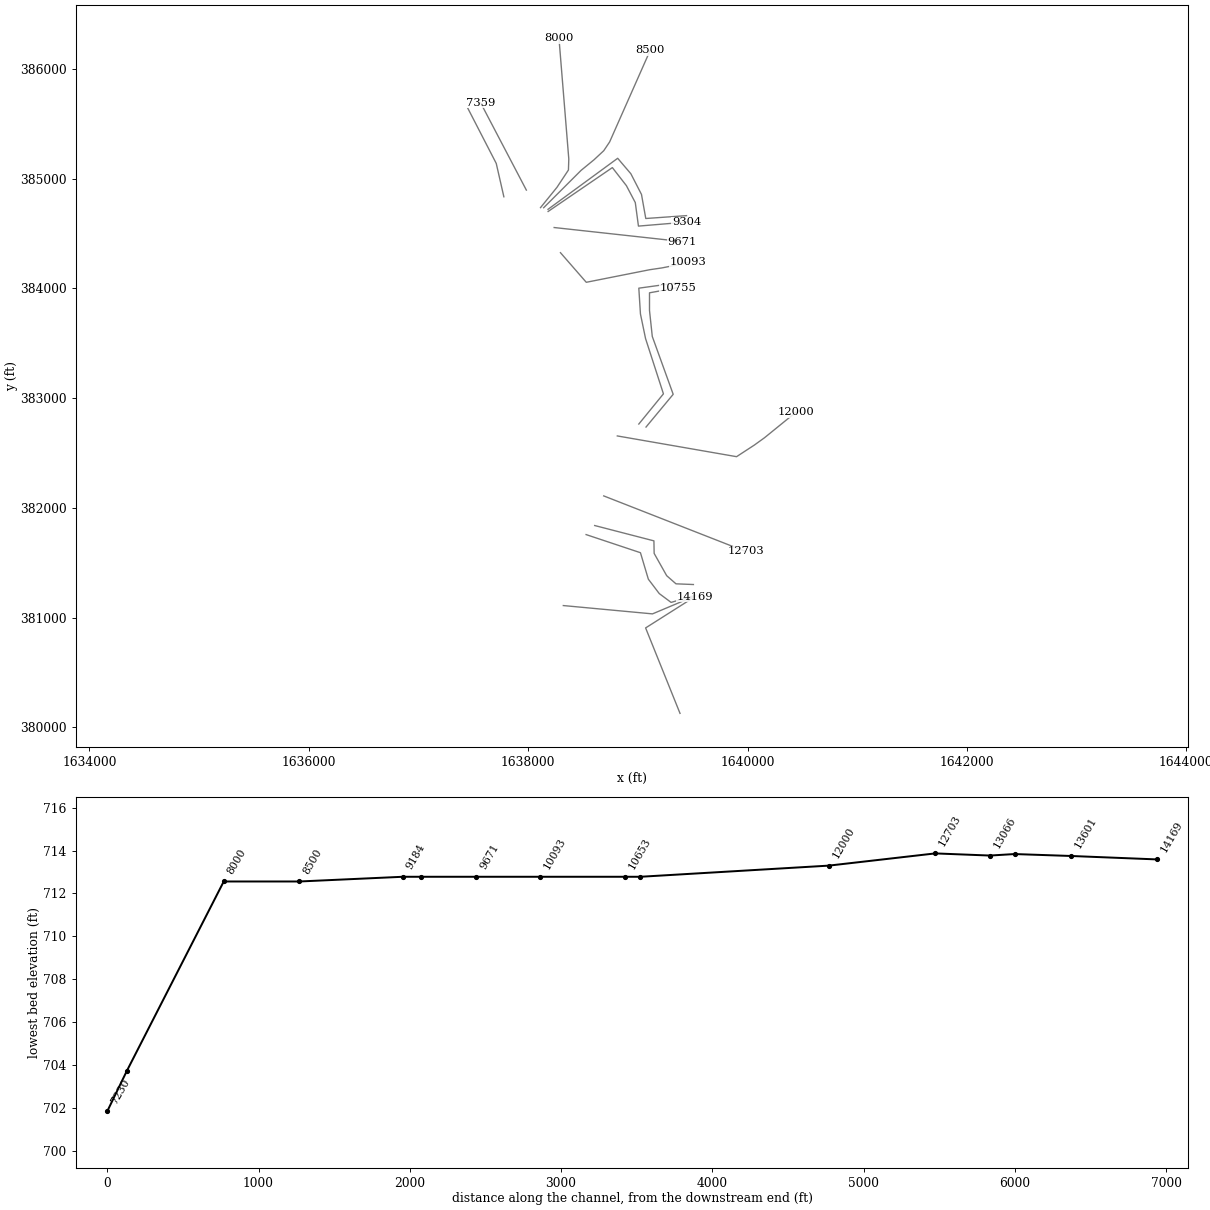
HEC-RAS study SFFSHGCK.prj: SFFSHGCK

--- SFFSHGCK.g01 (geometry) --- (continued)

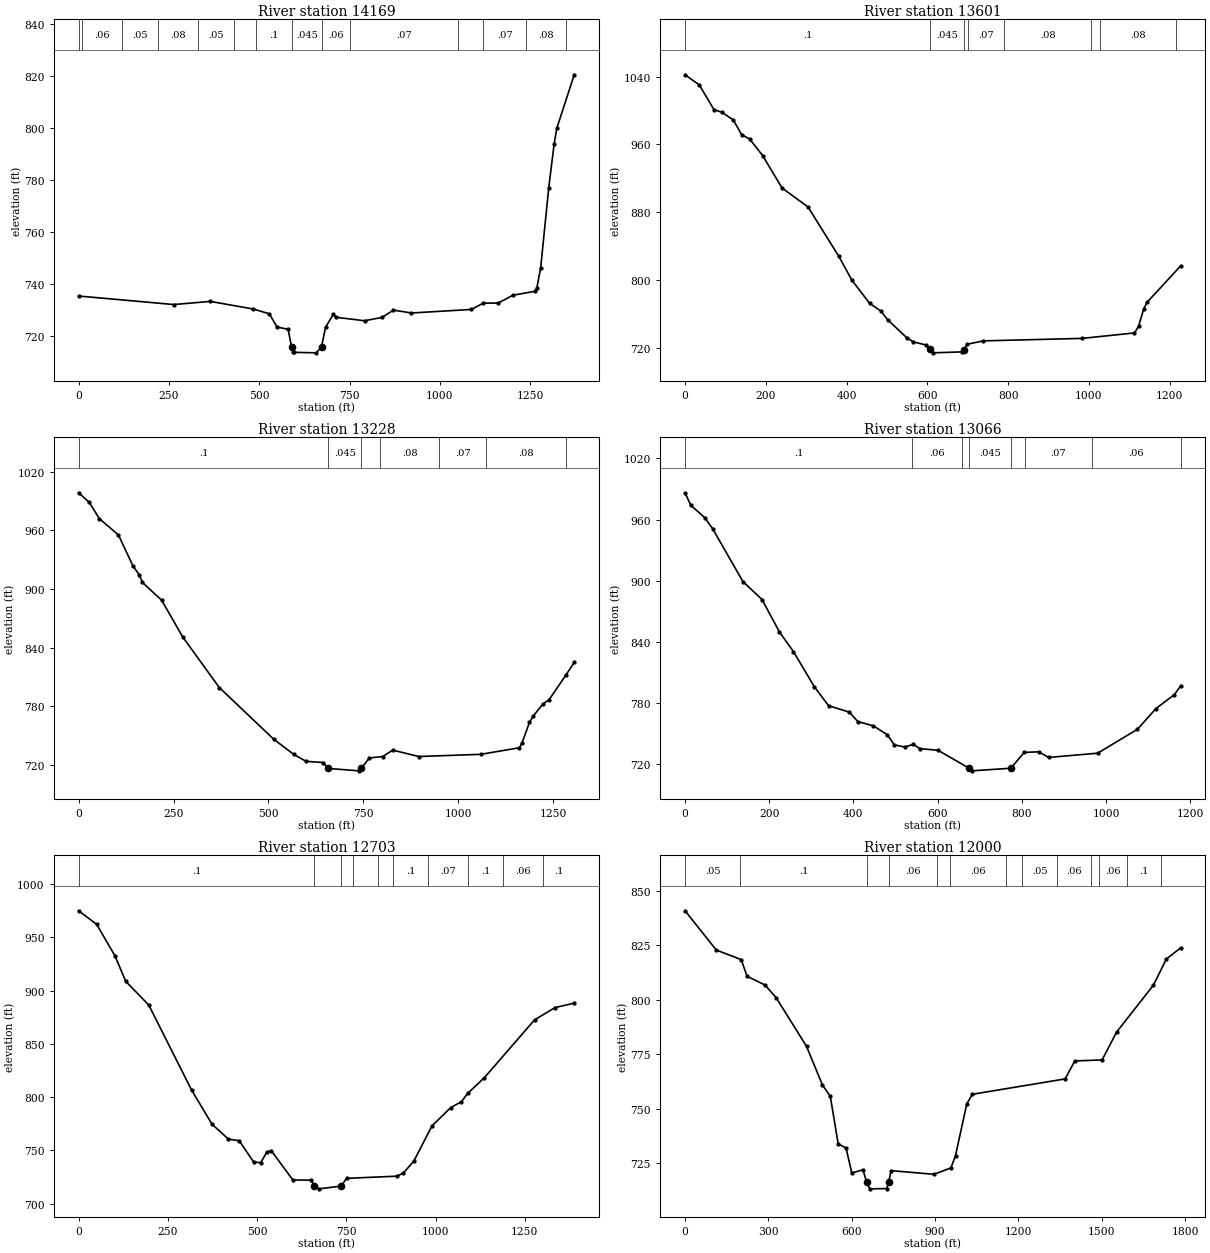
Type RM Length L Ch R = 1 ,14169   ,651.3,567.3,481.4
BEGIN DESCRIPTION:
Structure 9 XS 2
END DESCRIPTION:
XS GIS Cut Line= 3
1639384.76045551380126.3490490691639071.07416013  380905.3366826
1639520.69118351381190.268400905
#Sta/Elev= 30
       0   735.4   263.5  732.13   364.6  733.34   483.6  730.41   527.9  728.58
   549.4  723.51     580  722.62   589.4  715.91   593.1  714.02   597.4  713.78
   657.8  713.59   672.4  715.85   683.7  723.48   705.2  728.35   713.9  727.22
   791.5  725.91   839.8  727.19   871.6  729.99   921.5  728.89  1087.3  730.25
  1120.4  732.68  1161.7   732.7  1202.3  735.72  1264.2  737.23  1268.9  738.67
  1279.2  746.26  1301.6  777.06  1316.5  793.81    1324  799.87  1372.1  820.35
#Mann= 14 ,-1,0
       0     .05       0      10     .06       0     120     .05       0
     220     .08       0     330     .05       0     430     .06       0
     490      .1       0   589.4    .045       0   672.4     .06       0
     750     .07       0 1049.77     .08       0 1119.77     .07       0
 1239.77     .08       0 1349.77      .1       0
Bank Sta=589.4,672.4
XS Rating Curve= 0 ,0
Exp/Cntr(USF)=0,0
Exp/Cntr=0.3,0.1

Type RM Length L Ch R = 1 ,13601   ,433,373.3,343.6
BEGIN DESCRIPTION:
Structure 8 XS 4 And Structure 9 XS 1
END DESCRIPTION:
XS GIS Cut Line= 3
1638320.84110367381109.232774598 1639133.8114192381033.425253214
1639512.44659713381192.909221231
#Sta/Elev= 30
       0 1042.09    35.4 1030.13    71.6 1000.93    91.7  997.74   119.8  988.61
   139.9  971.49     160  966.24   192.1  946.72   240.3  908.37   304.6  885.97
   380.9  827.63   413.1  799.64   457.2  772.14   485.4  762.95   501.4  752.95
   549.6  731.32   565.7  726.64   597.9  722.87  606.93717.8882   613.9  713.75
   686.2  714.87  691.83717.6565   698.3  723.84   738.5  727.87   983.9  730.83
    1113  737.24    1123  744.93  1135.8  765.47    1144  773.38  1227.3  816.38
#Mann= 8 ,-1,0
       0      .1       0  606.93    .045       0  691.83      .1       0
     700     .07       0     790     .08       0  1006.5     .07       0
  1026.5     .08       0  1216.5      .1       0
Bank Sta=606.93,691.83
XS Rating Curve= 0 ,0
Exp/Cntr(USF)=0,0
Exp/Cntr=0.3,0.1

Type RM Length L Ch R = 1 ,13228   ,153,162.3,156.5
BEGIN DESCRIPTION:
Structure 8 XS 3
END DESCRIPTION:
XS GIS Cut Line= 6
1638528.50143121381756.2891803961639023.96893477381591.133345878
1639095.95993956381349.7517415821639195.47691677381218.474026964
1639303.46342395381138.0134921991639525.78858581381203.652349508
#Sta/Elev= 30
       0  998.29      28  988.55    54.4  971.88     105  955.09   142.9  923.67
   159.8   914.3   168.2  906.51   218.8  888.37   273.7  851.14   370.6  799.08
     514   746.2   566.2  730.84   599.2  723.57   644.6  722.36   657.2  716.32
   737.6  713.84  744.97716.3111     766  727.04   801.1  728.44   827.6  735.02
   896.4   728.5  1059.6  730.73  1161.2  737.44  1168.2  742.19  1187.9  763.34
  1198.4  770.16  1223.2  782.15    1240  786.78  1283.5  811.57  1305.9  824.69
#Mann= 7 ,-1,0
       0      .1       0   657.2    .045       0  744.97      .1       0
  794.38     .08       0  949.11     .07       0 1073.78     .08       0
  1283.5      .1       0
Bank Sta=657.2,744.97
XS Rating Curve= 0 ,0
Exp/Cntr(USF)=0,0
Exp/Cntr=0.3,0.1

Type RM Length L Ch R = 1 ,13066   ,325.2,362.2,393.6
BEGIN DESCRIPTION:
Structure 8 XS 2
END DESCRIPTION:
XS GIS Cut Line= 6
1638606.84458349381838.8670976551639146.77711941381699.119853063
 1639148.8945019381584.7811983961639263.23315657381381.512478989
1639347.92845632381307.4040917051639506.73214336381301.051944224
#Sta/Elev= 30
       0  986.39    13.7  974.11    46.8  962.02    65.3  951.32   137.5  899.38
   183.1  881.62   224.4  849.83   257.5  830.75   307.1  796.21     341  777.64
   390.3  771.34   410.4  762.09   447.5  757.88   480.6  749.18   497.1  739.23
   521.9  737.17   542.6  739.71   557.7  735.56   600.9  733.92   674.7  716.39
   681.2  713.77   773.8  716.32   805.8  731.82     840  732.42   863.9  726.91
   980.3  731.07  1074.7   754.5  1118.7  774.79  1162.8  788.61  1177.4  797.06
#Mann= 8 ,-1,0
       0      .1       0     540     .06       0  657.72      .1       0
   674.7    .045       0   773.8     .08       0   806.7     .07       0
  965.91     .06       0 1177.38      .1       0
Bank Sta=674.7,773.8
XS Rating Curve= 0 ,0
Exp/Cntr(USF)=0,0
Exp/Cntr=0.3,0.1

Type RM Length L Ch R = 1 ,12703   ,694.8,703.5,710.1
BEGIN DESCRIPTION:
Structure 8 XS 1
END DESCRIPTION:
XS GIS Cut Line= 2
1638689.20948977382108.929130939 1639982.2454625381602.527192696
#Sta/Elev= 30
       0  974.97    50.4  962.29   101.9  932.58     132  908.71   196.4  886.52
   316.7   806.5     374  774.45   419.8  760.55   449.9  759.07   490.3  739.11
     510  738.41   527.3  748.32   539.7  749.78   600.2   722.2   651.8  722.02
 660.481716.2856   673.3  713.87  735.79716.4614   750.6  723.71   892.4  725.78
   910.1  728.74   939.6  740.09   990.3  773.07  1042.4  790.09  1072.8  795.71
    1090  803.47  1137.2  818.35  1277.4  872.49  1334.8  884.07  1388.7  888.23
#Mann= 10 ,-1,0
       0      .1       0 660.481    .045       0  735.79      .1       0
     770     .08       0     840     .07       0     880      .1       0
     980     .07       0    1090      .1       0    1190     .06       0
    1300      .1       0
Bank Sta=660.481,735.79
XS Rating Curve= 0 ,0
Exp/Cntr(USF)=0,0
Exp/Cntr=0.3,0.1

Type RM Length L Ch R = 1 ,12000   ,1171,1244.9,1320.6
BEGIN DESCRIPTION:
Structure 7 XS 4
END DESCRIPTION:
XS GIS Cut Line= 6
1638813.04146759382655.6854460841639453.81380808382544.246036425
1639900.23778401382466.6070840951640062.57085696382572.601113692
1640155.09419695382639.2504983871640444.10859436382873.994620838
#Sta/Elev= 30
       0  840.93   112.7  822.89   202.1  818.53   223.3  810.86   287.3   806.9
   327.9  801.05   437.5  778.66   494.4  760.99   522.8  755.76   551.2  733.98
   579.6  731.99   600.2  720.57   640.5  722.04   653.6  716.35   664.9   713.3
   725.8  713.42  732.44716.2256     742  721.66   896.3  719.96   957.2  722.95
   973.5  728.56  1014.1  752.33  1034.4  756.71  1368.3  763.76  1402.8     772
  1501.2  772.48    1553  785.19  1685.9   806.8  1732.2  818.75  1783.8  823.91
#Mann= 13 ,-1,0
       0     .05       0  198.83      .1       0   653.6    .045       0
  732.44     .06       0  905.39     .08       0  952.89     .06       0
 1153.52     .07       0 1213.52     .05       0 1337.39     .06       0
 1461.42     .05       0 1491.42     .06       0 1591.42      .1       0
 1711.42     .06       0
Bank Sta=653.6,732.44
XS Rating Curve= 0 ,0
Exp/Cntr(USF)=0,0
Exp/Cntr=0.3,0.1

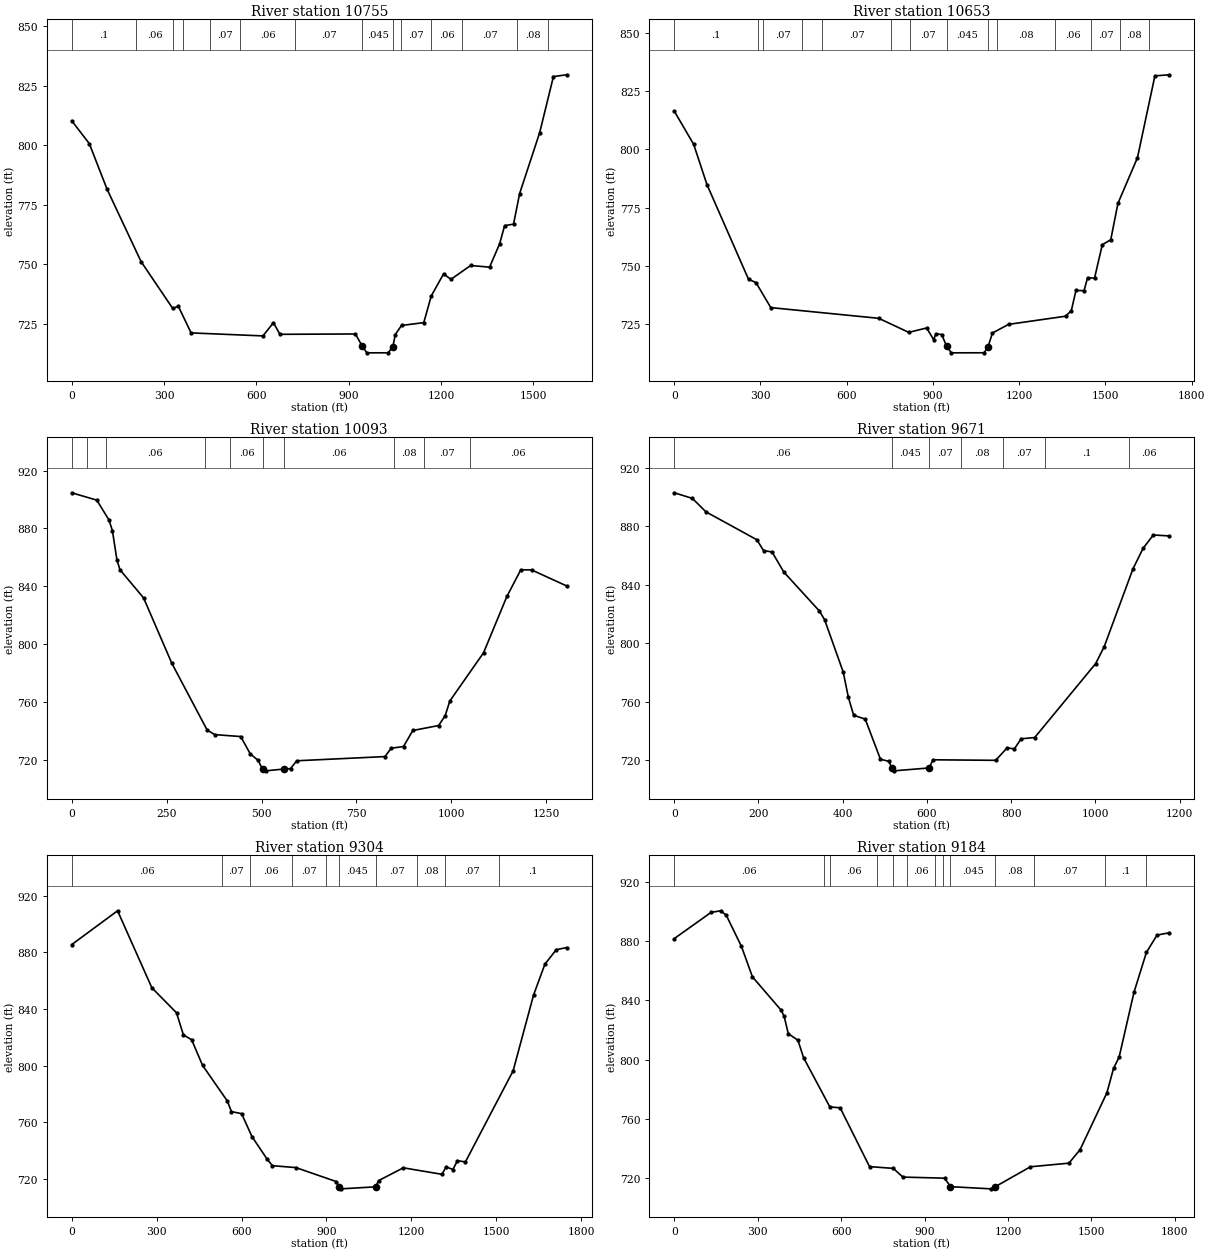
Type RM Length L Ch R = 1 ,10755   ,86.5,101.9,129
BEGIN DESCRIPTION:
Structure 7 XS 3
END DESCRIPTION:
XS GIS Cut Line= 6
1639074.78611462382736.637275037 1639322.5198664383035.188206667
1639131.95544196383562.4164476291639106.54685203383799.563286938
1639106.54685203383960.4843564691639362.75013378384007.066771333
#Sta/Elev= 30
       0  810.22      57  800.66   114.8  781.49   225.3   751.1   327.8   731.5
   346.6  732.27   387.9  721.15   621.4  719.89   655.4  725.43   676.6  720.56
   921.9   720.7  944.24715.5265     959  712.78    1028  712.79  1043.4  715.29
  1051.5  720.48  1071.6  724.27    1144  725.47  1168.2  736.65  1208.3  745.93
  1232.3  743.65  1296.3  749.46  1357.9  748.76  1390.5  758.59  1406.7   766.2
  1435.6  766.81  1455.5  779.67  1520.6  805.25  1565.3   828.8  1608.6  829.54
#Mann= 14 ,-1,0
       0      .1       0     210     .06       0     330     .07       0
     360     .06       0  447.95     .07       0  547.95     .06       0
  725.16     .07       0  944.24    .045       0  1043.4     .08       0
 1068.79     .07       0 1168.79     .06       0 1267.29     .07       0
 1448.21     .08       0 1548.21     .06       0
Bank Sta=944.24,1043.4
XS Rating Curve= 0 ,0
Exp/Cntr(USF)=0,0
Exp/Cntr=0.3,0.1

Type RM Length L Ch R = 1 ,10653   ,631.5,560.2,471.5
BEGIN DESCRIPTION:
Structure 7 XS 2
END DESCRIPTION:
XS GIS Cut Line= 6
1639009.14725731382764.1632474571639233.58980166383039.422971654
1639070.55134963383543.3600051851639023.96893477 383767.80254953
1639009.14725731384002.8320063451639377.57181124384053.649186197
#Sta/Elev= 30
       0   816.4    67.6  802.15     114  784.86   258.5   744.3   284.3  742.91
     336  732.16   711.4  727.58   815.8  721.56   878.2  723.43   902.4  718.42
   910.5  720.94   930.6  720.63   947.7  715.52   964.4  712.78  1078.3  712.81
 1091.99 715.491    1107  721.28  1163.3  724.99  1361.2  728.47  1381.4  730.86
  1397.5   739.5  1425.8  739.43  1437.9  744.98  1462.1  744.76  1489.1  759.12
  1518.6  761.26  1543.6  776.85  1611.5  796.42  1672.1  831.47    1722  831.94
#Mann= 14 ,-1,0
       0      .1       0     290     .05       0     310     .07       0
  445.17     .08       0  515.17     .07       0  754.89     .08       0
  818.98     .07       0   947.7    .045       0 1091.99     .06       0
 1124.41     .08       0 1324.45     .06       0 1450.09     .07       0
 1550.09     .08       0 1650.09     .06       0
Bank Sta=947.7,1091.99
XS Rating Curve= 0 ,0
Exp/Cntr(USF)=0,0
Exp/Cntr=0.3,0.1

Type RM Length L Ch R = 1 ,10093   ,429.1,422.4,416.6
BEGIN DESCRIPTION:
Structure 7 XS 1
END DESCRIPTION:
XS GIS Cut Line= 6
1638294.78292014384326.3353744591638529.99920224384056.381728167
1639108.70951143384171.0839900821639220.44649267384187.560663179
1639337.73628435384210.8946060091639458.19864184384238.091402009
#Sta/Elev= 30
       0  904.64      66  899.56    97.9  885.97   107.1  878.57   119.1  858.26
     127  851.56   189.3  832.07   263.8  786.92   356.6  740.99   376.5  737.78
   445.1  736.44   470.3  724.49   490.7  720.07  502.53713.9797   511.1  712.78
     560  714.06   576.3  714.31   592.6  719.72   825.1  722.62   841.4  728.36
     874  729.56   898.5  740.62   966.4  744.03   983.8  750.85   995.9  760.93
  1084.8  794.25  1146.3   833.1    1183  851.52  1211.7  851.38    1304  840.33
#Mann= 10 ,-1,0
       0     .08       0      40     .07       0      90     .06       0
     350     .07       0  418.05     .06       0  502.53    .045       0
     560     .06       0  848.05     .08       0  928.05     .07       0
 1048.02     .06       0
Bank Sta=502.53,560
XS Rating Curve= 0 ,0
Exp/Cntr(USF)=0,0
Exp/Cntr=0.3,0.1

Type RM Length L Ch R = 1 ,9671    ,443.7,366.3,335.7
BEGIN DESCRIPTION:
Structure 6 XS 4
END DESCRIPTION:
XS GIS Cut Line= 2
1638237.22532655384555.6657483161639405.70677685384427.577177702
#Sta/Elev= 30
       0  903.02    43.1  899.19    75.3  889.99   196.1  870.91   212.2  863.47
   232.3  862.52   260.4  848.73   344.9  822.09   357.2  816.13   401.3  780.39
   413.4  763.29   426.1  750.82   453.6  748.15   489.8  720.68   509.9  719.29
   516.8  714.65     522  712.78  605.28714.7606   614.5  720.34   763.4  719.97
   790.6  728.54   807.7  727.79   823.8   734.7     856  735.56  1000.8  786.16
    1021  797.68  1089.4  850.98  1113.5  865.05  1137.7  874.14  1175.5   873.5
#Mann= 7 ,-1,0
       0     .06       0   516.8    .045       0  605.28     .07       0
     680     .08       0     780     .07       0     880      .1       0
    1080     .06       0
Bank Sta=516.8,605.28
XS Rating Curve= 0 ,0
Exp/Cntr(USF)=0,0
Exp/Cntr=0.3,0.1

Type RM Length L Ch R = 1 ,9304    ,119.6,119.8,99.6
BEGIN DESCRIPTION:
Structure 6 XS 3
END DESCRIPTION:
XS GIS Cut Line= 6
1638182.33022486384702.0526861611638767.87797624385102.002712772
1638895.96654685384937.3174076971638977.00217316384783.088312468
1639005.75675023384568.7360106241639444.91756377384605.332745085
#Sta/Elev= 30
       0   885.5     162  909.42   283.1  854.95   370.3  837.27   394.5  821.62
   423.6  818.24   462.3  800.06   549.5  774.97   564.3  767.41   600.1  765.95
   636.7  749.78     690  733.86   709.1  729.15   791.8  727.81   935.3  717.88
   943.9  714.21   952.5  712.78 1073.53714.1917  1084.3   718.6  1171.5  727.64
  1308.3  723.05  1322.7  728.33  1346.8  726.45  1362.8  732.71  1390.9  731.81
  1559.5  796.23  1631.8   849.9  1671.9   871.7    1712  881.92    1749   883.4
#Mann= 10 ,-1,0
       0     .06       0     530     .07       0     630     .06       0
   779.1     .07       0  897.53     .06       0   943.9    .045       0
 1073.53     .07       0 1221.01     .08       0 1318.29     .07       0
 1508.29      .1       0
Bank Sta=943.9,1073.53
XS Rating Curve= 0 ,0
Exp/Cntr(USF)=0,0
Exp/Cntr=0.3,0.1

Type RM Length L Ch R = 1 ,9184    ,521,684.5,798
BEGIN DESCRIPTION:
Structure 6 XS 2
END DESCRIPTION:
XS GIS Cut Line= 6
1638181.24372569384721.6168428551638816.45847383385186.918181004
1638936.70488706385045.7593480821639033.42482814384857.547570853
1639072.63561506384637.967164086 1639443.8310646384664.107688702
#Sta/Elev= 30
       0  881.63   132.5  899.33   167.2  900.42     187  897.45   241.6  876.43
   281.2  855.82   384.8  833.27   395.3   829.1   410.1  817.53   444.9     813
   464.9  801.35   559.4  768.09   596.6  767.45   702.1  727.79   787.4  726.58
   822.1  720.71   971.9  719.98  993.24714.2509  1137.8  712.78  1154.1  714.22
  1280.7  727.67    1419  730.11  1459.1  739.23  1555.5  777.59  1579.4  794.08
  1599.5   801.7  1652.9  845.42  1697.5  872.34  1735.8  884.02  1779.6  885.58
#Mann= 13 ,-1,0
       0     .06       0     540     .07       0     560     .06       0
     730     .08       0   787.4     .07       0   837.4     .06       0
   937.4     .08       0   967.4     .07       0  993.24    .045       0
  1154.1     .08       0 1294.44     .07       0  1547.5      .1       0
  1697.5     .06       0
Bank Sta=993.24,1154.1
XS Rating Curve= 0 ,0
Exp/Cntr(USF)=0,0
Exp/Cntr=0.3,0.1

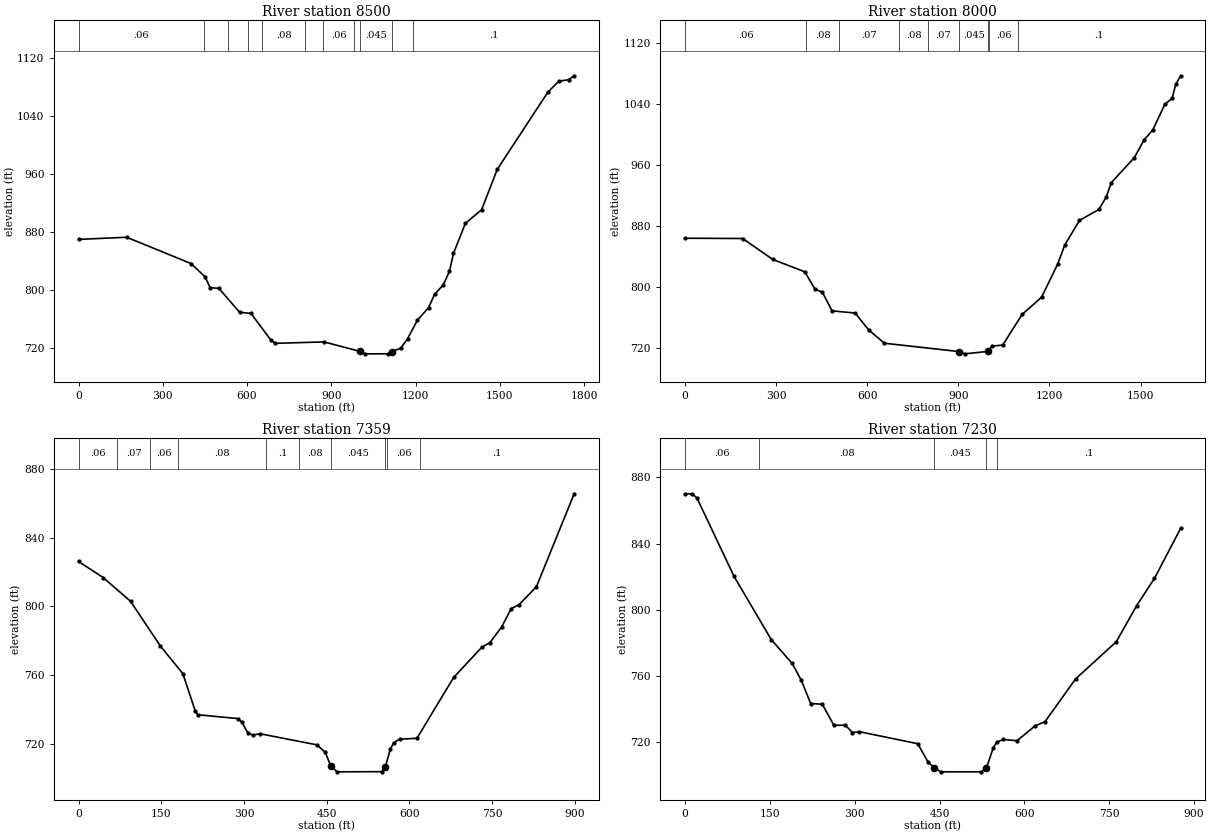
Type RM Length L Ch R = 1 ,8500    ,475.8,500,527.4
BEGIN DESCRIPTION:
Structure 6 XS 1
END DESCRIPTION:
XS GIS Cut Line= 6
  1638141.753112384736.2462455931638482.64350633385076.606785342
1638601.12358434385173.6997670081638689.52531043385256.161544338
1638743.10328725385336.0957676771639112.75674742386170.796526089
#Sta/Elev= 30
       0  870.07   171.6  873.02   400.5  836.86   450.5   818.7   468.6  803.65
   499.8  802.73   573.7  769.74   614.2  768.18     686  730.97   701.4  727.04
   874.5  728.97 1003.75 715.782  1018.8  712.56  1101.8  712.59  1114.6  715.77
  1147.3   720.2  1171.9  733.49  1206.9  758.96  1246.3  776.02  1268.2  794.62
  1298.8  807.39  1320.7   825.9  1335.3  850.97  1377.5  892.09  1435.3  910.87
  1491.3  966.56  1670.6  1072.3    1710 1087.82    1745 1089.84    1765 1095.27
#Mann= 11 ,-1,0
       0     .06       0  446.67     .08       0  531.78     .06       0
  601.78     .07       0  654.97     .08       0  805.86     .07       0
  872.09     .06       0  979.59     .07       0 1003.75    .045       0
  1114.6     .08       0 1189.59      .1       0
Bank Sta=1003.75,1114.6
XS Rating Curve= 0 ,0
Exp/Cntr(USF)=0,0
Exp/Cntr=0.3,0.1

Type RM Length L Ch R = 1 ,8000    ,628,640.7,666.1
XS GIS Cut Line= 6
1638112.95822209384737.1091047531638262.94512685384922.136293754
1638367.46296242385080.058878168 1638370.7624965385180.603624582
  1638362.886528385277.157893419 1638281.2193685386280.480033755
#Sta/Elev= 30
       0   864.2   189.8  863.85     289  836.38   394.6  820.18     428  797.32
   452.1  793.52   484.1  768.91   560.2  766.08   604.3   744.1   656.5  726.49
  902.56715.5215   921.4  712.56   997.6  715.74  1009.7  722.68  1045.8  724.01
    1110  764.28  1174.2  786.97  1226.4  829.84  1250.4  855.35  1298.6  887.57
  1362.8  901.98  1386.9  918.44  1403.3  937.04  1479.2   969.9  1511.3  993.13
    1540 1006.23  1579.6 1039.68  1603.6 1047.82  1615.7 1066.07  1631.7 1077.29
#Mann= 9 ,-1,0
       0     .06       0  398.18     .08       0  507.56     .07       0
  705.03     .08       0  798.78     .07       0  902.56    .045       0
   997.6     .07       0 1001.28     .06       0 1096.28      .1       0
Bank Sta=902.56,997.6
XS Rating Curve= 0 ,0
Exp/Cntr(USF)=0,0
Exp/Cntr=0.3,0.1

Type RM Length L Ch R = 1 ,7359    ,130.2,129.2,128.9
BEGIN DESCRIPTION:
Weir
END DESCRIPTION:
XS GIS Cut Line= 2
1637983.77636315384896.9579350161637566.65201186385693.093752694
#Sta/Elev= 30
       0  826.09    44.7  816.76    94.3  802.94   148.5  776.88   189.2  760.84
   211.8  739.01   216.3  736.93   288.5  734.73   295.8   732.9   306.6  726.58
   315.6  725.08   329.2  725.87   432.1  719.43   447.5  715.09  457.36707.1174
   469.2  703.72     550  703.82   556.5  706.68   565.4  716.89   571.3  720.58
   582.1  722.71   613.7  723.23   680.2   758.6   731.1   776.1   746.2  778.94
   767.2  787.97   784.7  798.71   798.8  800.92   830.4  811.44   898.8  865.47
#Mann= 10 ,-1,0
       0     .06       0      70     .07       0     130     .06       0
     180     .08       0     340      .1       0     400     .08       0
  457.36    .045       0   556.5     .07       0     560     .06       0
     620      .1       0
Bank Sta=457.36,556.5
XS Rating Curve= 0 ,0
Exp/Cntr(USF)=0,0
Exp/Cntr=0.3,0.1

Type RM Length L Ch R = 1 ,7230    ,221.6,235.7,266.8
BEGIN DESCRIPTION:
Structure 5 XS 4
END DESCRIPTION:
XS GIS Cut Line= 3
 1637778.7781717384835.9063945791637709.31743899385140.144403849
1637450.92351331385641.650894014
#Sta/Elev= 30
       0  870.11      13  870.09    21.2  867.53    86.8  820.09   152.5  781.88
   189.4  767.47   205.8  757.13   222.2  743.19   242.7  742.76   263.2  730.04
   283.7  730.02   296.1   725.6   308.4  726.12   411.5  718.87   429.5  707.86
   440.9  704.29     452  701.85     524  701.84     533  704.29   544.9  716.24
     551   719.8   562.7  721.42     587  720.68   618.5  729.57   636.5  732.23
   690.5  758.07   762.5  780.59   798.5  802.44     830  818.93   876.2  849.19
#Mann= 5 ,-1,0
       0     .06       0     130     .08       0   440.9    .045       0
     533     .06       0  552.07      .1       0
Bank Sta=440.9,533
XS Rating Curve= 0 ,0
Exp/Cntr(USF)=0,0
Exp/Cntr=0.3,0.1