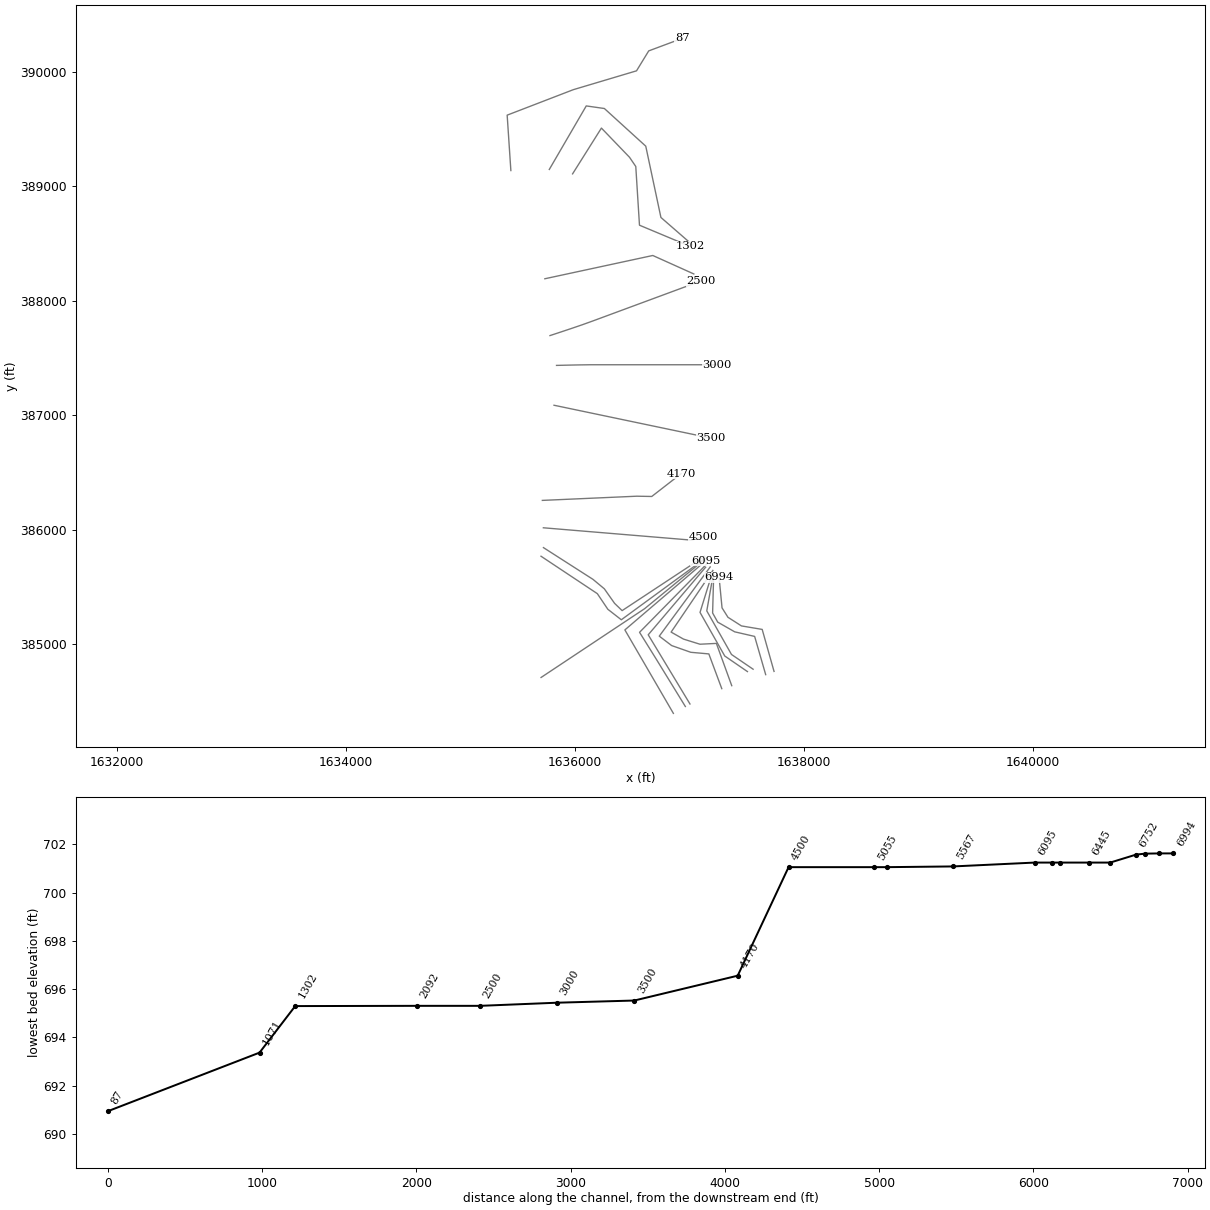
HEC-RAS study SFFSHGCK.prj: SFFSHGCK

--- SFFSHGCK.g01 (geometry) --- (continued)

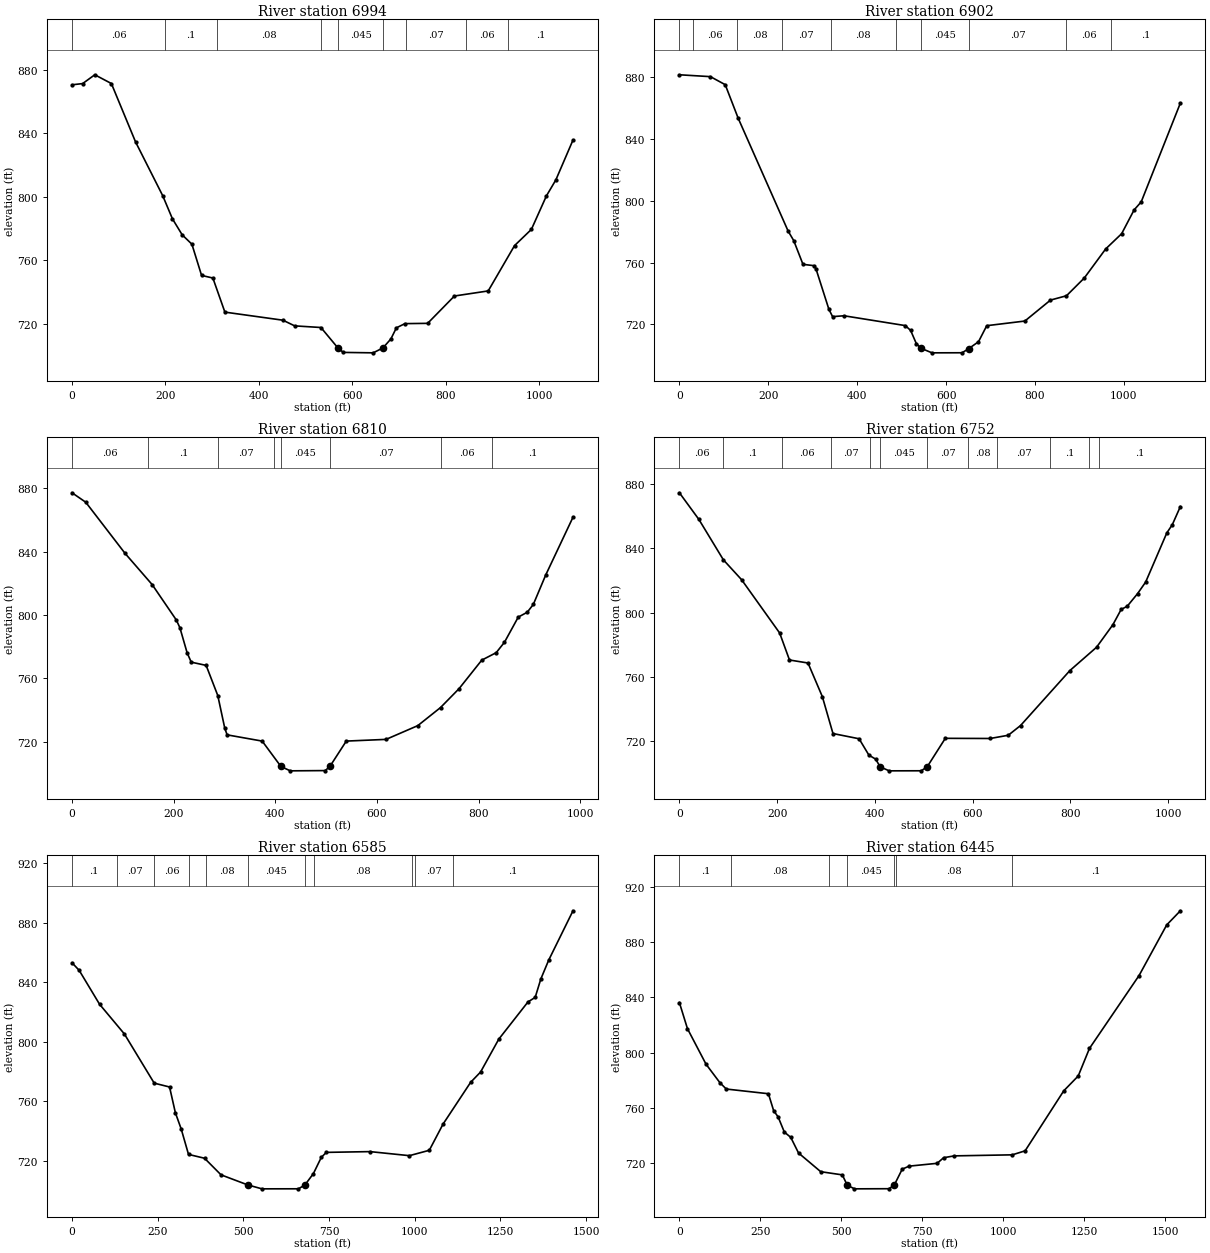
Type RM Length L Ch R = 1 ,6994    ,83.2,92.8,95.8
BEGIN DESCRIPTION:
Structure 5 XS 3
END DESCRIPTION:
XS GIS Cut Line= 6
1637737.22417769384761.6984089831637633.70770022385128.711374579
1637452.55386463385159.2957883791637334.92150386 385234.58049927
1637283.16326513385316.9231518081637257.28414576385585.124934359
#Sta/Elev= 30
       0  870.48    22.7  871.24    48.7  876.79    84.2  871.28   135.9  834.52
   194.1   800.6   214.9  786.03   235.7  775.98   256.5  770.07   277.2  750.41
   301.4  748.75   327.1  727.28   451.3  722.19   476.4  718.62   532.6  717.59
   569.6   704.5   580.6   701.9   644.4  701.63  665.19704.7029   682.3  710.37
   694.1  717.39   712.4  720.03     761  720.21   818.3  737.43   890.6  740.63
   946.9  769.17     983   779.4  1015.2  800.53  1035.3  810.55    1072  835.68
#Mann= 9 ,-1,0
       0     .06       0     200      .1       0     310     .08       0
  533.82     .07       0   569.6    .045       0  665.19     .08       0
  715.34     .07       0   842.6     .06       0   932.6      .1       0
Bank Sta=569.6,665.19
XS Rating Curve= 0 ,0
Exp/Cntr(USF)=0,0
Exp/Cntr=0.3,0.1

Type RM Length L Ch R = 1 ,6902    ,114.4,91.4,61
BEGIN DESCRIPTION:
Structure 5 XS 2
END DESCRIPTION:
XS GIS Cut Line= 6
1637664.29211401384733.4666423991637567.83357819 385067.54254698
1637393.73768425385107.5375496411637245.52090968385192.232849394
1637200.82061259385272.2228547161637210.23120145385608.651406513
#Sta/Elev= 30
       0  881.54    69.8  880.33   103.1  875.13   132.3  853.39   244.7  780.36
   257.2  774.26     278   758.9     303  758.02   307.1  756.14   336.3  729.83
   344.6  725.06   370.4  725.61   508.4  719.25   520.3  716.09   533.1  707.57
   543.9  704.53   568.3  701.63   636.1  701.68   651.2   704.4   672.9  708.81
   691.5   719.2   777.2   722.2   834.9  735.76   870.9  738.57   910.9  750.03
     959  768.83     995  778.72    1023   794.1    1039   799.3  1127.1  863.23
#Mann= 10 ,-1,0
       0     .07       0      30     .06       0     130     .08       0
     230     .07       0     340     .08       0  486.98     .07       0
   543.9    .045       0   651.2     .07       0  870.58     .06       0
  970.58      .1       0
Bank Sta=543.9,651.2
XS Rating Curve= 0 ,0
Exp/Cntr(USF)=0,0
Exp/Cntr=0.3,0.1

Type RM Length L Ch R = 1 ,6810    ,58.1,58.1,58
BEGIN DESCRIPTION:
Structure 5 XS 1
END DESCRIPTION:
XS GIS Cut Line= 4
1637554.39715561384780.9815339491637365.84424454384909.506651324
1637149.87123017385290.6355002131637205.61736384385605.318491347
#Sta/Elev= 30
       0  877.12      27  871.16   104.4  838.86   157.7  819.17   205.2  796.84
   212.3  791.92   226.5   776.1   234.6  770.21   263.9  768.18   286.8  749.17
   300.6  728.48   305.2  724.33   374.2  720.39     411  704.41   429.4  701.62
   498.3  701.78   507.6  704.48   539.7   720.4   617.9  721.47   680.4  730.15
   725.1  741.56   761.6  753.48   806.3  771.49   834.7   776.2     851   782.8
   878.1  798.66   895.7   801.7   907.7  806.62   932.2  825.27   985.8  861.69
#Mann= 8 ,-1,0
       0     .06       0     150      .1       0  288.19     .07       0
  398.19     .08       0     411    .045       0   507.6     .07       0
  726.26     .06       0  826.26      .1       0
Bank Sta=411,507.6
XS Rating Curve= 0 ,0
Exp/Cntr(USF)=0,0
Exp/Cntr=0.8,0.6

Type RM Length L Ch R = 1 ,6752    ,117.5,167.6,237.8
BEGIN DESCRIPTION:
Structure 4 XS 4
END DESCRIPTION:
XS GIS Cut Line= 4
1637504.92653803384760.1725534541637306.84540574384896.320247806
1637090.87239137385277.4490966951637193.69746609385608.339592128
#Sta/Elev= 30
       0  874.52    39.8  857.97      90   832.8   127.2  820.47   205.1  787.31
   225.2  770.52   263.1  768.65   292.4  747.75   314.2  724.78   367.6  721.53
   387.7  711.34   401.5  708.86   410.7  704.09   429.1  701.58   494.9  701.62
  507.15704.1975     544   721.8   635.8   721.7   672.8  723.71   697.9  729.75
   798.9  763.96   853.4  778.44   886.9  792.48   903.7  801.94   916.2  803.95
   937.2  811.73   953.9     819   997.2  849.58  1008.4  854.66  1024.9  865.96
#Mann= 12 ,-1,0
       0     .06       0      90      .1       0     210     .06       0
  310.36     .07       0  390.36     .08       0   410.7    .045       0
  507.15     .07       0  590.36     .08       0  650.36     .07       0
  758.43      .1       0  838.43     .06       0  858.43      .1       0
Bank Sta=410.7,507.15
XS Rating Curve= 0 ,0
Exp/Cntr(USF)=0,0
Exp/Cntr=0.8,0.6

Type RM Length L Ch R = 1 ,6585    ,149.8,139.3,125
BEGIN DESCRIPTION:
Structure 4 XS 3
END DESCRIPTION:
XS GIS Cut Line= 6
1637367.85856488384637.008106569 1637233.7576736 385006.37371938
1637090.24619347384999.3157777341636946.73471333385044.016074826
1636838.51294142385105.184902426 1637203.1732598385643.941114743
#Sta/Elev= 30
       0   853.2    20.8  848.14    80.4  825.31   152.7  805.38   239.8  772.29
   284.6  769.71   301.6  752.36   318.7  741.39   339.9  724.39   386.6  721.82
   434.7  710.67   512.8 703.885   554.2  701.25   660.7  701.28   679.5703.8417
   704.3  711.49   727.4  722.42   742.1  725.76   869.6  726.27   984.4  723.55
  1042.5  727.16  1082.7  744.79  1163.1  772.84  1192.1  779.76  1245.2  801.84
  1330.4  826.88  1351.5  829.95  1367.9  842.27  1390.9  854.98  1461.8  888.16
#Mann= 11 ,-1,0
       0      .1       0     130     .07       0     240     .06       0
     340     .07       0     390     .08       0   512.8    .045       0
   679.5     .07       0  706.96     .08       0  991.27      .1       0
 1001.27     .07       0 1111.27      .1       0
Bank Sta=512.8,679.5
XS Rating Curve= 0 ,0
Exp/Cntr(USF)=0,0
Exp/Cntr=0.3,0.1

Type RM Length L Ch R = 1 ,6445    ,221.5,182.9,127.5
BEGIN DESCRIPTION:
Structure 4 XS 2
END DESCRIPTION:
XS GIS Cut Line= 6
1637280.81061791  384611.12898721637167.88355157384914.620477981
1637010.25618814384928.7363612741636843.21823585384987.552541658
1636734.99646395385069.8951941951637179.64678765385674.525528543
#Sta/Elev= 30
       0  836.24    24.9  817.33    82.3  791.56   125.3  778.11   144.7   773.6
   274.7   770.2   290.9  757.85   304.5  753.46   323.8  742.41   343.6  738.57
   367.6  727.24   436.1  713.68   502.7  711.37   517.9  703.92   540.3  701.25
     647  701.34   663.3  704.11   687.5  715.49   708.6   717.7   795.4  719.75
   815.3  723.81   848.4  725.15  1027.1   725.9  1066.8   728.8    1186  772.29
  1230.7  783.07  1265.4  803.06  1418.5  855.91  1503.8  892.59  1545.9  902.83
#Mann= 7 ,-1,0
       0      .1       0     160     .08       0  460.87      .1       0
   517.9    .045       0   663.3     .07       0  669.44     .08       0
 1025.42      .1       0
Bank Sta=517.9,663.3
XS Rating Curve= 0 ,0
Exp/Cntr(USF)=0,0
Exp/Cntr=0.3,0.1

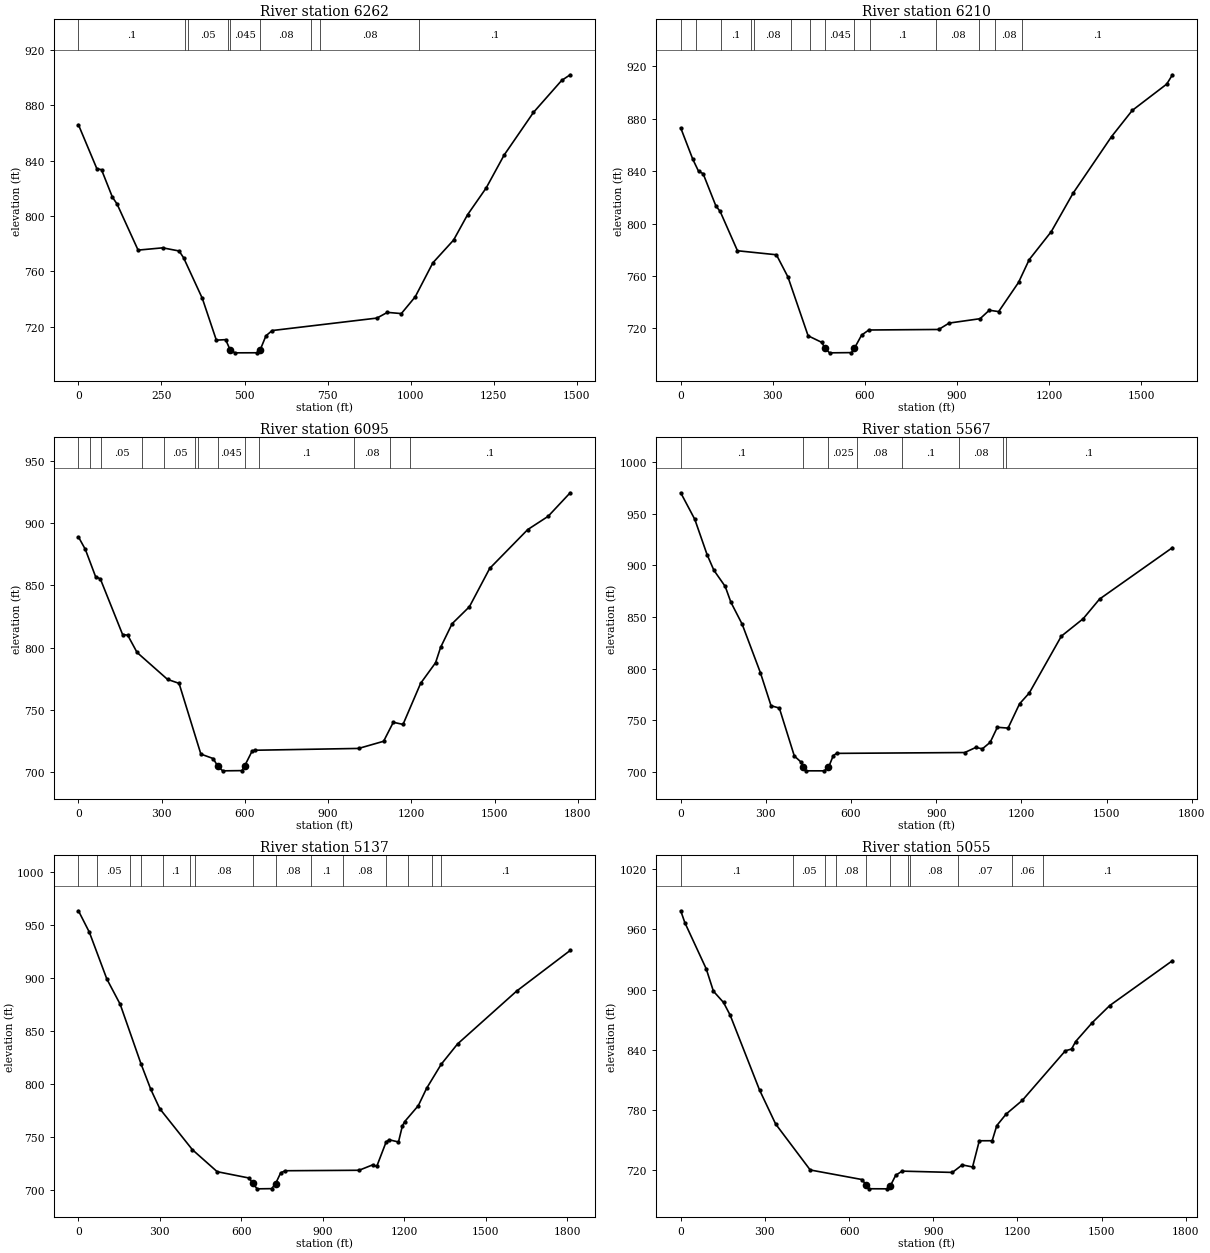
Type RM Length L Ch R = 1 ,6262    ,51.7,52.1,54.7
BEGIN DESCRIPTION:
Structure 3 XS 4 AND Structure 4 XS 1
END DESCRIPTION:
XS GIS Cut Line= 3
 1637003.1982465384477.0280959241636638.53792812385081.658430272
1637139.65178499385672.172881327
#Sta/Elev= 30
       0  865.97    55.5  834.21    69.5  833.51   102.2  813.72   116.2  808.77
   179.6  775.44   253.8  777.09   303.1  774.81   316.6  769.92   373.1  740.52
   415.2  710.41   443.2  710.78   456.4  703.63   471.2  701.25   536.6   701.3
  547.22 703.403   564.6  713.56   583.3  717.35   898.7  726.35   930.2  730.48
   972.2   729.6  1014.1  741.74  1067.1  766.25  1129.6  782.72  1171.5  800.95
  1227.8  820.39  1281.7  844.08    1370  874.88  1454.8  897.95  1480.6  902.07
#Mann= 9 ,-1,0
       0      .1       0     320     .08       0     330     .05       0
     450     .08       0   456.4    .045       0  547.22     .08       0
     700      .1       0  726.08     .08       0 1026.08      .1       0
Bank Sta=456.4,547.22
XS Rating Curve= 0 ,0
Exp/Cntr(USF)=0,0
Exp/Cntr=0.3,0.1

Type RM Length L Ch R = 1 ,6210    ,114.1,115.6,111.9
BEGIN DESCRIPTION:
Structure 3 XS 3
END DESCRIPTION:
XS GIS Cut Line= 4
1636962.78217735384455.1023773931636709.21908858384868.122666312
1636562.83215074385103.3873878481637150.99395458385702.005401534
#Sta/Elev= 30
       0  873.05    39.2  849.18    58.2  839.89    72.8  838.17   114.3  813.56
   128.4  809.24   184.7  779.24   311.5  776.17     349  759.23   414.7  714.27
   459.6   709.2   468.8705.0226   484.6  701.25   555.8  701.42   565.2  704.65
   588.8  714.78   612.3   718.7   839.8   719.1   873.8  723.98   974.7  727.34
  1004.5   733.8    1035  732.75  1099.8  755.05  1134.5  772.45  1206.4  793.87
  1277.2  823.15  1402.6  866.45  1469.9  886.42  1582.1  906.53  1600.9  913.66
#Mann= 14 ,-1,0
       0      .1       0      50     .05       0     130      .1       0
     230     .05       0     240     .08       0     360     .05       0
     420      .1       0   468.8    .045       0   565.2     .08       0
  614.64      .1       0  831.73     .08       0  971.73     .07       0
 1021.73     .08       0 1111.73      .1       0
Bank Sta=468.8,565.2
XS Rating Curve= 0 ,0
Exp/Cntr(USF)=0,0
Exp/Cntr=0.3,0.1

Type RM Length L Ch R = 1 ,6095    ,594.2,527.9,456.5
BEGIN DESCRIPTION:
Structure 3 XS 2
END DESCRIPTION:
XS GIS Cut Line= 3
1636858.22007889384394.9791707781636434.74358013 385124.29980754
1637140.53774473385728.145926149
#Sta/Elev= 30
       0   888.9    24.9   878.9    61.9  856.97    78.8   855.3   159.1  810.62
   177.6  810.07   211.3  796.21     321  774.63   362.6  771.44   441.2   714.7
   485.5  711.12   501.5705.2426   519.8  701.25   589.2  701.43   599.6  705.47
   626.2  717.26   635.5  717.77  1009.8  719.23  1099.8  724.97  1134.7  740.19
  1169.8  738.51  1233.2  771.45  1287.1     788  1305.2  800.29  1346.6  819.27
  1409.1  832.93  1482.1  863.64    1619  894.78  1692.7  905.44  1772.2  924.33
#Mann= 13 ,-1,0
       0     .05       0      40      .1       0      80     .05       0
     230      .1       0     310     .05       0     420      .1       0
     430     .08       0   501.5    .045       0   599.6     .08       0
     650      .1       0  993.35     .08       0 1123.35     .07       0
 1193.35      .1       0
Bank Sta=501.5,599.6
XS Rating Curve= 0 ,0
Exp/Cntr(USF)=0,0
Exp/Cntr=0.3,0.1

Type RM Length L Ch R = 1 ,5567    ,501.4,429.9,367.7
BEGIN DESCRIPTION:
Structure 2 XS 4 AND Structure 3 XS 1
END DESCRIPTION:
XS GIS Cut Line= 3
 1635702.8088909384708.6654661591636607.27104259385309.897532307
1637106.55506273385720.303768764
#Sta/Elev= 30
       0  970.31    49.6  944.57    92.8  910.46   116.8   895.3   156.7  879.62
   176.8   864.3   216.5  843.02   280.7   796.1   318.2  764.13   347.4  761.87
   400.2  715.47     425  709.28   430.7  704.54   440.5   701.1   505.6  701.09
   520.5704.4152   537.5  715.86     549     718  1000.6  718.81  1039.5  723.74
  1062.6   722.4  1090.2  728.69  1115.4  743.27  1153.2  742.47  1193.7     766
  1227.8  776.43  1340.9  831.47  1417.8  848.36  1475.5  867.39  1732.4  917.22
#Mann= 8 ,-1,0
       0      .1       0   430.7    .045       0   520.5    .025       0
     620     .08       0     780      .1       0     980     .08       0
 1136.06     .07       0 1146.06      .1       0
Bank Sta=430.7,520.5
XS Rating Curve= 0 ,0
Exp/Cntr(USF)=0,0
Exp/Cntr=0.3,0.1

Type RM Length L Ch R = 1 ,5137    ,82,81.7,83.1
BEGIN DESCRIPTION:
Structure 2 XS 3
END DESCRIPTION:
XS GIS Cut Line= 5
1635702.54748566 385768.140928811636194.25075367385441.122965875
1636286.00399507385304.6694273841636403.63635583385212.916185985
1637135.30963981385749.319751087
#Sta/Elev= 30
       0  963.74    40.3  943.42   104.7  899.23   153.8  875.39   230.4  819.19
   266.5  795.05   299.7  776.73   419.8  738.02   511.1  717.26   629.7  711.22
   641.4706.1846   658.6  701.06   711.7  701.25   726.2     706     745  716.16
   761.7  718.16  1033.7   718.6  1083.3  723.66  1098.8  722.22  1133.5   745.4
  1144.6  747.41  1178.9  745.32  1193.2  760.44  1201.8   764.6  1251.9  779.63
  1282.4  795.97  1336.3  818.74  1396.4  837.91    1614  887.85  1811.4  926.26
#Mann= 15 ,-1,0
       0      .1       0      70     .05       0     190      .1       0
     230     .05       0     310      .1       0     410     .05       0
     430     .08       0   641.4    .045       0   726.2     .08       0
  854.95      .1       0  974.14     .08       0 1134.14     .07       0
 1214.14      .1       0 1304.14     .06       0 1334.14      .1       0
Bank Sta=641.4,726.2
XS Rating Curve= 0 ,0
Exp/Cntr(USF)=0,0
Exp/Cntr=0.3,0.1

Type RM Length L Ch R = 1 ,5055    ,510.4,555.2,584.1
BEGIN DESCRIPTION:
Structure 2 XS 2
END DESCRIPTION:
XS GIS Cut Line= 6
1635723.72131059385843.4256397021636156.60839822385565.813268289
1636255.41958127385483.4706157511636344.82017545385356.427666122
1636410.69429748385292.9061913071637130.60434538 385768.14092881
#Sta/Elev= 30
       0   978.6    14.7  966.72    90.8   920.7   116.5  898.34   152.5  887.08
   176.1  874.46   280.8  799.74   338.2  765.78   461.4   719.9   646.5  710.31
   661.1   704.5   671.9  701.14   734.5  701.06  747.37704.2292   766.1  714.61
     789  718.73   968.1  717.45  1003.1  724.97    1040  722.88    1064  749.03
  1109.9  749.08  1126.3  764.18  1159.8  775.75  1217.4  789.38  1370.7  838.87
  1392.8  840.59  1407.3  848.09  1466.6  866.98  1528.5  883.93  1752.4   928.8
#Mann= 11 ,-1,0
       0      .1       0     400     .05       0  514.26     .07       0
  554.26     .08       0   661.1    .045       0  747.37      .1       0
  808.23     .07       0  818.23     .08       0  989.74     .07       0
 1179.74     .06       0 1289.74      .1       0
Bank Sta=661.1,747.37
XS Rating Curve= 0 ,0
Exp/Cntr(USF)=0,0
Exp/Cntr=0.3,0.1

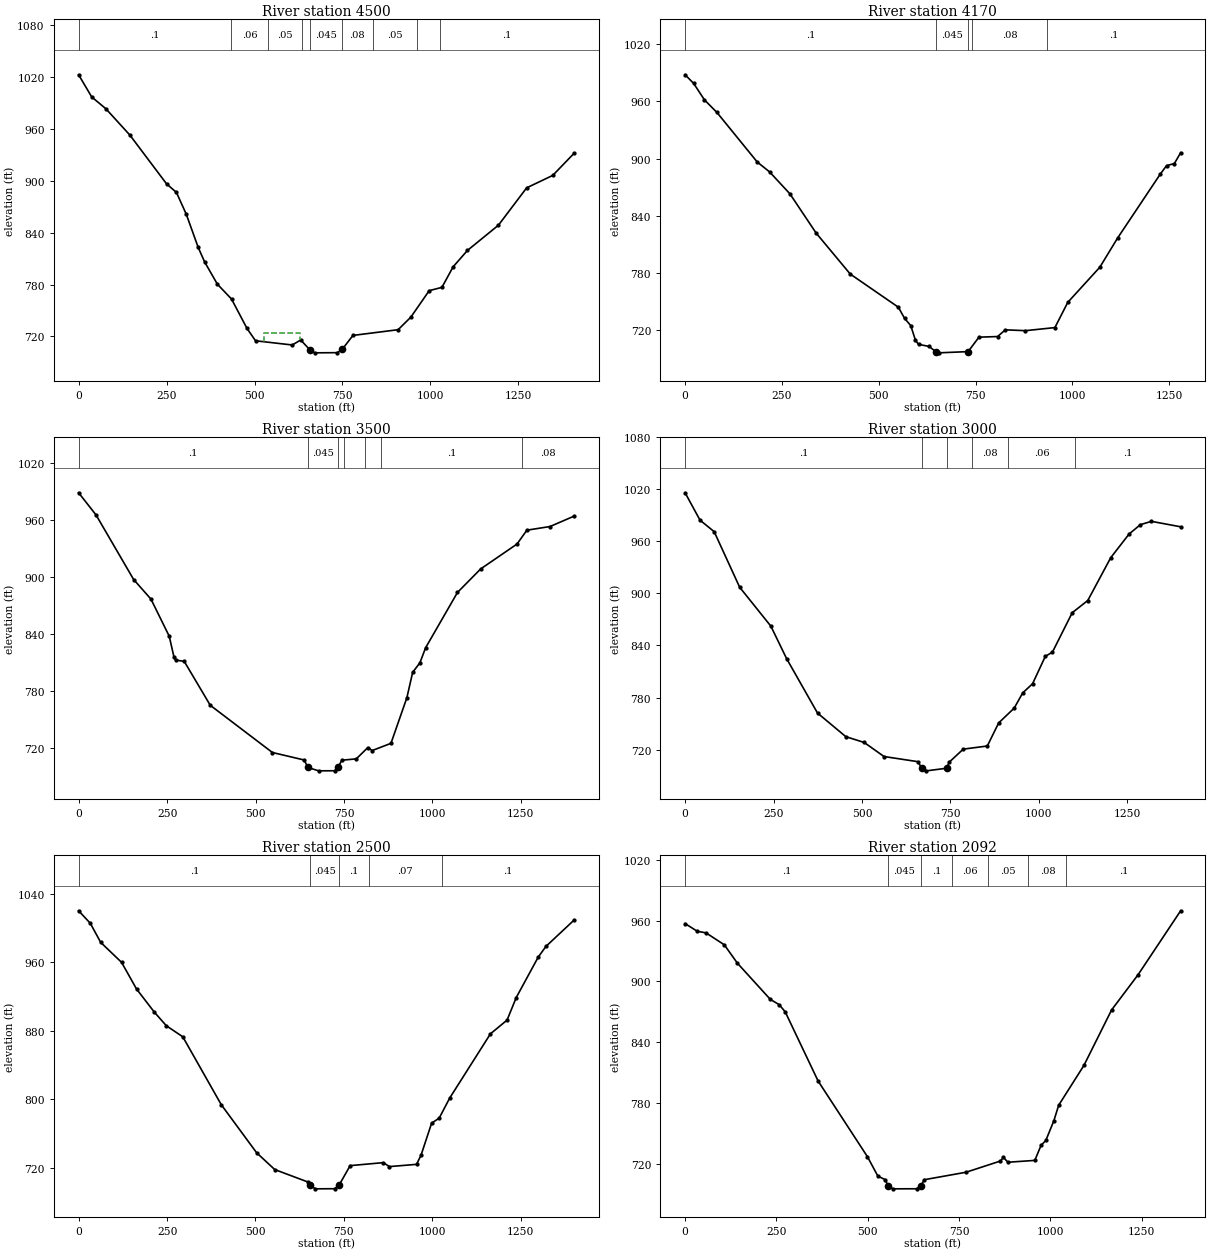
Type RM Length L Ch R = 1 ,4500    ,324.2,329.8,336.2
BEGIN DESCRIPTION:
Structure 2 XS 1
END DESCRIPTION:
XS GIS Cut Line= 6
1635723.02697834386016.7663223451635921.16831434386000.254544333
 1636115.8063765385984.0354166781636209.23237076385976.249671087
1637019.70417501 385908.710764171637122.30009842385940.404926509
#Sta/Elev= 30
       0 1022.39    37.2  996.75    77.4  983.15   145.6  952.73     250  896.31
     278  886.46   306.1  861.12   339.9  822.83   358.3  805.99   394.4   780.4
   434.6  763.24   478.7  729.19   502.8     715   607.2  710.14   631.3   715.9
     657  704.65   671.4  701.06   735.6  701.26  748.96704.9714   779.8   721.2
   908.2   727.8   944.3   742.3   996.5  772.91  1032.7  776.74  1064.6  800.53
  1105.3  819.43  1193.2  848.52  1273.5  891.73  1347.7   906.1  1408.6  931.76
#Mann= 9 ,-1,0
       0      .1       0  434.14     .06       0  537.89     .05       0
  635.39    .025       0     657    .045       0  748.96     .08       0
  835.39     .05       0  962.89     .07       0 1026.64      .1       0
#XS Ineff= 1 ,-1
  526.82  629.19  724.14
Permanent Ineff=
       T
Bank Sta=657,748.96
XS Rating Curve= 0 ,0
Exp/Cntr(USF)=0,0
Exp/Cntr=0.3,0.1

Type RM Length L Ch R = 1 ,4170    ,682.1,670.2,661.1
BEGIN DESCRIPTION:
Weir
END DESCRIPTION:
XS GIS Cut Line= 6
1635714.03456339 386256.112438171636201.44402164386277.776764913
1636363.78359197 386284.992629751636538.61099823 386292.76295541
1636669.48549117 386290.428610621636924.84780708386488.733826744
#Sta/Elev= 30
       0  987.77    22.1  978.74    50.1  961.42    82.2  948.32   186.3  896.42
   218.3  886.01   270.7  863.06   338.4  821.98   426.5  779.05   550.6  744.38
   566.6  732.74   582.7   725.1   594.7  709.92   602.7  705.47   630.3  703.24
   646.7  697.96   654.7  696.56   730.8  697.84   758.8  712.97   806.9  713.62
   826.9  720.65   878.9  719.78   954.9  723.01   988.2  749.44    1071  786.27
  1116.6  816.66  1227.1   883.8  1243.2  892.57  1263.5  894.85  1279.6  906.13
#Mann= 5 ,-1,0
       0      .1       0   646.7    .045       0   730.8      .1       0
  740.39     .08       0  935.39      .1       0
Bank Sta=646.7,730.8
XS Rating Curve= 0 ,0
Exp/Cntr(USF)=0,0
Exp/Cntr=0.3,0.1

Type RM Length L Ch R = 1 ,3500    ,490.9,500,507.2
XS GIS Cut Line= 6
1635815.96478459 387087.62113601  1635913.454419387067.179575846
1636201.71729392387006.7380956711636293.47203167386987.498960927
1636550.38523176386933.6299741721637186.93349934386800.160424843
#Sta/Elev= 30
       0  988.51    49.2  965.16   155.5  897.12   204.5  876.44   256.1  837.38
   269.6  815.31     274  812.26   298.5  810.89   372.1   764.6   547.8  714.84
   637.7  706.94     648   699.1   678.4  695.53   723.5  695.62  733.51699.3878
     744  706.71   784.9  708.17   817.5  720.04   829.8  716.92   882.9   724.5
   927.9  772.59   944.2  799.28   964.7  809.36     981  825.32  1070.9  883.49
  1136.3  908.21  1239.3  934.52  1267.1   949.1  1332.5  952.94  1400.8  963.94
#Mann= 7 ,-1,0
       0      .1       0     648    .045       0  733.51      .1       0
  750.39     .07       0  810.39     .08       0  855.39      .1       0
 1251.95     .08       0
Bank Sta=648,733.51
XS Rating Curve= 0 ,0
Exp/Cntr(USF)=0,0
Exp/Cntr=0.3,0.1

Type RM Length L Ch R = 1 ,3000    ,486.7,500,513.1
XS GIS Cut Line= 6
1635837.88928142 387435.799901591635937.49866226 387438.10763976
1636036.71729584387440.0941843391636135.15509109387441.437029421
1636232.02989735387441.4928035891637238.67060059387441.492803589
#Sta/Elev= 30
       0 1016.14    42.2  984.54    82.2  971.29   154.3  907.15   242.4  862.33
     287  824.82   374.3   762.1   454.3  734.87   506.3  728.15   562.3  711.96
   658.3     706  668.37698.7393   682.3  695.44   739.2  698.44   746.3  705.33
   786.3  720.47   854.3  724.08   886.3  750.64   930.3  767.79   954.3  785.28
   982.3  795.93  1018.3  827.52  1038.3   832.3  1094.3  877.79  1138.3   891.9
  1203.2  941.29  1255.2  968.64  1287.2   979.4  1318.3  983.18  1400.8  976.91
#Mann= 6 ,-1,0
       0      .1       0  668.37    .045       0   739.2     .06       0
  810.45     .08       0  912.95     .06       0 1103.57      .1       0
Bank Sta=668.37,739.2
XS Rating Curve= 0 ,0
Exp/Cntr(USF)=0,0
Exp/Cntr=0.3,0.1

Type RM Length L Ch R = 1 ,2500    ,413.9,407.7,401.8
XS GIS Cut Line= 6
1635780.86347684387696.4168344291635875.52076784387727.637572512
1635969.67838793387759.0827195941636062.83765042387790.976028502
1636153.99855734387823.7659891691637098.08820459388173.080251172
#Sta/Elev= 30
       0 1020.03    32.9 1005.46    62.4  983.13   121.4  959.79   163.6  928.75
   214.2  901.57     248  885.75   294.5  872.86   403.3  793.53   503.2  737.45
   554.4  717.82   648.2   703.3  654.72699.3842   669.5  695.31   723.4  695.46
   735.9  699.34   767.6  722.41   861.4  725.91   878.5  721.28   955.3  723.91
   968.1  734.73   997.9     772  1019.2  777.84  1049.1  801.38  1164.2  876.34
  1211.2  892.35  1237.1  918.68  1299.3  965.95  1321.1  978.42  1400.9 1009.28
#Mann= 5 ,-1,0
       0      .1       0  654.72    .045       0   735.9      .1       0
  820.54     .07       0 1026.79      .1       0
Bank Sta=654.72,735.9
XS Rating Curve= 0 ,0
Exp/Cntr(USF)=0,0
Exp/Cntr=0.3,0.1

Type RM Length L Ch R = 1 ,2092    ,912.7,790,699.3
BEGIN DESCRIPTION:
Structure 1 XS 4
END DESCRIPTION:
XS GIS Cut Line= 3
1635736.05945748388192.9539318431636678.40923373388396.269123293
1637036.63123771388234.907860237
#Sta/Elev= 30
       0  957.11    33.4  949.52    57.3  947.94   107.4  936.16   143.3  917.99
   233.3  882.32   257.9  877.03   274.2  869.96   364.2  801.74   499.3  727.01
   527.9  707.84   548.4  704.32   555.3698.3846   568.8  695.31   634.3  695.38
   645.8698.4457   654.8  704.31   769.4   711.7   863.5  722.77   871.7  726.36
   883.9  721.56   957.6  723.38   974.7  738.23   987.8  743.09  1009.8  762.56
  1022.9   777.8  1092.2  817.19  1167.8  871.85  1240.4  906.64  1356.9  969.75
#Mann= 7 ,-1,0
       0      .1       0   555.3    .045       0   645.8      .1       0
     730     .06       0     830     .05       0     940     .08       0
 1044.03      .1       0
Bank Sta=555.3,645.8
XS Rating Curve= 0 ,0
Exp/Cntr(USF)=0,0
Exp/Cntr=0.3,0.1

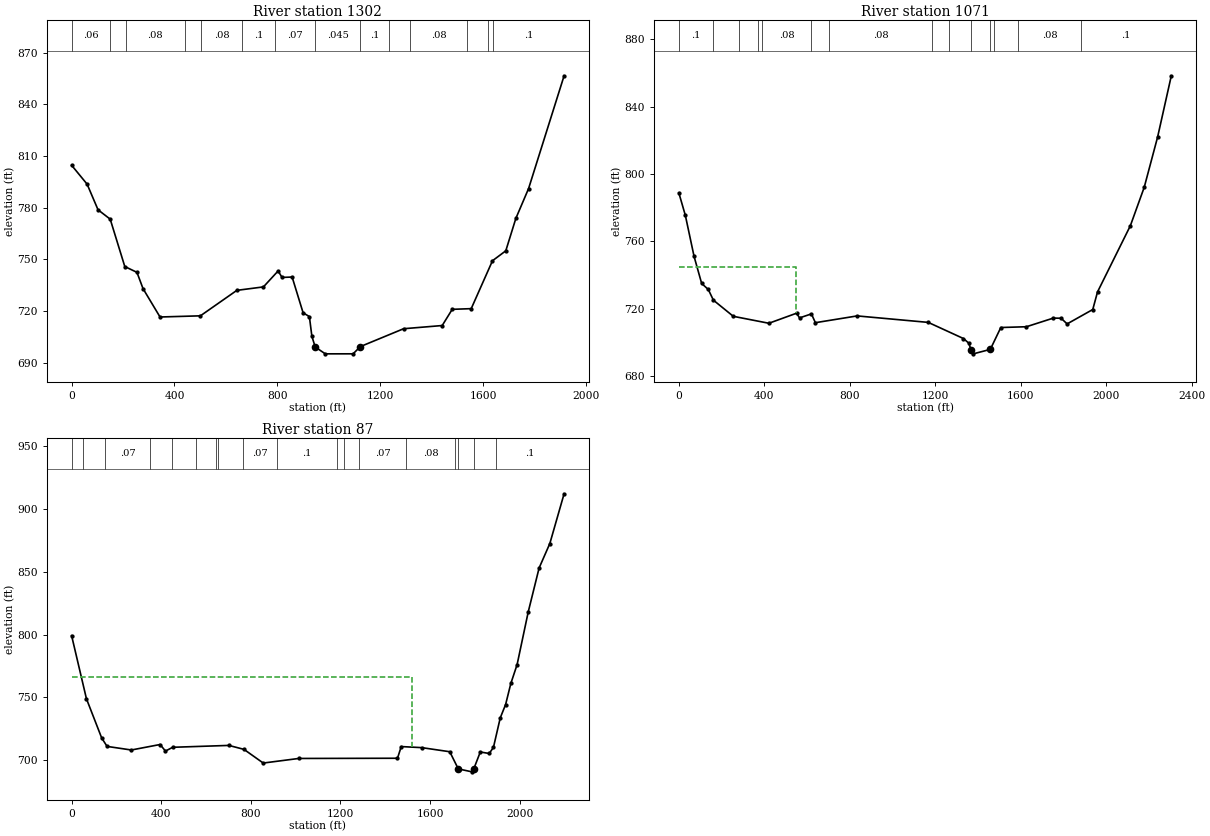
Type RM Length L Ch R = 1 ,1302    ,174.8,231.3,264.4
BEGIN DESCRIPTION:
Structure 1 XS 3
END DESCRIPTION:
XS GIS Cut Line= 6
1635978.10135207389109.4859060021636229.82492243389509.661838381
1636475.09404228389254.7110427521636529.95687172389174.030411224
1636562.22912433388660.9015947061637001.13175984388476.949754822
#Sta/Elev= 30
       0  804.64    60.3  793.68   102.8  778.81   150.1  773.38   206.8  745.92
   254.1  742.55   277.7  733.11   343.8  716.66   500.8  717.34   642.5  732.11
   745.8  734.11     803  743.37   818.1   739.6   857.4  739.83   900.1  719.08
   924.5   716.9   934.2  705.47   947.1  699.28   986.3   695.3  1094.5  695.31
  1122.5  699.49  1290.8  709.86  1440.9  711.71  1479.9  721.11  1553.7   721.5
  1636.4  749.28  1688.1  755.03  1727.2  773.81  1776.8  791.16  1914.8  856.52
#Mann= 14 ,-1,0
       0     .06       0     150     .07       0     210     .08       0
     440      .1       0  502.76     .08       0  663.84      .1       0
  789.53     .07       0   947.1    .045       0  1122.5      .1       0
  1235.6     .06       0  1315.6     .08       0 1538.87      .1       0
 1618.87     .07       0 1638.87      .1       0
Bank Sta=947.1,1122.5
XS Rating Curve= 0 ,0
Exp/Cntr(USF)=0,0
Exp/Cntr=0.3,0.1

Type RM Length L Ch R = 1 ,1071    ,900.9,983.7,1066.6
BEGIN DESCRIPTION:
Structure 1 XS 2
END DESCRIPTION:
XS GIS Cut Line= 6
1635774.78616062389148.2126091351636097.50868673389703.295354048
1636255.64272452389680.7047772211636617.09195377389351.527800586
1636749.40818947388728.6733251891637023.72233667388489.858655866
#Sta/Elev= 30
       0  788.87    30.5  775.51    71.4  751.13   106.8  735.13   137.9  731.53
   161.8   725.2   254.9  715.62   421.4   711.5     551  717.47   564.9  714.69
   620.4  717.06   638.9  711.84   834.5  715.86    1167  712.02  1331.6  702.45
  1356.2  699.76  1368.4  695.47  1377.6  693.37  1457.4  696.01  1506.5  708.98
  1626.2  709.44  1752.3  714.57  1788.7  714.48  1816.7  711.12  1936.7  719.65
    1959   730.1  2112.7  769.37  2177.5  792.14  2240.2  821.99  2304.2  858.27
#Mann= 14 ,-1,0
       0      .1       0     160     .07       0     280     .08       0
     370     .07       0     390     .08       0     620     .07       0
  702.08     .08       0 1185.44     .07       0 1265.44      .1       0
  1368.4    .045       0  1457.4     .07       0 1476.36      .1       0
 1586.49     .08       0 1882.72      .1       0
#XS Ineff= 2 , 0
          548.17  744.86
Permanent Ineff=
       F       F
Bank Sta=1368.4,1457.4
XS Rating Curve= 0 ,0
Exp/Cntr(USF)=0,0
Exp/Cntr=0.3,0.1

Type RM Length L Ch R = 1 ,87      ,,,
BEGIN DESCRIPTION:
Structure 1 XS 2
END DESCRIPTION:
XS GIS Cut Line= 6
1635439.15473346389138.5309333521635406.88248085 389622.61472252
1635984.55580259389845.2932655381636536.41132224390009.881753855
1636642.90975586390184.1519179561636936.58725462390293.877576834
#Sta/Elev= 30
       0  799.15    66.2  749.01   134.3  717.82   158.4  711.14   266.6  708.29
   394.9  712.65   418.9  707.44     451  710.44   701.8  711.93   769.2  708.79
   855.2  697.92  1013.8  701.57  1454.4  701.74  1471.1  711.01  1562.7  710.17
  1687.7  706.91  1725.6  693.29  1786.6  690.94  1794.6  693.17  1823.9  706.71
  1863.7  705.52  1882.6  710.35    1913  733.81  1936.9  744.41  1960.2  761.13
  1988.2  776.14  2037.9  818.02  2086.4  852.88  2134.3  872.33  2197.9  911.83
#Mann= 18 ,-1,0
       0     .06       0      50     .08       0     150     .07       0
     350     .08       0     450     .06       0  555.16     .08       0
  645.16    .025       0  655.16     .08       0  765.16     .07       0
  915.16      .1       0 1184.26     .06       0 1214.26      .1       0
 1284.26     .07       0 1494.26     .08       0 1710.14     .07       0
  1725.6    .045       0  1794.6     .08       0 1894.38      .1       0
#XS Ineff= 2 , 0
         1520.49  766.38
Permanent Ineff=
       F       F
Bank Sta=1725.6,1794.6
XS Rating Curve= 0 ,0
Exp/Cntr(USF)=0,0
Exp/Cntr=0.3,0.1
LCMann Table=0

Chan Stop Cuts=-1
Use User Specified Reach Order=0
Composite Channel Slope=5