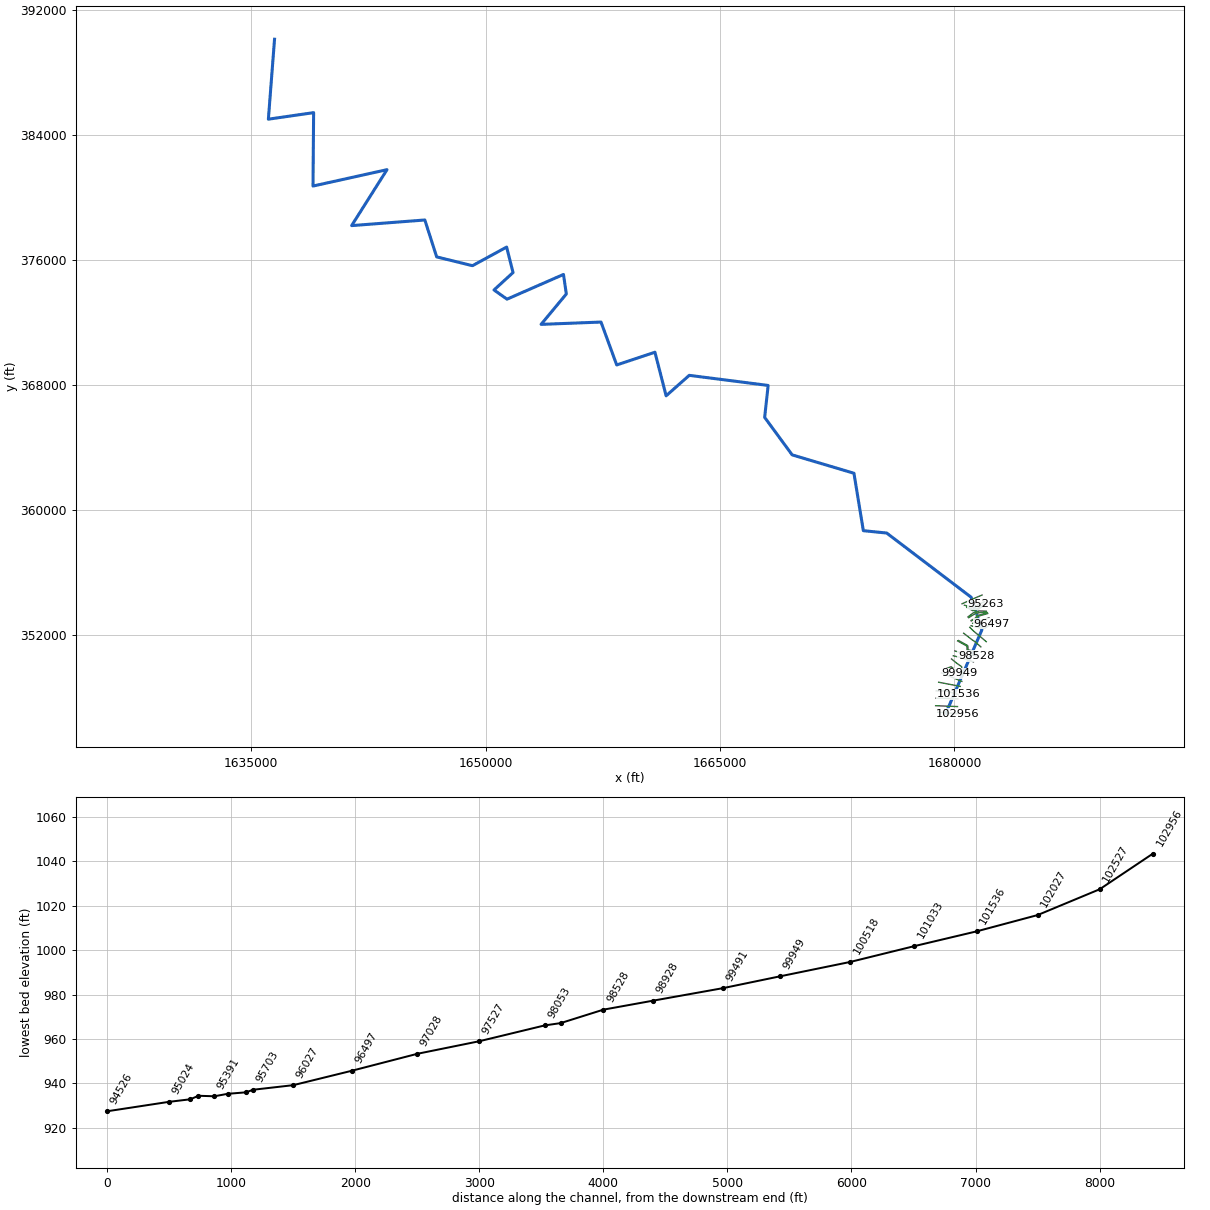
--- SFFSHGCK.prj (project) ---

Proj Title=SFFSHGCK
Current Plan=p01
Default Exp/Contr=0,0
English Units
Geom File=g01
Flow File=f01
Plan File=p01
BEGIN DESCRIPTION:
---------- MODELED AS PART OF WVEMD CTP PROGRAM, 2023----------
Stream Name: South Fork Fishing Creek
Flood Zone:  AFH
Wetzel County, WV
HEC-RAS Version: RAS 6.3
Vertical Datum: NAVD88
Projection: NAD 1983 StatePlane West Virginia S FIPS 4702 (US Feet)
Terrain: 1-meter West Virginia FEMA R3 South Central (collected 2018-2020)
Land Use: 2019 NLCD
Hydrologic Method:
WV SIR2010-5033 regression equations
Additional Model Notes:
Uses a shared XS and KWSEL tie-in with FISHINGCK because it is the dominant flow path at the fork
END DESCRIPTION:
DSS Export Rating Curves= 0
DSS Export Rating Curve Sorted= 0
DSS Export Volume Flow Curves= 0
DXF OffsetX= 0
DXF OffsetY= 0
DXF ScaleX= 0
DXF ScaleY= 0

--- SFFSHGCK.p01 (plan) ---

Plan Title=Floodplain
Program Version=6.31
Short Identifier=Floodplain
Geom File=g01
Flow File=f01
Subcritical Flow
K Sum by GR= 0
Std Step Tol= 0.01
Critical Tol= 0.01
Num of Std Step Trials= 20
Max Error Tol= 0.3
Flow Tol Ratio= 0.001
Split Flow NTrial= 30
Split Flow Tol= 0.02
Split Flow Ratio= 0.02
Log Output Level= 0
Friction Slope Method= 1
Unsteady Friction Slope Method= 2
Unsteady Bridges Friction Slope Method= 1
Parabolic Critical Depth
Global Vel Dist= 0 , 0 , 0
Global Log Level= 0
CheckData=True
Encroach Param=-1 ,0,0, 0
Mapping Interval=1HOUR
Computation Time Step Use Courant=        0
Computation Time Step Use Time Series=    0
Computation Time Step Count To Double=0
Computation Time Step Max Doubling=0
Computation Time Step Max Halving=0
Computation Time Step Residence Courant=0
Run HTab= 0
Run UNet= 0
Run Sediment= 0
Run PostProcess= 0
Run WQNet= 0
Run RASMapper=-1
UNET Theta= 0
UNET Theta Warmup= 0
UNET ZTol= 0
UNET ZSATol= 0
UNET MxIter= 0
UNET Max Iter WO Improvement= 0
UNET MaxInSteps= 0
UNET DtIC= 0
UNET DtMin= 0
UNET MaxCRTS= 0
UNET WFStab= 0
UNET SFStab= 0
UNET WFX= 1
UNET SFX= 1
UNET Gravity=32.17405
UNET 1D Methodology=Finite Difference
UNET DSS MLevel= 1
UNET Pardiso=0
UNET DZMax Abort= 0
UNET Use Existing IB Tables= 0
UNET Froude Reduction=False
UNET Froude Limit= 0
UNET Froude Power= 0
UNET D1 Cores= 0
UNET WindReference=Eulerian
UNET WindDragFormulation=Hsu (1988)
UNET D2 Coriolis=0
UNET D2 Cores= 0
UNET D2 Theta= 1
UNET D2 Theta Warmup= 1
UNET D2 Z Tol= 0.01
UNET D2 Volume Tol= 0.01
UNET D2 Max Iterations= 20
UNET D2 Equation= 0
UNET D2 RampUpFraction=0.1
UNET D2 TimeSlices= 1
UNET D2 Turbulence Formulation=Non-Conservative (original)
UNET D2 Eddy Viscosity=0.3
UNET D2 Transverse Eddy Viscosity=0.1
UNET D2 Smagorinsky Mixing=0
UNET D2 BCVolumeCheck=0
UNET D2 Cores=0
UNET D2 SolverType=PARDISO (Direct)
UNET D2 Minimum Iterations= 3
UNET D2 Maximum Iterations= 30
UNET D2 Restart Number= 10
UNET D2 Relaxation Coeff=1.3
UNET D2 SOR Precondition Iterations= 10
UNET D2 ILUT Maximum Fill= 8
UNET D2 ILUT Tolerance=1E-08
UNET D2 Convergence Tolerance=0.00001
UNET D1D2 MaxIter= 0
UNET D1D2 ZTol=0.01
UNET D1D2 QTol=0.1
UNET D1D2 MinQTol=1
Write IC File= 0
Write IC File at Fixed DateTime=0
Write IC File at Sim End=0
Echo Input=False
Echo Parameters=False
Echo Output=False
Write Detailed= 0
HDF Write Warmup=0
HDF Write Time Slices=0
HDF Flush=0
HDF Compression= 1
HDF Chunk Size= 1
HDF Spatial Parts= 1
HDF Use Max Rows=0
HDF Fixed Rows= 1
Calibration Method= 0
Calibration Iterations= 20
Calibration Max Change=0.05
Calibration Tolerance=0.2
Calibration Maximum=1.5
Calibration Minimum=0.5
Calibration Optimization Method= 1
WQ AD Non Conservative
WQ ULTIMATE=-1
WQ Max Comp Step=1HOUR
WQ Output Interval=15MIN
WQ Output Selected Increments= 0
WQ Create Restart=0
WQ Fixed Restart=0
WQ System Summary=0
WQ Write To DSS=0
Sorting and Armoring Iterations= 10
XS Update Threshold= 0.02
Bed Roughness Predictor= 0
Hydraulics Update Threshold= 0.02
Energy Slope Method= 1
Volume Change Method= 1
Sediment Retention Method= 0
Sediment TS Multiplier= 1
Warm Up Method= 0
XS Weighting Method= 0
Number of US Weighted Cross Sections= 1
Number of DS Weighted Cross Sections= 1
Upstream XS Weight=0
Main XS Weight=1
Downstream XS Weight=0
Number of DS XS's Weighted with US Boundary= 1
Upstream Boundary Weight= 1
Weight of XSs Associated with US Boundary= 0
Number of US XS's Weighted with DS Boundary= 1
Downstream Boundary Weight= 0.5
Weight of XSs Associated with DS Boundary= 0.5
Percentile Method= 0
Sediment Output Level= 3
Mass or Volume Output= 0
Output Increment Type= 1
Profile and TS Output Increment= 1
Transport Output Increment 1
XS Output Flag= 0
XS Output Increment= 10
Read HDF5 Sediment Hotstart= 0
Sediment Hotstart Type= 0
Write Gradation File= 0
Read Gradation Hotstart= 0
Write HDF5 File= 1
Write Binary Output= 1
Write DSS Sediment File= 0
DSS Sediment Output Type= 1
SV Curve= 0
Specific Gage Flag= 0
Subcell Erosion Methods= 0
Subcell Deposition Methods= 0
Advection Scheme= 1
Matrix Solver= 0
Implicit Weighting Factor= 1
Maximum Outer Loop Convergence Iterations= 5
Convergence Maximum Absolute= 0.001
Convergence RMSE= 0.0001
Grain Fractions Max Abs Error= 0.001
Max Subgrid Regions= 1
Max Subgrid Length Scale= 3.402823E+38
Initial Layer Thickness= 3.402823E+38
Min Layer Thickness= 3.402823E+38
Max Layer Thickness= 3.402823E+38
Number of Layers= 5

--- SFFSHGCK.f01 (steady flow) ---

Flow Title=Flow
Program Version=6.31
Number of Profiles= 1
Profile Names=F01pct
River Rch & RM=SFFSHGCK,Main,102956
     665
River Rch & RM=SFFSHGCK,Main,99491
     782
River Rch & RM=SFFSHGCK,Main,96497
    1130
River Rch & RM=SFFSHGCK,Main,93520
    1520
River Rch & RM=SFFSHGCK,Main,90892
    2060
River Rch & RM=SFFSHGCK,Main,89019
    2340
River Rch & RM=SFFSHGCK,Main,81515
    2610
River Rch & RM=SFFSHGCK,Main,76512
    3100
River Rch & RM=SFFSHGCK,Main,74077
    4990
River Rch & RM=SFFSHGCK,Main,69012
    5560
River Rch & RM=SFFSHGCK,Main,63512
    7290
River Rch & RM=SFFSHGCK,Main,37019
    8100
River Rch & RM=SFFSHGCK,Main,31507
    9880
River Rch & RM=SFFSHGCK,Main,0
   13900
Boundary for River Rch & Prof#=SFFSHGCK,Main            , 1
Up Type= 0
Dn Type= 1
Dn Known WS=709.1
DSS Import GetInterval= 0
DSS Import GetPeak= 0
DSS Import FillOption= 0

--- SFFSHGCK.g01 (geometry) ---

Geom Title=Geometry
Program Version=6.31

River Reach=SFFSHGCK        ,Main
Reach XY= 30
 1679455.5628478346970.8887390721681759.46899958352297.199001117
1681075.15499958354387.8190011211675667.14899959358497.960001127
1674172.53899958358649.4030011271673571.16199959362325.092001092
1669617.45599957363500.5570010881667856.08899961365900.897001115
1668079.75499958367944.9290011071663029.69899957368590.764001088
1661550.48099961367281.2920011271660834.19099958370070.548001103
1658387.30099959 369257.06400113 1657382.9719996372001.678001094
1653547.32999958371853.3690011231655162.34699958373798.326001126
1654980.69599958375047.7270011181651366.88499959373467.515001147
 1650533.9509996374055.2950011141651752.16675917 375170.27925249
 1651341.8709996376800.1740011481649154.31199958 375609.47700115
1646864.02099959376173.073001099 1646107.7399996378533.899001096
 1641420.4139996  378174.1830011 1643685.5539996381754.693001091
1638949.39799959380706.1380010981638989.27299958385404.278001115
 1636093.2639996384986.5080011531636487.10255393390101.973639943

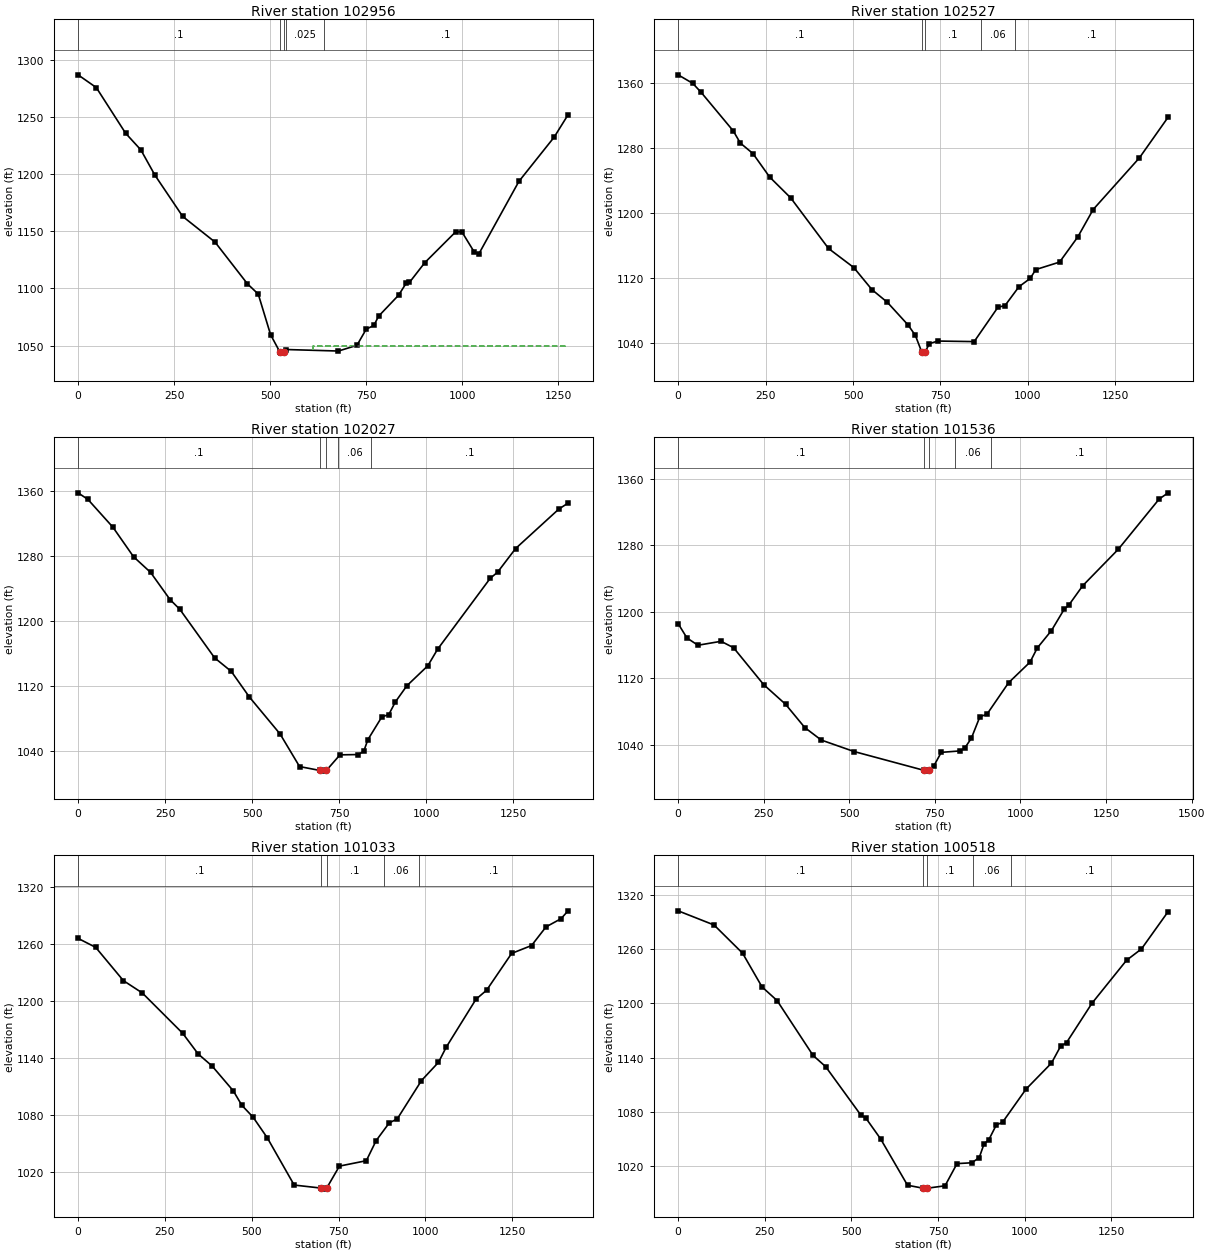
Type RM Length L Ch R = 1 ,102956  ,428.2,428.5,428.6
XS GIS Cut Line= 2
 1678928.7457059347037.3363149911680199.57121069 346934.25073548
#Sta/Elev= 30
       0 1286.79    47.5 1275.65   123.8 1235.71   163.5 1221.13     200 1199.07
   272.3 1162.99   356.5 1140.53   440.8 1104.04   468.9 1095.08     501 1059.57
  525.311044.342   529.1 1043.47  534.981044.342     540 1046.64   677.6  1045.3
   725.7 1050.31   749.8 1064.41   769.9 1067.72   781.9 1075.74   834.1 1094.14
   854.2 1104.84   862.2 1105.24   902.3 1122.59   982.6 1149.52   998.6 1149.57
  1030.7 1131.98  1042.8  1130.2  1147.1 1193.63  1238.8  1232.3    1275 1251.87
#Mann= 5 ,-1,0
       0      .1       0  525.31    .045       0  534.98      .1       0
     540    .025       0     640      .1       0
#XS Ineff= 2 , 0
                          612.19         1049.85
Permanent Ineff=
       F       F
Bank Sta=525.31,534.98
XS Rating Curve= 0 ,0
Exp/Cntr(USF)=0,0
Exp/Cntr=0.3,0.1

Type RM Length L Ch R = 1 ,102527  ,499.9,500,499.8
XS GIS Cut Line= 6
1678798.47232334347446.8674124181678997.14876325347439.105945006
1679192.31241493347431.4832568321679623.23379718347414.650613338
1680098.65246576347396.0788000821680198.18605934347392.191668749
#Sta/Elev= 30
       0 1370.04    41.7 1359.56    65.7 1348.52   157.8 1300.89   177.8 1286.05
   213.8 1273.14   261.7  1244.2   321.9 1218.52     430 1156.26     502 1132.85
   554.1 1105.58   598.1 1090.02   657.5 1062.01   678.2 1049.25  696.791028.417
   702.2 1027.44  705.541028.417   718.2 1039.08   742.2 1042.31   846.3 1041.62
   914.3 1083.97   934.4 1085.95   974.4 1109.21  1006.4 1119.38  1022.4 1130.29
  1090.5 1139.52  1142.5 1170.47  1186.5 1204.25  1318.6  1267.8  1400.8 1317.95
#Mann= 5 ,-1,0
       0      .1       0  696.79    .045       0  705.54      .1       0
  865.39     .06       0  962.89      .1       0
Bank Sta=696.79,705.54
XS Rating Curve= 0 ,0
Exp/Cntr(USF)=0,0
Exp/Cntr=0.3,0.1

Type RM Length L Ch R = 1 ,102027  ,490.4,491.6,488.2
XS GIS Cut Line= 6
1678819.86434092347930.2421018331678920.56919201347928.303457424
1679219.50100884347924.8575981711679314.57890268 347923.17453067
1679402.05510567347920.2828041761680226.61316784347883.220214263
#Sta/Elev= 30
       0 1357.71    28.3 1349.65   100.3  1315.4   159.4 1279.21   208.3 1260.01
   264.3 1226.55   292.3 1214.66   392.3 1154.98   440.3 1138.29   492.3 1106.81
   580.4 1061.46   636.4 1021.42  694.27 1016.69   704.5 1015.82  713.421016.692
   752.5 1035.83   804.6 1036.16   820.6 1040.03   832.6 1054.44   872.6 1082.36
   892.7 1085.35   911.7 1100.92   944.7 1120.73  1004.8 1145.23  1032.8 1165.51
  1184.2 1252.77    1205  1260.1    1257 1289.26    1381 1337.68  1407.7 1345.11
#Mann= 5 ,-1,0
       0      .1       0  694.27    .045       0  713.42      .1       0
  747.29     .06       0  842.29      .1       0
Bank Sta=694.27,713.42
XS Rating Curve= 0 ,0
Exp/Cntr(USF)=0,0
Exp/Cntr=0.3,0.1

Type RM Length L Ch R = 1 ,101536  ,498.4,502.1,499.5
XS GIS Cut Line= 6
1678862.28420359348395.4839535061678962.92278184348392.611912012
1679358.46562593348399.4504810121679532.55714126348394.119126841
1679785.21378817348297.3391366751680257.31520617348166.245238751
#Sta/Elev= 30
       0 1185.83    25.8 1168.57    57.9 1159.83   125.4 1164.57   161.9 1156.86
   249.9 1112.48   313.9 1088.83   369.9 1060.89   417.9 1045.88   513.9 1032.04
  718.761009.351   725.2 1008.48  732.761009.352   746.4 1014.33   768.6 1031.05
   824.5 1032.82   837.7 1036.53   856.4 1047.94   881.5 1073.95     902 1076.83
   965.3 1114.78    1028 1139.59  1048.9 1156.46  1090.5  1177.5  1127.9 1203.31
  1140.4 1207.63  1181.8  1231.4  1285.4  1275.1  1405.3 1335.71  1431.3 1343.08
#Mann= 5 ,-1,0
       0      .1       0  718.76    .045       0  732.76      .1       0
  807.49     .06       0  913.15      .1       0
Bank Sta=718.76,732.76
XS Rating Curve= 0 ,0
Exp/Cntr(USF)=0,0
Exp/Cntr=0.3,0.1

Type RM Length L Ch R = 1 ,101033  ,514.8,515.5,512.7
XS GIS Cut Line= 2
 1678993.1182595348950.0842222571680378.41043642348684.767823756
#Sta/Elev= 30
       0 1266.12    50.8 1256.63   130.4  1221.6     185 1208.56   301.3 1166.03
   345.7  1144.3   385.9 1131.57     447 1105.34   471.4 1090.22     504 1077.58
   544.7 1055.93   622.1 1006.12     7001002.901   707.6 1001.83   715.71002.902
   752.4 1026.09   829.8 1031.79   858.2 1053.04     896 1071.71   918.7 1075.77
   988.6 1116.28  1037.5 1135.47  1059.7 1151.37  1145.5 1201.97    1176 1211.45
  1248.1 1250.26  1305.4 1258.56    1347 1278.19  1390.4 1286.87  1410.5 1295.13
#Mann= 5 ,-1,0
       0      .1       0     700    .045       0   715.7      .1       0
     880     .06       0     980      .1       0
Bank Sta=700,715.7
XS Rating Curve= 0 ,0
Exp/Cntr(USF)=0,0
Exp/Cntr=0.3,0.1

Type RM Length L Ch R = 1 ,100518  ,565.6,568.6,564.6
XS GIS Cut Line= 2
1679172.24519785349542.6315935851680479.25209826349004.254061416
#Sta/Elev= 30
       0 1302.14   103.7 1286.48   185.9 1255.35   242.1 1218.05   285.4 1203.04
   389.2 1142.44   425.6    1130   527.6 1076.24   540.8 1073.58   583.9 1050.33
   661.7  999.02  706.83995.7148   713.7  994.72  718.33995.7167   769.9   998.4
   804.5 1022.91   847.2 1023.83   868.6 1029.56   882.4 1044.61   896.2 1049.27
   917.6 1065.44     936 1068.68  1003.5 1105.16    1077 1133.97    1103 1152.38
  1120.3  1156.5  1193.9 1200.11  1293.4 1247.48  1336.6 1260.07  1413.5  1301.3
#Mann= 5 ,-1,0
       0      .1       0  706.83    .045       0  718.33      .1       0
     850     .06       0     960      .1       0
Bank Sta=706.83,718.33
XS Rating Curve= 0 ,0
Exp/Cntr(USF)=0,0
Exp/Cntr=0.3,0.1

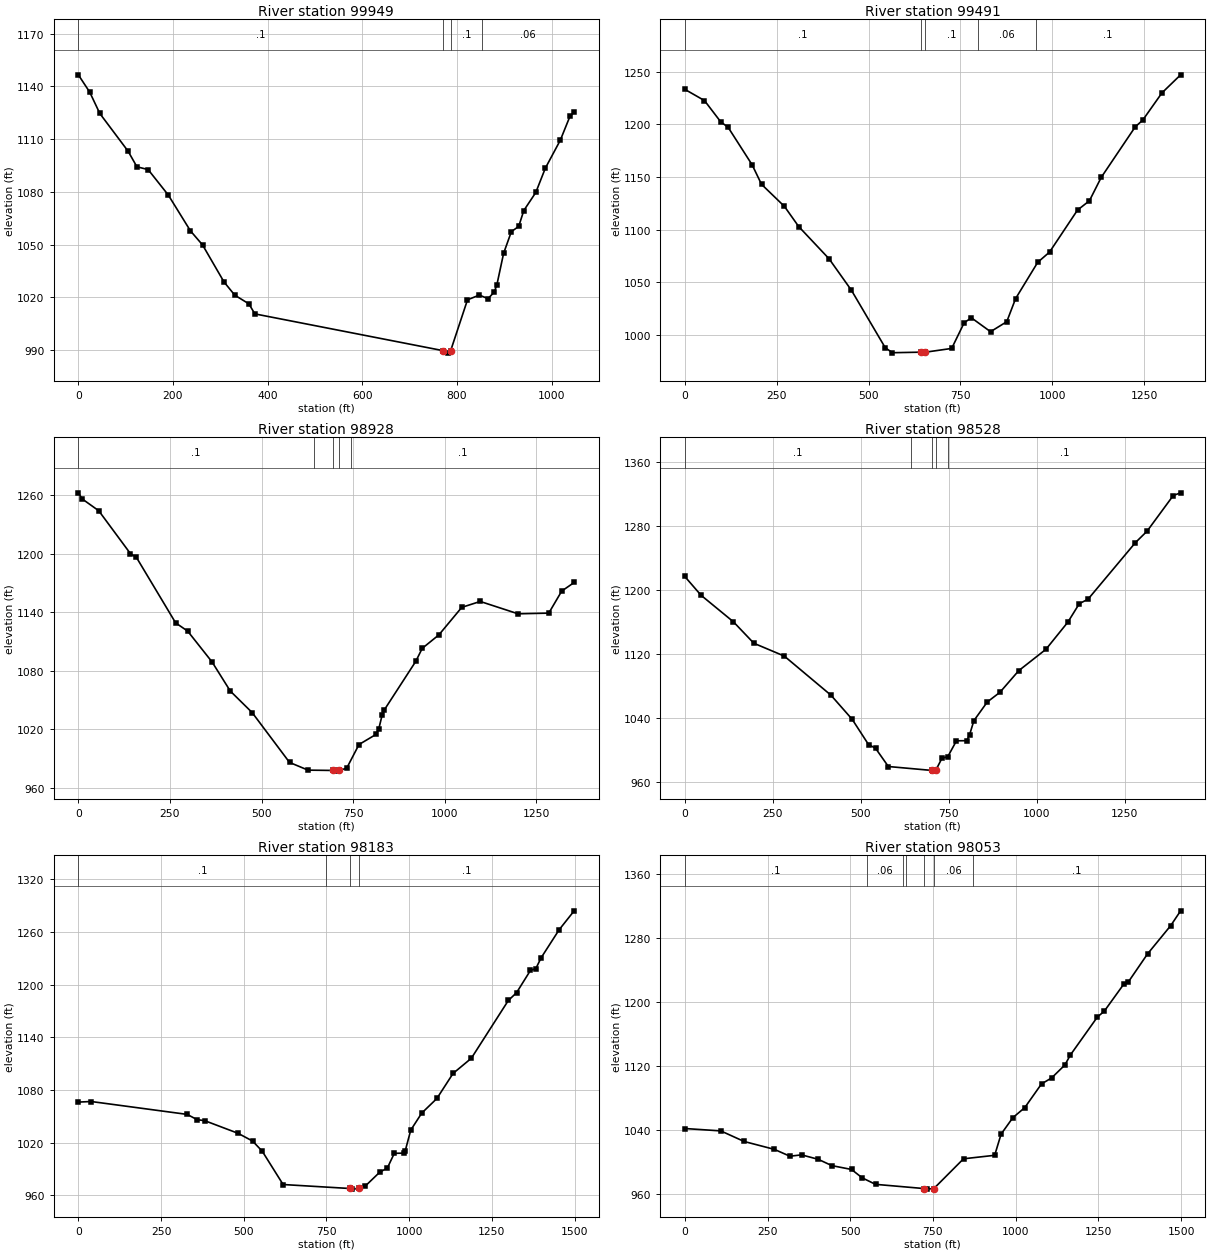
Type RM Length L Ch R = 1 ,99949   ,455.2,458.6,457.7
XS GIS Cut Line= 3
1679425.45891246349808.5528285141679794.53336529349942.747737942
1680303.12140043349529.818963743
#Sta/Elev= 30
       0 1146.55    24.1 1136.69    45.4 1124.55   105.1 1103.12   123.8 1094.22
   147.5 1092.64   190.1 1078.16   236.9 1057.78   262.5 1049.77   307.9 1028.68
   330.6 1021.19   360.3 1016.27   373.1 1010.53  771.11989.6013   781.2  988.21
  786.82 989.599   822.4 1018.54   847.5 1021.25   865.8 1019.17   879.1 1023.05
   884.5  1027.1   898.7 1044.99   915.1 1057.34   930.6  1060.3   941.4 1069.35
   966.7  1079.6   986.9 1093.44  1018.5 1109.33  1038.8 1122.86  1047.8 1125.33
#Mann= 4 ,-1,0
       0      .1       0  771.11    .045       0  786.82      .1       0
  852.71     .06       0
Bank Sta=771.11,786.82
XS Rating Curve= 0 ,0
Exp/Cntr(USF)=0,0
Exp/Cntr=0.3,0.1

Type RM Length L Ch R = 1 ,99491   ,558,563.3,563.7
XS GIS Cut Line= 5
1679816.28495704350438.4817623941680139.69812744350173.762950929
1680464.58942135349945.9456693211680485.84231605349677.665428607
1680520.33027533349414.291057472
#Sta/Elev= 30
       0 1233.25    53.6 1222.56    97.9 1202.34   117.8 1197.25   183.2 1161.64
   208.8 1143.11   271.3  1122.1   309.9 1103.07   392.6 1072.45   453.6  1042.5
   545.5  988.06     565  983.29     643  983.81   648.9   982.9  654.95983.7998
   726.4  987.36   760.4 1011.76     780 1016.42   832.2 1003.24   876.3 1012.73
   900.4 1034.69   960.6  1069.1   992.7 1078.78  1068.9 1118.68  1101.2 1127.45
  1133.4 1149.68    1226 1197.64  1246.4 1204.04  1298.8 1229.91  1349.5 1247.01
#Mann= 5 ,-1,0
       0      .1       0     643    .045       0  654.95      .1       0
  797.94     .06       0  954.74      .1       0
Bank Sta=643,654.95
XS Rating Curve= 0 ,0
Exp/Cntr(USF)=0,0
Exp/Cntr=0.3,0.1

Type RM Length L Ch R = 1 ,98928   ,394.5,400,398.2
XS GIS Cut Line= 5
1679929.92415934 350642.70470121 1680390.4914203 350531.86242642
1680828.40945649350387.4188866281680912.69818492350365.277427282
1681223.98888054350251.434941019
#Sta/Elev= 30
       0 1262.24    10.5    1256    55.7 1243.89   142.1 1200.03   158.6  1196.1
   265.6 1129.08   298.5 1120.61   365.1 1089.02   414.8 1059.25   474.5 1037.21
   576.5  986.17   627.1  978.27  694.33  977.96   702.5  977.26   711.3  977.98
   732.4  980.18   766.1  1004.5   812.4 1014.83   819.7 1019.94   829.2 1034.54
   835.5 1040.13   921.1 1089.68   938.7 1102.99   984.2  1116.8  1046.6 1144.95
    1097 1151.01  1200.3 1138.35  1284.1 1139.05  1319.5 1161.66  1353.4 1170.42
#Mann= 5 ,-1,0
       0      .1       0  643.72     .06       0  694.33    .045       0
   711.3     .06       0  743.72      .1       0
Bank Sta=694.33,711.3
XS Rating Curve= 0 ,0
Exp/Cntr(USF)=0,0
Exp/Cntr=0.3,0.1

Type RM Length L Ch R = 1 ,98528   ,355,344.9,327.7
BEGIN DESCRIPTION:
Structure 31 XS 4
END DESCRIPTION:
XS GIS Cut Line= 6
1680024.10996392350955.2682040041680220.13188159350896.942205176
  1680588.266644350811.8068767491680916.04485984350731.089518502
1681102.38471025 350689.578774751681393.61936401 350628.11826776
#Sta/Elev= 30
       0 1216.65    46.1 1193.21     138 1160.02   196.2 1133.14   282.5 1117.15
   415.1 1068.23   475.4 1038.06   521.9 1006.49   541.8 1001.82   578.3  978.98
  701.32974.1061   705.8  973.22  712.72974.1076   730.5  989.31   747.2   991.4
   771.7 1011.15   800.6 1011.29   808.8 1018.37   821.2 1036.35   859.3  1059.7
   895.3 1071.84   948.7  1098.9  1025.9 1125.59  1088.1 1159.53  1120.8 1182.75
  1145.3 1188.16  1280.2 1259.09  1313.1 1273.31  1387.6 1317.95  1408.5  1321.3
#Mann= 5 ,-1,0
       0      .1       0  642.38     .06       0  701.32    .045       0
  712.72     .06       0  747.37      .1       0
Bank Sta=701.32,712.72
XS Rating Curve= 0 ,0
Exp/Cntr(USF)=0,0
Exp/Cntr=0.3,0.1

Type RM Length L Ch R = 1 ,98183   ,137,129.9,135
BEGIN DESCRIPTION:
Structure 31 XS 3
END DESCRIPTION:
XS GIS Cut Line= 6
1680206.26375606 351592.439794381680782.22155433351272.295206127
 1680801.5849059 351225.500439841680809.65296905351123.842844114
1680808.03935642351001.2082841911681351.77036808350849.232830062
#Sta/Elev= 30
       0 1066.22    38.7 1066.89   329.1 1052.22   359.1 1046.21     382 1045.09
   482.6 1030.73   526.7 1021.89   555.9 1010.32     619   972.4  820.49967.8804
   826.9  967.16  847.57967.8809   866.1  970.18   910.9  986.36   934.2  991.24
   955.1 1007.92   984.1 1008.13   988.3 1010.98  1004.9 1034.36  1038.1 1053.71
  1083.8 1070.32  1132.8 1098.87    1188 1116.12  1299.8 1181.88  1324.7 1190.76
  1366.5 1216.01  1382.9 1218.17    1399 1230.53  1453.5 1262.45  1498.8 1283.93
#Mann= 4 ,-1,0
       0      .1       0   749.6     .06       0  820.49    .045       0
  847.57      .1       0
Bank Sta=820.49,847.57
XS Rating Curve= 0 ,0
Exp/Cntr(USF)=0,0
Exp/Cntr=0.3,0.1

Type RM Length L Ch R = 1 ,98053   ,509,525.3,533.9
BEGIN DESCRIPTION:
Structure 31 XS 2
END DESCRIPTION:
XS GIS Cut Line= 6
1680267.60376902351620.0479193721680843.56156729351299.903331119
1680862.92491886351253.1085648321680870.99298201351151.450969106
1680869.37936938351028.8164091831681413.11038104350876.840955054
#Sta/Elev= 30
       0 1041.86   108.8 1038.88   179.4 1025.64   270.6 1015.82   317.7 1007.24
     353 1008.92   403.3 1003.37   444.5  995.48     504  990.68     536  980.26
   576.5  972.08  722.18966.8469   730.7   966.1  752.91966.8472   842.5 1004.01
   936.7 1008.37   956.1 1034.85   991.8 1055.49  1027.6 1067.93  1078.3 1097.63
  1108.7 1105.03  1148.9 1121.23  1165.5 1133.72  1247.3 1181.26  1267.8 1188.38
  1327.5  1222.6  1339.9 1224.54  1398.9 1260.14  1468.7 1295.37  1498.8 1313.93
#Mann= 7 ,-1,0
       0      .1       0     550     .06       0  658.95     .05       0
  668.95     .06       0  722.18    .045       0  752.91     .06       0
  871.57      .1       0
Bank Sta=722.18,752.91
XS Rating Curve= 0 ,0
Exp/Cntr(USF)=0,0
Exp/Cntr=0.3,0.1

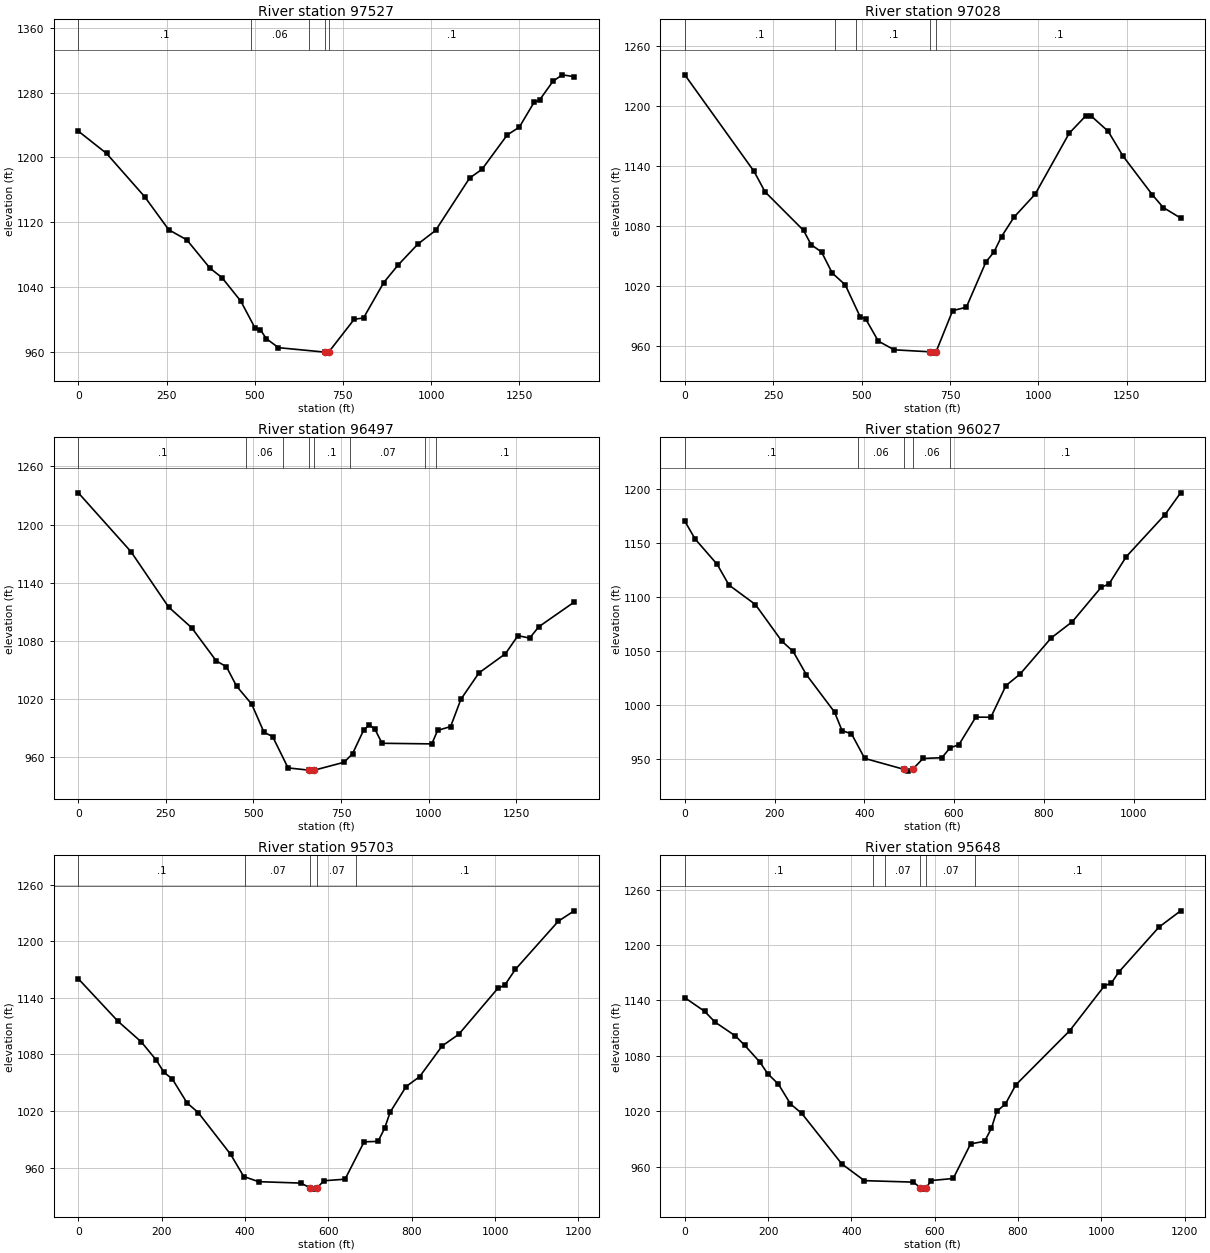
Type RM Length L Ch R = 1 ,97527   ,498.7,499.8,498.2
BEGIN DESCRIPTION:
Structure 31 XS 1
END DESCRIPTION:
XS GIS Cut Line= 6
1680593.59340501352085.906690761  1681108.167179351683.164386004
1681254.37915692351586.9854445011681324.20742933 351533.91173175
1681470.89972125351411.082909167 1681693.2312976351212.639736503
#Sta/Elev= 30
       0 1232.43      80 1204.94   187.9 1151.72   256.3 1110.95   307.6 1098.47
   373.1 1063.67   407.3 1051.94   460.6 1023.01   501.4  989.51   515.6  988.06
   532.7   976.9   567.3  965.72  700.24960.1808   705.8     959  709.52960.1795
     782  1000.7   808.4 1002.34   865.7  1045.9     906 1067.29   962.6 1093.36
  1012.8 1110.17  1109.1 1174.63  1144.2 1185.39  1215.8 1227.73    1250 1237.33
  1291.8 1267.85  1307.4  1270.7  1345.3 1293.78  1371.8 1301.78  1405.5 1299.53
#Mann= 5 ,-1,0
       0      .1       0  489.72     .06       0  653.44      .1       0
  700.24    .045       0  709.52      .1       0
Bank Sta=700.24,709.52
XS Rating Curve= 0 ,0
Exp/Cntr(USF)=0,0
Exp/Cntr=0.3,0.1

Type RM Length L Ch R = 1 ,97028   ,525.5,530.7,534.3
XS GIS Cut Line= 6
1680983.34131317352464.7687939261681123.96931276352323.416714415
 1681267.8459935352190.9898139241681338.54729567352129.312443838
1681601.07629818351917.1944297551682039.83624743351544.519978255
#Sta/Elev= 30
       0 1231.58   195.9 1134.99   226.9 1114.59   335.9 1075.98   357.2 1061.76
   386.7 1054.45   416.7 1033.49   453.7 1021.59   495.9  989.64   511.4  987.55
   547.1  965.39   591.8  956.66  694.71954.6101   706.1  953.33  710.47954.6121
   757.3  995.76   796.1  999.24   851.6 1044.57   874.3 1054.46   895.6 1069.91
   931.1 1089.35   990.7 1112.26  1086.9 1173.16  1134.1 1190.68  1149.9 1190.12
  1197.1 1175.15  1239.1 1150.34  1322.2 1111.55  1352.9 1098.91    1402 1088.42
#Mann= 5 ,-1,0
       0      .1       0  424.94     .06       0  484.94      .1       0
  694.71    .045       0  710.47      .1       0
Bank Sta=694.71,710.47
XS Rating Curve= 0 ,0
Exp/Cntr(USF)=0,0
Exp/Cntr=0.3,0.1

Type RM Length L Ch R = 1 ,96497   ,466.2,469.8,472.2
XS GIS Cut Line= 5
 1681066.3480164352564.1378033531681604.34102363352428.005391764
 1681959.6255991352410.291022524 1682295.4614203352646.712646397
1682374.39468937 352698.23538619
#Sta/Elev= 30
       0 1232.76   150.4 1172.01   257.6 1114.97   323.7 1093.55   393.8 1059.37
   422.7 1053.39   451.6 1033.45   495.1 1014.69     530  985.74   554.7  981.32
   598.8  948.98  659.21946.6235   666.9  945.66  673.48946.6246     759  954.84
   782.9  963.66     815  988.28   831.1  993.44   847.1  988.67   867.1  974.39
  1009.1  973.76  1025.8  987.68  1062.9  991.63  1092.3 1019.84  1143.9 1047.02
  1219.5  1066.8  1255.1 1085.44  1288.7 1082.89  1314.5 1094.56  1415.6 1120.01
#Mann= 8 ,-1,0
       0      .1       0     480     .06       0  584.95      .1       0
  659.21    .045       0  673.48      .1       0  774.95     .07       0
  990.68     .06       0 1020.68      .1       0
Bank Sta=659.21,673.48
XS Rating Curve= 0 ,0
Exp/Cntr(USF)=0,0
Exp/Cntr=0.3,0.1

Type RM Length L Ch R = 1 ,96027   ,324.5,324.4,324.3
BEGIN DESCRIPTION:
Structure 30 XS 4
END DESCRIPTION:
XS GIS Cut Line= 6
1681166.09750934352719.9313413351681846.54693584352936.435173422
1681935.83940817352965.8137235941682027.27656126 352999.88419351
1682119.72125825353036.211548671 1682212.5015845353073.630437091
#Sta/Elev= 30
       0 1170.28    23.1 1153.75    72.1 1130.39    98.4 1111.24   157.4 1093.19
   216.2 1059.39   241.4 1049.91   270.8 1028.44   333.7   993.8   350.5   976.6
   371.5  973.72   400.9  950.97  488.51 940.855   497.4   939.2  507.63 940.856
     531   950.9     573  951.63   591.2  960.72   610.8  963.59   648.5  989.13
   682.1  989.01   715.7 1018.27   747.1 1028.87   816.6 1062.34   863.8  1077.4
     928 1109.22   945.2 1112.11   983.8 1137.43  1070.1 1176.28    1105 1196.48
#Mann= 5 ,-1,0
       0      .1       0  386.56     .06       0  488.51    .045       0
  507.63     .06       0  591.56      .1       0
Bank Sta=488.51,507.63
XS Rating Curve= 0 ,0
Exp/Cntr(USF)=0,0
Exp/Cntr=0.3,0.1

Type RM Length L Ch R = 1 ,95703   ,54.4,54.6,54.6
BEGIN DESCRIPTION:
Structure 30 XS 3
END DESCRIPTION:
XS GIS Cut Line= 6
1681082.51322091352873.5499765831681457.08053561353071.984762636
1681462.03143399353113.2694370821681475.53460043353145.339457375
1681504.22882912353166.7194709031682132.53174888353346.562084248
#Sta/Elev= 30
       0 1160.25    95.1 1115.22   151.3 1093.19   186.9 1074.05   205.5 1060.96
   225.3 1054.12   260.8 1028.58   287.5  1018.4   365.3  974.09   396.9  950.48
   432.5  945.05   534.4  943.52  556.93938.1768     565  937.13  572.16938.1774
   589.2  946.01   639.9  947.66   685.7  987.32     719  987.75   734.7  1001.5
   748.1 1018.74   786.5 1045.99   818.8 1056.43   872.9 1089.03   912.7 1101.35
  1006.5 1150.13  1022.9  1153.4  1048.5  1170.2  1151.7 1221.37  1189.6 1232.36
#Mann= 5 ,-1,0
       0      .1       0     400     .07       0  556.93    .045       0
  572.16     .07       0  666.04      .1       0
Bank Sta=556.93,572.16
XS Rating Curve= 0 ,0
Exp/Cntr(USF)=0,0
Exp/Cntr=0.3,0.1

Type RM Length L Ch R = 1 ,95648   ,150.1,150.1,149.2
BEGIN DESCRIPTION:
Structure 30 XS 2
END DESCRIPTION:
XS GIS Cut Line= 6
1681073.86297026 352905.665097211681395.26101785353082.451678196
1681399.27940751353126.7931844791681425.86314472353179.960658899
1681479.88815905353215.9773351191682107.43110796353402.142074856
#Sta/Elev= 30
       0 1143.04    47.5 1128.32    72.4  1116.7   121.3 1101.74   144.1 1091.39
   180.6 1073.17   198.9 1060.87   224.7 1049.55   253.7 1028.11   280.6 1017.99
   376.9  963.27   431.1  945.16   548.5  943.57  565.35937.6013   573.5  935.99
  580.04937.6047     591  945.25   644.4  947.49   686.1  984.89   719.8  987.76
   736.2 1001.86   748.7  1020.1   769.6 1027.96   794.6 1048.72     924  1107.3
  1007.4 1155.89  1024.1 1158.84  1041.5 1170.56  1138.1 1219.28  1190.3 1236.98
#Mann= 6 ,-1,0
       0      .1       0  451.33     .06       0  480.78     .07       0
  565.35    .045       0  580.04     .07       0  695.71      .1       0
Bank Sta=565.35,580.04
XS Rating Curve= 0 ,0
Exp/Cntr(USF)=0,0
Exp/Cntr=0.3,0.1

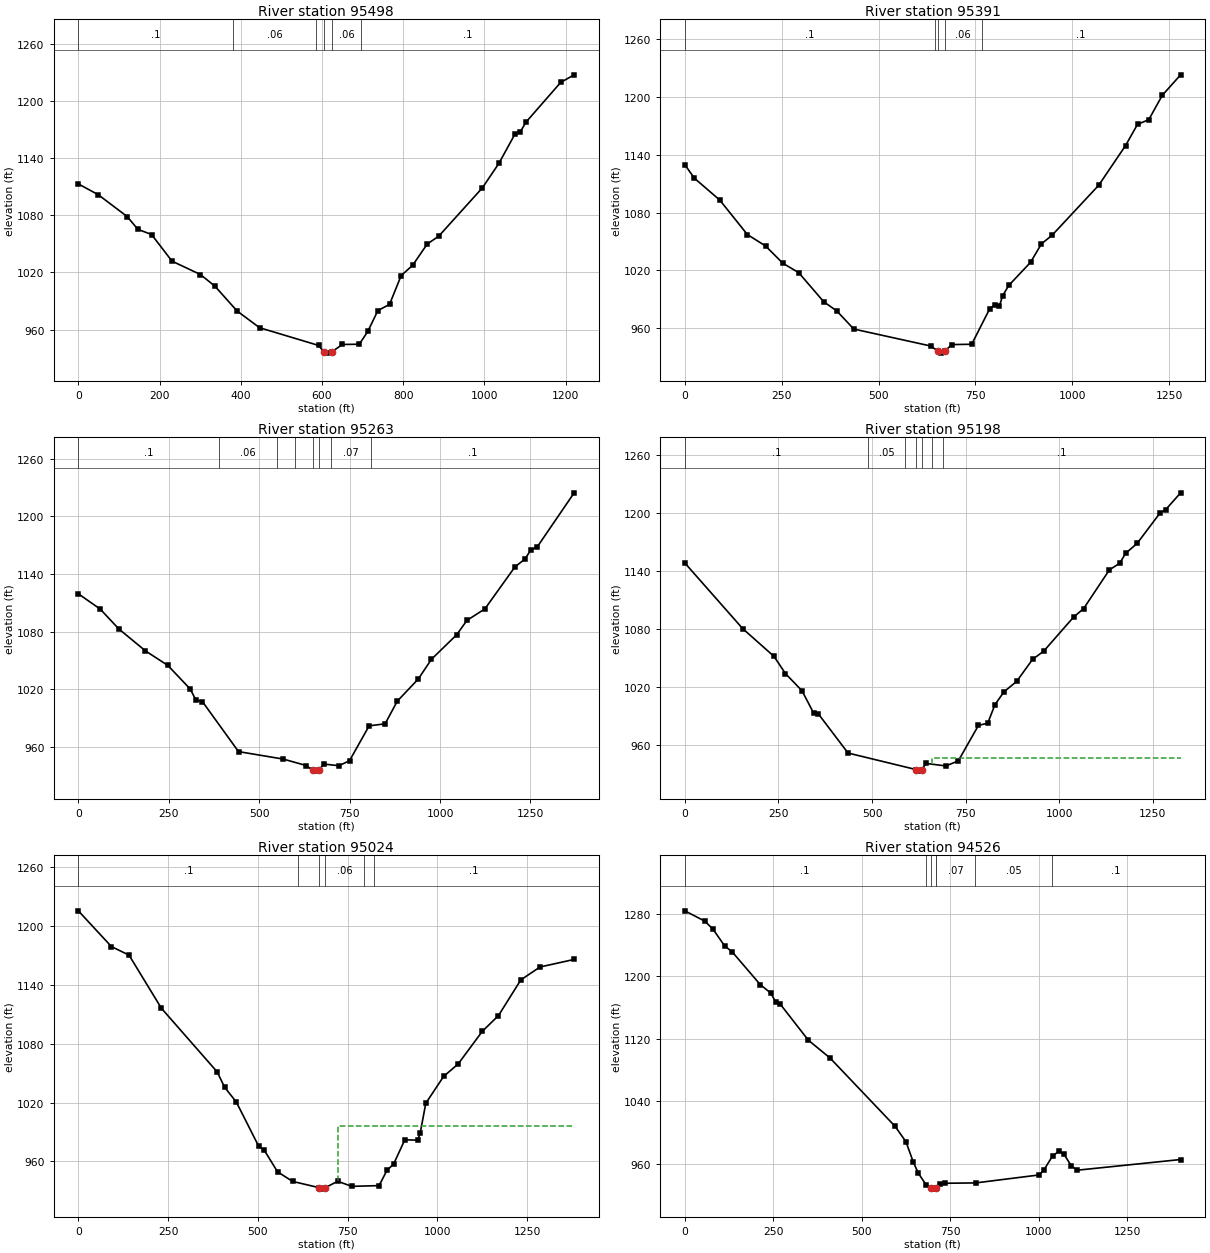
Type RM Length L Ch R = 1 ,95498   ,106.2,106.7,106.7
BEGIN DESCRIPTION:
Structure 30 XS 1
END DESCRIPTION:
XS GIS Cut Line= 4
1680918.73647011353079.4195487421681286.28156929353314.289831636
1681612.58990125353407.5207836251682057.22982612353432.621424545
#Sta/Elev= 30
       0 1113.03    49.1 1101.67   120.3 1078.72   146.6 1065.34   180.4 1059.85
   230.6 1031.91   300.7 1017.85   336.4 1005.58   390.9  979.56   446.4  961.96
     592  943.33  604.48936.5851   612.8   935.3  623.92936.5867   650.2  944.39
   691.9  944.66   712.7  958.04   737.6  980.01   766.3  986.48     795  1016.8
   823.1 1027.49   859.2 1049.97   887.2 1058.01   994.8 1108.83  1035.5 1134.55
  1075.5 1165.64  1087.6 1167.17  1102.2 1177.86  1187.7  1219.6  1220.9 1227.59
#Mann= 6 ,-1,0
       0      .1       0     380     .06       0  586.18      .1       0
  604.48    .045       0  623.92     .06       0  696.18      .1       0
Bank Sta=604.48,623.92
XS Rating Curve= 0 ,0
Exp/Cntr(USF)=0,0
Exp/Cntr=0.3,0.1

Type RM Length L Ch R = 1 ,95391   ,128.4,128.1,127.8
BEGIN DESCRIPTION:
Structure 29 XS 4
END DESCRIPTION:
XS GIS Cut Line= 4
1680868.53518827353129.6208305821681214.56545238353394.970463165
1681578.52474572353513.3020560731682039.30079689 353498.95883269
#Sta/Elev= 30
       0 1129.81    24.6 1115.84    90.2 1093.11   161.5 1057.32   208.6 1045.39
   252.8  1027.6     294 1017.74   358.4  987.62   392.6  977.88   436.1  959.21
   635.4  941.53  652.94936.2409   660.6   934.2  670.87936.2419   689.3  943.07
   740.5   943.4   786.8  980.06   799.4  984.18     812  983.17   820.4  993.73
   836.1 1004.45   892.4 1028.42   920.4 1047.58   948.4 1056.72  1068.5 1108.53
  1137.7 1149.71  1168.5 1171.69  1197.5 1176.52  1232.6 1201.93  1279.8 1223.11
#Mann= 5 ,-1,0
       0      .1       0  646.06     .05       0  652.94    .045       0
  670.87     .06       0  766.06      .1       0
Bank Sta=652.94,670.87
XS Rating Curve= 0 ,0
Exp/Cntr(USF)=0,0
Exp/Cntr=0.3,0.1

Type RM Length L Ch R = 1 ,95263   ,65,64.9,64.6
BEGIN DESCRIPTION:
Structure 29 XS 3
END DESCRIPTION:
XS GIS Cut Line= 5
1680795.02616843353739.2078243531681178.70739392353529.438182379
1681248.63060791353545.5743086851681555.21700772353633.426551904
1681998.06402967353947.184563404
#Sta/Elev= 30
       0 1119.35    60.5 1103.42   111.8 1082.76   185.5 1059.85   247.4 1044.67
   309.3 1020.06   324.9 1008.66   343.1  1006.9   442.8   954.8   566.8  946.97
   630.7   940.2   647.5935.2452   653.3  934.43  664.01935.2473   679.1  941.77
   720.7   940.1   749.8  945.35   803.9  981.65   848.1  983.78   881.8 1007.43
   939.9 1030.54   976.1 1051.03    1046 1076.67  1074.2  1091.6    1124 1103.65
    1207  1147.4  1234.7 1155.61  1250.7 1164.91  1269.3 1168.63  1370.7 1224.65
#Mann= 8 ,-1,0
       0      .1       0     390     .06       0  549.04     .05       0
  599.04     .06       0   647.5    .045       0  664.01     .06       0
  699.04     .07       0  809.04      .1       0
Bank Sta=647.5,664.01
XS Rating Curve= 0 ,0
Exp/Cntr(USF)=0,0
Exp/Cntr=0.3,0.1

Type RM Length L Ch R = 1 ,95198   ,173.3,174.2,174.5
BEGIN DESCRIPTION:
Structure 29 XS 2
END DESCRIPTION:
XS GIS Cut Line= 4
1680791.44036258353789.409106193  1681200.222229353602.947202216
1681548.04539603353694.3852512821681974.75629167353983.042621861
#Sta/Elev= 30
       0 1148.46   154.6 1080.44   238.2  1051.7   268.9 1033.85   312.9 1016.14
   343.7  993.21   356.9  992.02   435.9  951.59  618.39934.3917     627  932.85
  633.43934.3932   643.7  940.88   697.3  938.21   730.4  943.46   784.2  980.21
     809  982.52   828.3  1001.7   852.5 1015.08   886.3 1025.79   928.6 1048.55
   958.7 1057.19  1038.1 1092.31    1065 1101.16    1134 1141.37  1161.6 1148.18
  1176.9 1158.32  1208.1 1168.77  1269.7 1200.51    1284  1203.6  1324.1 1221.09
#Mann= 7 ,-1,0
       0      .1       0   489.3     .05       0   589.3     .06       0
  618.39    .045       0  633.43     .06       0   659.3     .07       0
   689.3      .1       0
#XS Ineff= 2 , 0
                          660.36           946.1
Permanent Ineff=
       F       F
Bank Sta=618.39,633.43
XS Rating Curve= 0 ,0
Exp/Cntr(USF)=0,0
Exp/Cntr=0.3,0.1

Type RM Length L Ch R = 1 ,95024   ,496.4,497.6,496
BEGIN DESCRIPTION:
Structure 29 XS 1
END DESCRIPTION:
XS GIS Cut Line= 6
1680642.03500381353876.5906544921681182.29319977353758.929756504
 1681344.1214315353821.8428514151681491.53747526353894.287916511
1681839.33566417354070.8476027551681931.81251334354109.746475086
#Sta/Elev= 30
       0 1215.68    92.2  1179.2   141.3 1170.44   231.4 1116.24   386.9 1051.26
   407.4 1035.67   440.2 1020.53   502.7  975.23   517.9  971.43   554.9  949.36
   596.9  939.55  670.29  933.22   675.9  931.68   688.3  933.24   722.4  939.69
   761.6  934.52   837.7  935.26   860.1  951.06   878.1  957.14   909.5  982.04
   945.4   981.6   952.4  988.98   967.9 1019.29  1017.7 1046.77  1057.9 1059.33
  1125.3  1092.7  1170.3 1108.74  1232.7 1145.24  1286.1 1158.36  1381.2 1166.08
#Mann= 6 ,-1,0
       0      .1       0  612.92     .06       0  670.29    .045       0
   688.3     .06       0  796.56     .07       0  822.53      .1       0
#XS Ineff= 2 , 0
                          723.65          996.55
Permanent Ineff=
       F       F
Bank Sta=670.29,688.3
XS Rating Curve= 0 ,0
Exp/Cntr(USF)=0,0
Exp/Cntr=0.3,0.1

Type RM Length L Ch R = 1 ,94526   ,497.3,500,503.8
XS GIS Cut Line= 6
 1680489.2255035 353970.693603591681323.44561984354341.430723011
1681409.55863659 354378.50873284  1681498.745138354416.366596758
1681589.46772559354454.6148798321681772.83382867354531.598321676
#Sta/Elev= 30
       0 1283.55    55.7 1270.56    79.3 1260.32   112.6 1238.62   133.9 1231.04
   213.3 1189.08     243  1178.3     257 1166.72   270.3 1163.81     349 1118.04
   410.2 1095.29   594.1  1007.8   624.7  988.23     646   961.6   659.8  947.87
   681.6  932.99  695.32928.3589   700.6  927.44  709.34  928.36     721  933.79
   734.2  934.94   821.8  935.38  1000.7  945.57  1013.8  951.28  1039.8  970.45
  1057.2  975.62  1071.2  972.27  1092.5  956.79  1109.4  951.68  1400.9  965.32
#Mann= 7 ,-1,0
       0      .1       0  680.39     .06       0  695.32    .045       0
  709.34     .06       0  710.39     .07       0  820.39     .05       0
 1036.65      .1       0
Bank Sta=695.32,709.34
XS Rating Curve= 0 ,0
Exp/Cntr(USF)=0,0
Exp/Cntr=0.3,0.1