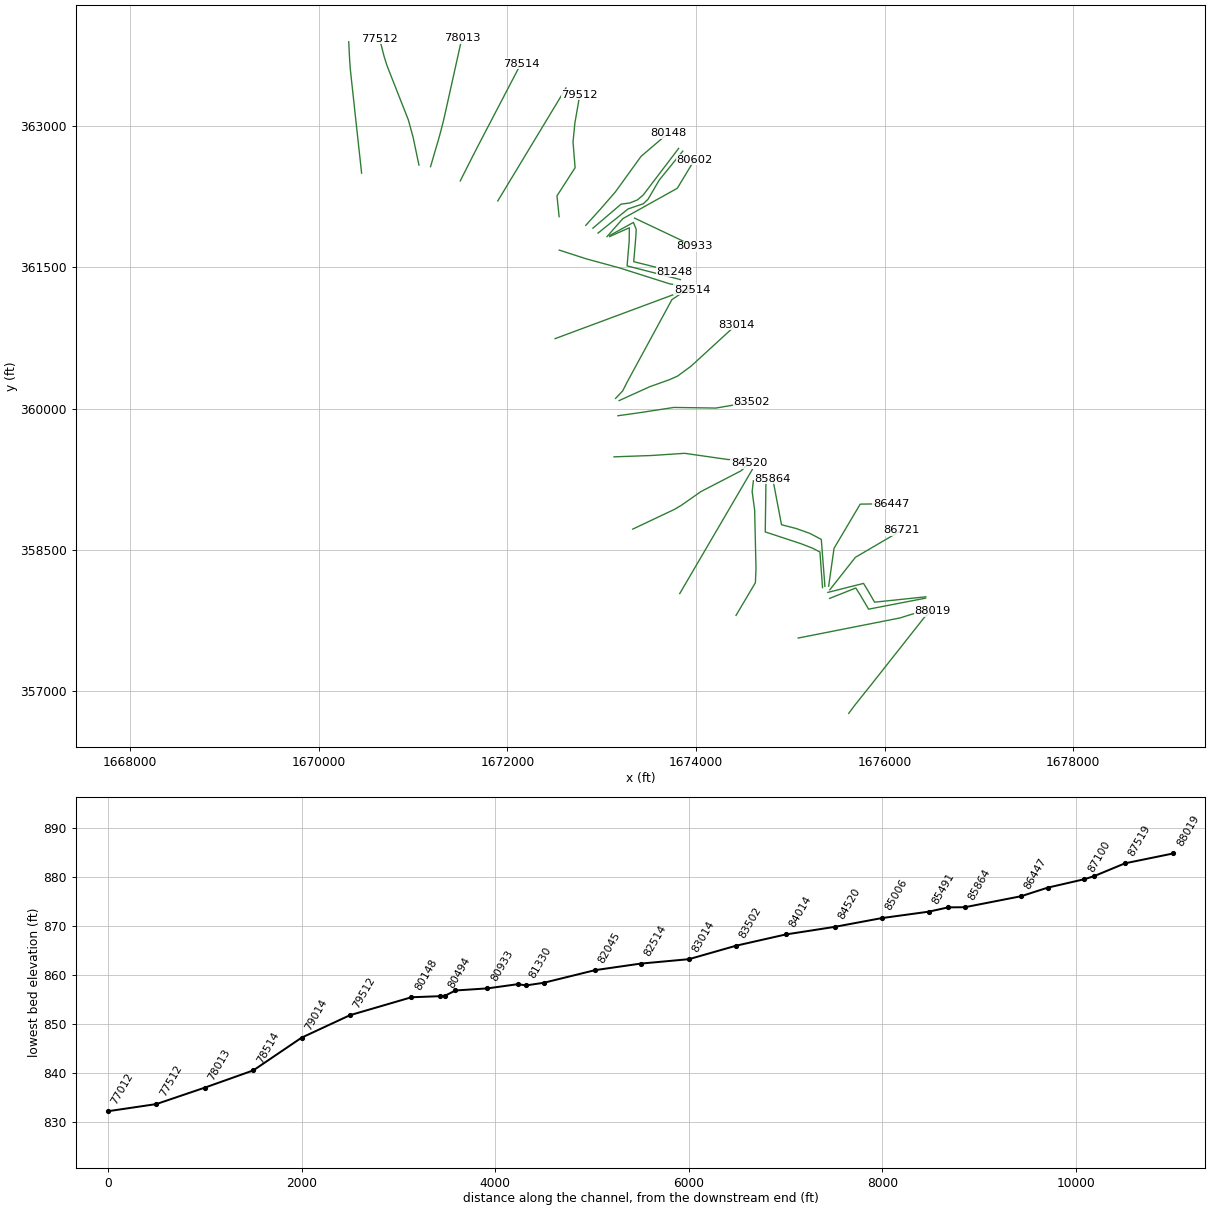
HEC-RAS study SFFSHGCK.prj: SFFSHGCK

--- SFFSHGCK.g01 (geometry) --- (continued)

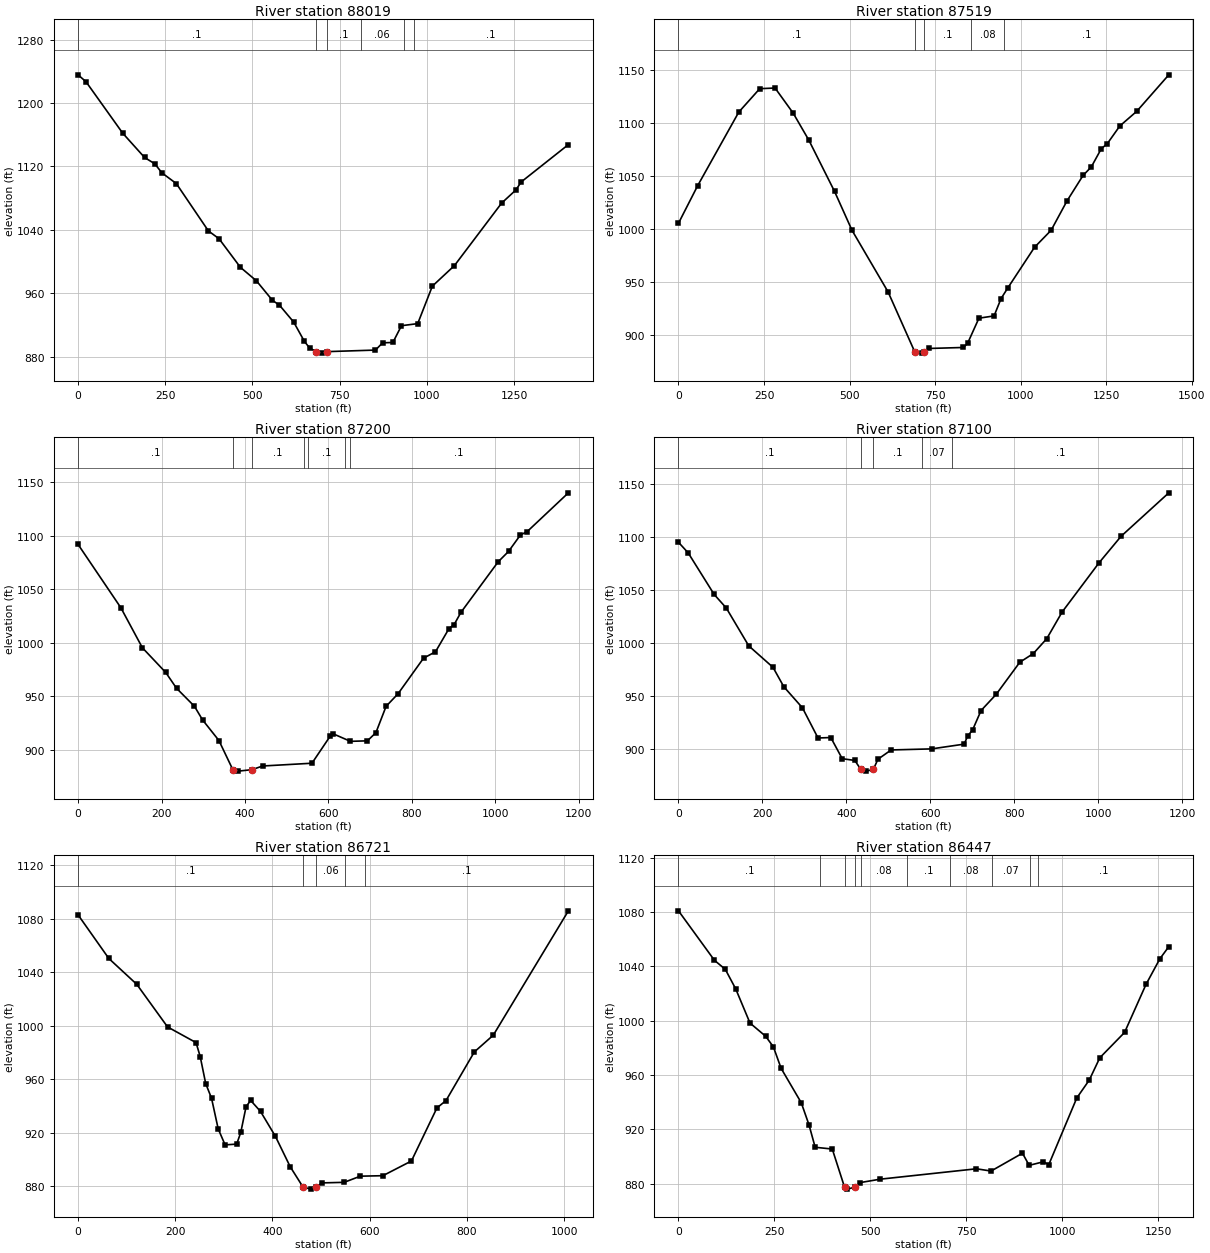
Type RM Length L Ch R = 1 ,88019   ,508.5,500,487.6
XS GIS Cut Line= 6
1675619.20735642356766.2428025011675678.50776276356846.546447679
1675740.22220625356924.2848092621675862.21868142357076.815672174
1676423.93212493357788.983867258  1676508.574016357849.696672335
#Sta/Elev= 30
       0 1235.51    22.7 1226.84   128.1  1161.9   190.6 1131.35     220 1123.33
   240.5  1111.9   281.7 1098.43   373.6 1038.79   404.1 1028.92   465.4  992.88
   511.2  975.92   557.1  951.33   577.4  945.14   618.2  923.82   648.8  899.57
   664.1  891.06  682.66886.6124   699.7  884.73  713.71886.6118   852.6  888.58
   872.9   897.7   902.5  898.17   927.1   919.3   973.7  921.92  1015.6  969.14
  1079.1  995.14  1214.3 1073.87    1255 1090.31  1270.3 1100.49  1405.6 1147.58
#Mann= 6 ,-1,0
       0      .1       0  682.66    .045       0  713.71      .1       0
  810.65     .06       0  933.15     .07       0  963.15      .1       0
Bank Sta=682.66,713.71
XS Rating Curve= 0 ,0
Exp/Cntr(USF)=0,0
Exp/Cntr=0.3,0.1

Type RM Length L Ch R = 1 ,87519   ,338.4,318.4,294
BEGIN DESCRIPTION:
Structure 25 XS 4
END DESCRIPTION:
XS GIS Cut Line= 6
1675083.16905843357565.6322798431675561.79900667357660.240030259
1676165.73841558357779.619384676 1676260.4075176357809.838812426
1676368.79476801357841.594654426 1676481.0051735357876.002394006
#Sta/Elev= 30
       0 1005.37    56.2 1040.93   176.3 1110.39   237.5 1132.48   282.3 1133.11
   335.3 1109.38   381.2 1083.77   456.1  1035.5   507.1  998.79   612.6  940.55
  690.82883.7583   710.4  882.71  718.86883.7595   730.8   887.1   832.8  888.05
     845  891.92   878.2  915.71   922.5  917.87   942.8  934.21   963.2  944.58
  1040.7  982.68  1089.3  998.78  1135.4 1026.35  1182.5 1050.51  1206.8 1058.65
  1235.9 1075.81  1253.2 1080.46  1290.1 1097.28  1339.5 1111.12  1433.2 1145.57
#Mann= 5 ,-1,0
       0      .1       0  690.82    .045       0  718.86      .1       0
  855.39     .08       0  952.89      .1       0
Bank Sta=690.82,718.86
XS Rating Curve= 0 ,0
Exp/Cntr(USF)=0,0
Exp/Cntr=0.3,0.1

Type RM Length L Ch R = 1 ,87200   ,98.1,100.5,105.9
BEGIN DESCRIPTION:
Structure 25 XS 3
END DESCRIPTION:
XS GIS Cut Line= 5
1675416.75099148357986.5638060481675694.12809817358096.667695727
1675738.59313054358026.7940734311675829.64057777357872.225151381
1676433.09458851357988.681188542
#Sta/Elev= 30
       0 1091.81   102.6 1032.66   154.2  995.27   210.2  972.21     236  957.48
     279  940.62   298.4  927.94   337.6  908.69  370.93881.4568   384.2   880.1
  416.74881.4587   442.4  884.89   560.6  887.48   603.9  912.51     612  914.85
   652.8  907.92   693.5  908.39   713.9  916.04   738.3  940.63   766.9  952.32
     828  985.56   856.7  991.57   889.1 1013.24   901.3 1016.91   917.6 1028.31
  1006.9 1075.56  1031.7 1085.22  1060.2 1100.59  1076.5 1103.79  1175.2 1139.97
#Mann= 7 ,-1,0
       0      .1       0  370.93    .045       0  416.74      .1       0
  541.25     .07       0  551.25      .1       0  640.64     .07       0
  650.64      .1       0
Bank Sta=370.93,416.74
XS Rating Curve= 0 ,0
Exp/Cntr(USF)=0,0
Exp/Cntr=0.3,0.1

Type RM Length L Ch R = 1 ,87100   ,350.2,379,394.8
BEGIN DESCRIPTION:
Structure 25 XS 2
END DESCRIPTION:
XS GIS Cut Line= 5
1675397.69454903358050.0852808631675776.02325761358145.618561656
1675827.52319528358060.6721933321675893.16205259357946.333538665
 1676437.3293535358003.502865999
#Sta/Elev= 30
       0 1095.12    23.1 1085.16      85 1045.99   113.9  1033.2   167.5  997.51
   225.3  977.26     251  959.01   295.4  939.13   332.5   910.7     363  911.13
   390.2  891.19   420.2  889.55   434.6881.0742   447.6  879.47  464.38881.0728
   475.3  890.67   506.8  899.42   603.2  900.43   680.7  904.91   689.6  912.86
   700.8   918.2   721.1  936.58   757.1  951.81   813.4  982.07   845.6  990.26
   877.7 1004.32   914.3 1029.44  1002.4 1075.87  1054.7 1100.76  1168.5 1141.73
#Mann= 5 ,-1,0
       0      .1       0   434.6    .045       0  464.38      .1       0
  579.54     .07       0  651.38      .1       0
Bank Sta=434.6,464.38
XS Rating Curve= 0 ,0
Exp/Cntr(USF)=0,0
Exp/Cntr=0.3,0.1

Type RM Length L Ch R = 1 ,86721   ,263.9,274.3,277.7
BEGIN DESCRIPTION:
Structure 25 XS 1
END DESCRIPTION:
XS GIS Cut Line= 3
1675418.15483446358077.6432028131675690.01629046358422.698127734
1676181.45815323358710.243898501
#Sta/Elev= 30
       0 1082.78    63.3 1050.17   120.8 1030.84   184.1  999.01   242.7  987.28
   251.3  976.83   262.6  956.63   274.6   945.7   288.3  922.76   302.5  910.83
   326.3   911.4   334.7  920.09   345.7  939.47   355.1  944.04   375.4   935.8
     406   917.2   436.5  894.44   462.7879.3539   478.8  877.75  489.84879.3563
     502  882.41   547.4  882.83   580.7  887.43   627.1  887.79   685.8  898.78
   738.3  938.46   756.9  943.93   815.2   980.3   854.2  992.83  1008.7 1085.79
#Mann= 5 ,-1,0
       0      .1       0   462.7    .045       0  489.84     .06       0
  549.29     .07       0  589.29      .1       0
Bank Sta=462.7,489.84
XS Rating Curve= 0 ,0
Exp/Cntr(USF)=0,0
Exp/Cntr=0.3,0.1

Type RM Length L Ch R = 1 ,86447   ,561.1,582.4,614.7
BEGIN DESCRIPTION:
Structure 24 XS 4
END DESCRIPTION:
XS GIS Cut Line= 4
1675406.16407901358115.7241381721675463.33340634   358518.026812
1675740.80732979358986.8629299791676067.46707072358991.510134355
#Sta/Elev= 30
       0 1080.83    93.7 1044.41     122 1037.78   149.4 1023.23   186.4  998.22
   227.1  988.53   247.3  980.72   267.5  964.89     320  939.56   340.2  923.24
   356.2  906.81   400.8   905.5  432.77877.4307   439.3     876   460.5877.4322
   474.3  880.85   525.7  883.32   776.5  890.97   814.6   889.3   896.4  902.44
   913.9   893.5   951.1  896.13     965  894.01    1038   943.1  1070.5  956.27
    1098  972.68  1162.5  991.32  1218.5 1026.74  1254.5 1045.53  1277.8 1054.47
#Mann= 10 ,-1,0
       0      .1       0     370     .05       0  432.77    .045       0
   460.5     .05       0  476.34     .08       0  596.34      .1       0
  706.34     .08       0  816.34     .07       0  916.34     .06       0
  936.34      .1       0
Bank Sta=432.77,460.5
XS Rating Curve= 0 ,0
Exp/Cntr(USF)=0,0
Exp/Cntr=0.3,0.1

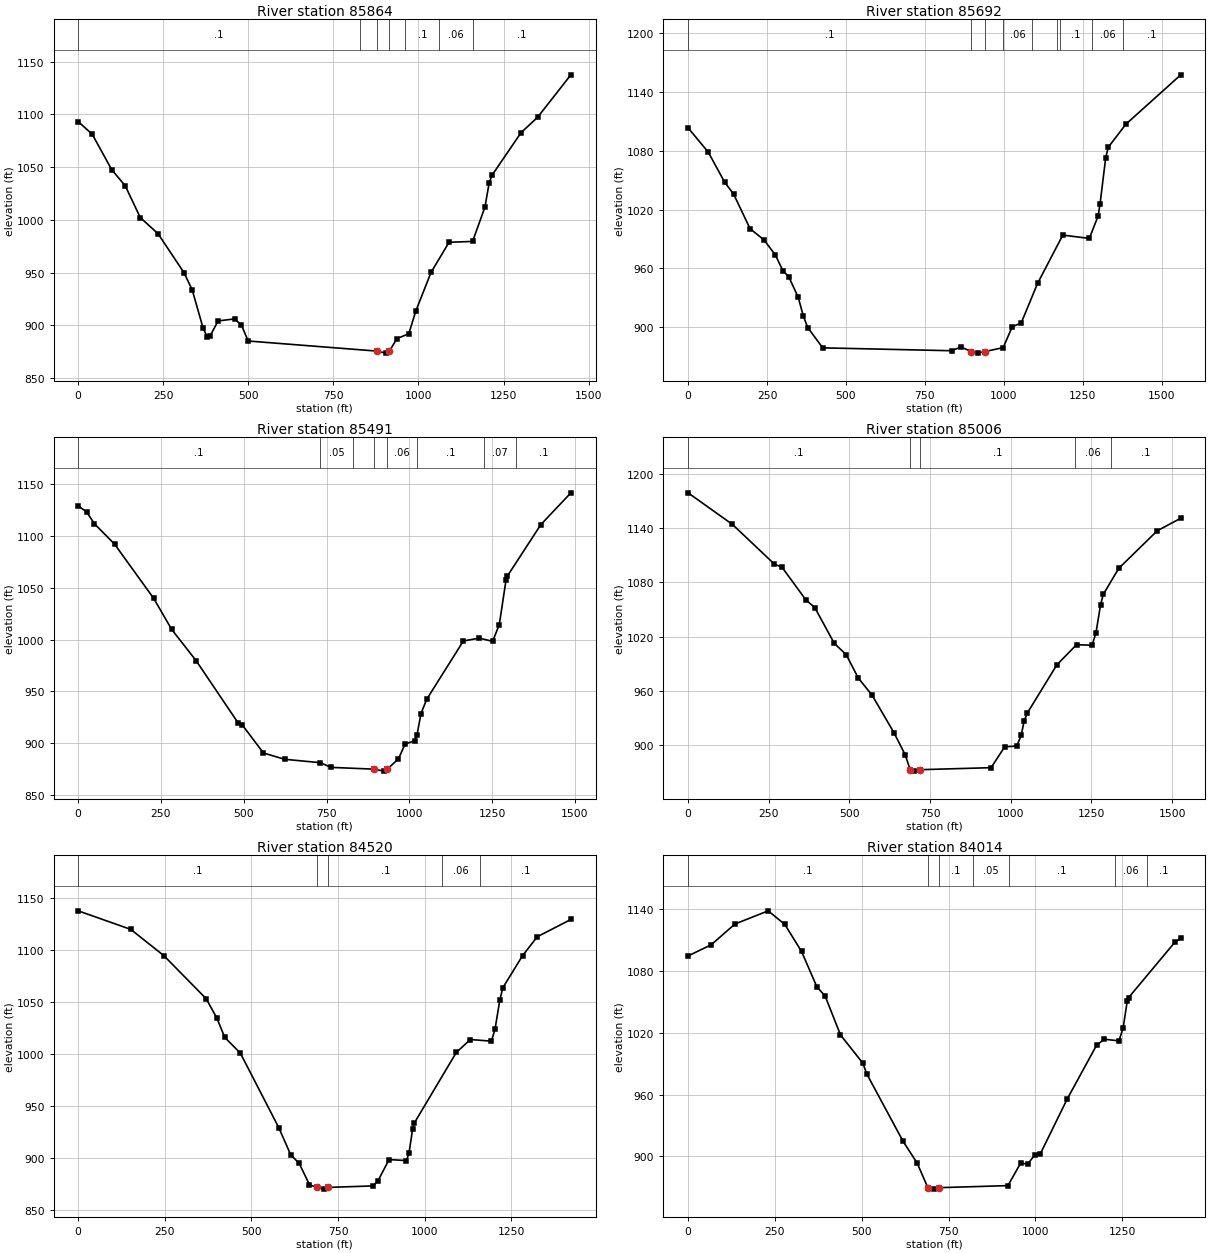
Type RM Length L Ch R = 1 ,85864   ,176.1,171.8,176.3
BEGIN DESCRIPTION:
Structure 24 XS 3
END DESCRIPTION:
XS GIS Cut Line= 6
1675366.55310085358114.5468426911675328.00399152358612.665099052
1675206.79031248 358676.166583271675063.07873159358727.704181633
 1674906.2355839358768.3672199231674813.29149638359256.323679407
#Sta/Elev= 30
       0 1093.19    41.4 1081.15    98.3 1047.72   138.4 1032.24   182.5 1002.21
   234.7  986.91   310.9  950.02     335  933.83   367.1  897.43   379.1  889.28
   387.1  889.75   411.2  904.27   459.4  906.17   479.4  900.58   499.6  885.24
  878.74875.6538     904  873.75  914.41875.6566   936.8  887.46   971.7  892.19
     992  913.48  1036.8   950.2  1089.9  978.82    1159  979.59  1195.2 1011.99
  1207.9 1035.37    1216 1042.28  1301.5 1082.71  1349.9 1097.19  1447.9 1137.49
#Mann= 7 ,-1,0
       0      .1       0  829.12     .06       0  878.74    .045       0
  914.41     .06       0  961.15      .1       0 1061.15     .06       0
 1161.15      .1       0
Bank Sta=878.74,914.41
XS Rating Curve= 0 ,0
Exp/Cntr(USF)=0,0
Exp/Cntr=0.3,0.1

Type RM Length L Ch R = 1 ,85692   ,208.7,201.6,166.3
BEGIN DESCRIPTION:
Structure 24 XS 2
END DESCRIPTION:
XS GIS Cut Line= 6
1675341.15872794358100.7411257541675313.68794107358478.704066662
1675235.26636723358519.3671049531675116.18175509358565.839148713
1674733.89457414358691.8399463821674741.50090228359254.206296913
#Sta/Elev= 30
       0 1103.26      64 1078.46   116.1 1047.73   144.2 1035.78   196.3 1000.49
   240.4  989.08   276.5  973.73   300.6  957.46   318.7  951.64     349  930.49
   364.8  911.69     379  899.79   426.4   879.1   834.5  876.16   864.5  880.02
  897.12875.2877   916.7  873.72  939.87 875.287   998.1  879.34  1026.8  900.75
  1054.8  904.22  1106.8  944.69  1186.8  993.96  1270.8   990.6  1298.8  1013.5
  1304.9 1026.01  1322.8    1073  1330.8 1083.45  1386.8    1107  1560.5 1157.25
#Mann= 9 ,-1,0
       0      .1       0  897.12    .045       0  939.87      .1       0
  998.09     .06       0 1088.09      .1       0 1168.09     .06       0
 1178.09      .1       0 1278.09     .06       0 1378.09      .1       0
Bank Sta=897.12,939.87
XS Rating Curve= 0 ,0
Exp/Cntr(USF)=0,0
Exp/Cntr=0.3,0.1

Type RM Length L Ch R = 1 ,85491   ,490.5,485,475.2
BEGIN DESCRIPTION:
Structure 24 XS 1
END DESCRIPTION:
XS GIS Cut Line= 6
1674423.82129546357806.1774540111674629.30792211 358152.67947952
1674635.60096275358307.605933663 1674621.2889835358923.390463246
1674594.78378717359120.5167094141674607.74537542359234.611953659
#Sta/Elev= 30
       0 1129.37    25.3  1123.5    49.2 1111.96   109.7 1092.39     228 1039.89
   282.2 1009.94   356.2  979.62   482.8  919.55   494.8  917.82   559.5  890.39
   623.1   884.3   731.2     881   763.2  876.46  893.94874.7442   923.2  872.84
  933.21874.7408   967.2  884.66   987.2  899.03  1016.1  902.18  1023.2  907.86
  1035.2  928.49  1052.5   942.3  1163.2  998.68  1211.4 1001.42  1251.6  998.33
  1271.7 1014.54    1292 1057.56    1296 1061.41  1397.3 1111.24  1487.9 1141.93
#Mann= 8 ,-1,0
       0      .1       0  730.95     .05       0  830.95      .1       0
  893.94    .045       0  933.21     .06       0 1023.45      .1       0
 1224.07     .07       0 1322.89      .1       0
Bank Sta=893.94,933.21
XS Rating Curve= 0 ,0
Exp/Cntr(USF)=0,0
Exp/Cntr=0.3,0.1

Type RM Length L Ch R = 1 ,85006   ,490.3,486.2,477.7
XS GIS Cut Line= 2
1673826.84578368358037.4131604281674597.27483296359355.457284714
#Sta/Elev= 30
       0 1178.77   137.3 1143.94   267.7    1100   290.9 1096.72     365 1060.59
   392.8 1052.02     453  1012.6   490.1 1000.05   527.2  974.42   570.5  955.21
   638.4  913.67   672.8  889.55  688.28873.1042   698.6  871.53  718.07873.1037
   938.9  875.34   981.2  898.41  1018.3  899.15  1032.2  910.95  1041.2  926.74
  1050.7  935.36  1142.6  988.79  1203.6 1011.09  1251.8 1010.49  1263.9 1024.14
  1278.1 1055.15  1286.6 1066.62  1334.2 1095.26  1453.5 1136.81  1526.7 1150.74
#Mann= 5 ,-1,0
       0      .1       0  688.28    .045       0  718.07      .1       0
    1200     .06       0    1310      .1       0
Bank Sta=688.28,718.07
XS Rating Curve= 0 ,0
Exp/Cntr(USF)=0,0
Exp/Cntr=0.3,0.1

Type RM Length L Ch R = 1 ,84520   ,511.6,505.5,492.8
XS GIS Cut Line= 6
1673328.96160884358721.8734056651673771.48008075358931.472067833
1673846.87002183358976.2980936771674052.37354784   359120.574708
1674477.29297359359340.5496617561674561.97095384359418.065582842
#Sta/Elev= 30
       0 1137.98   151.9 1120.07   247.5 1094.72   369.3  1053.3   400.5 1034.42
     423    1016     468 1000.85     579  928.97   613.4  902.81     638  894.52
   667.6  873.94  689.64871.4113   710.3  869.74  721.97871.4081   851.3  872.84
   865.1  877.67   897.3  898.23   947.4  897.25   954.8  904.45   965.5  928.17
   970.1  933.43  1091.4  1001.5  1131.8 1013.91  1192.8 1012.36  1203.3 1024.34
  1216.7 1051.66  1225.6 1063.86  1282.4 1094.72  1324.9 1112.96    1422 1129.68
#Mann= 5 ,-1,0
       0      .1       0  689.64    .045       0  721.97      .1       0
 1051.33     .06       0 1158.79      .1       0
Bank Sta=689.64,721.97
XS Rating Curve= 0 ,0
Exp/Cntr(USF)=0,0
Exp/Cntr=0.3,0.1

Type RM Length L Ch R = 1 ,84014   ,512,512.5,508.2
XS GIS Cut Line= 6
1673129.62998651359488.6766620871673523.70137684359502.699599922
1673879.18458976 359526.059461341674332.40120301359461.049420759
1674433.83439909359455.0523855091674540.24166659359475.316780671
#Sta/Elev= 30
       0 1094.71    66.5 1105.51   134.9  1125.7   230.6 1138.52   278.6 1125.29
   326.7 1099.03   370.7 1064.77   394.7 1055.67   438.8 1017.98     503   990.6
     515  979.76   619.2  914.48   659.3  893.66  690.36   869.6   707.4  868.19
   723.4  869.61   920.9   871.6   957.4  893.39   977.7  892.55     998  901.24
  1014.2  902.51  1091.2  955.51    1176 1007.94  1198.3 1013.83  1240.4 1012.19
  1252.4 1024.52  1264.4  1050.9  1268.4 1054.26  1402.1 1108.28  1418.5 1111.67
#Mann= 7 ,-1,0
       0      .1       0  690.36    .045       0   723.4      .1       0
  820.58     .05       0  925.11      .1       0 1228.62     .06       0
 1320.23      .1       0
Bank Sta=690.36,723.4
XS Rating Curve= 0 ,0
Exp/Cntr(USF)=0,0
Exp/Cntr=0.3,0.1

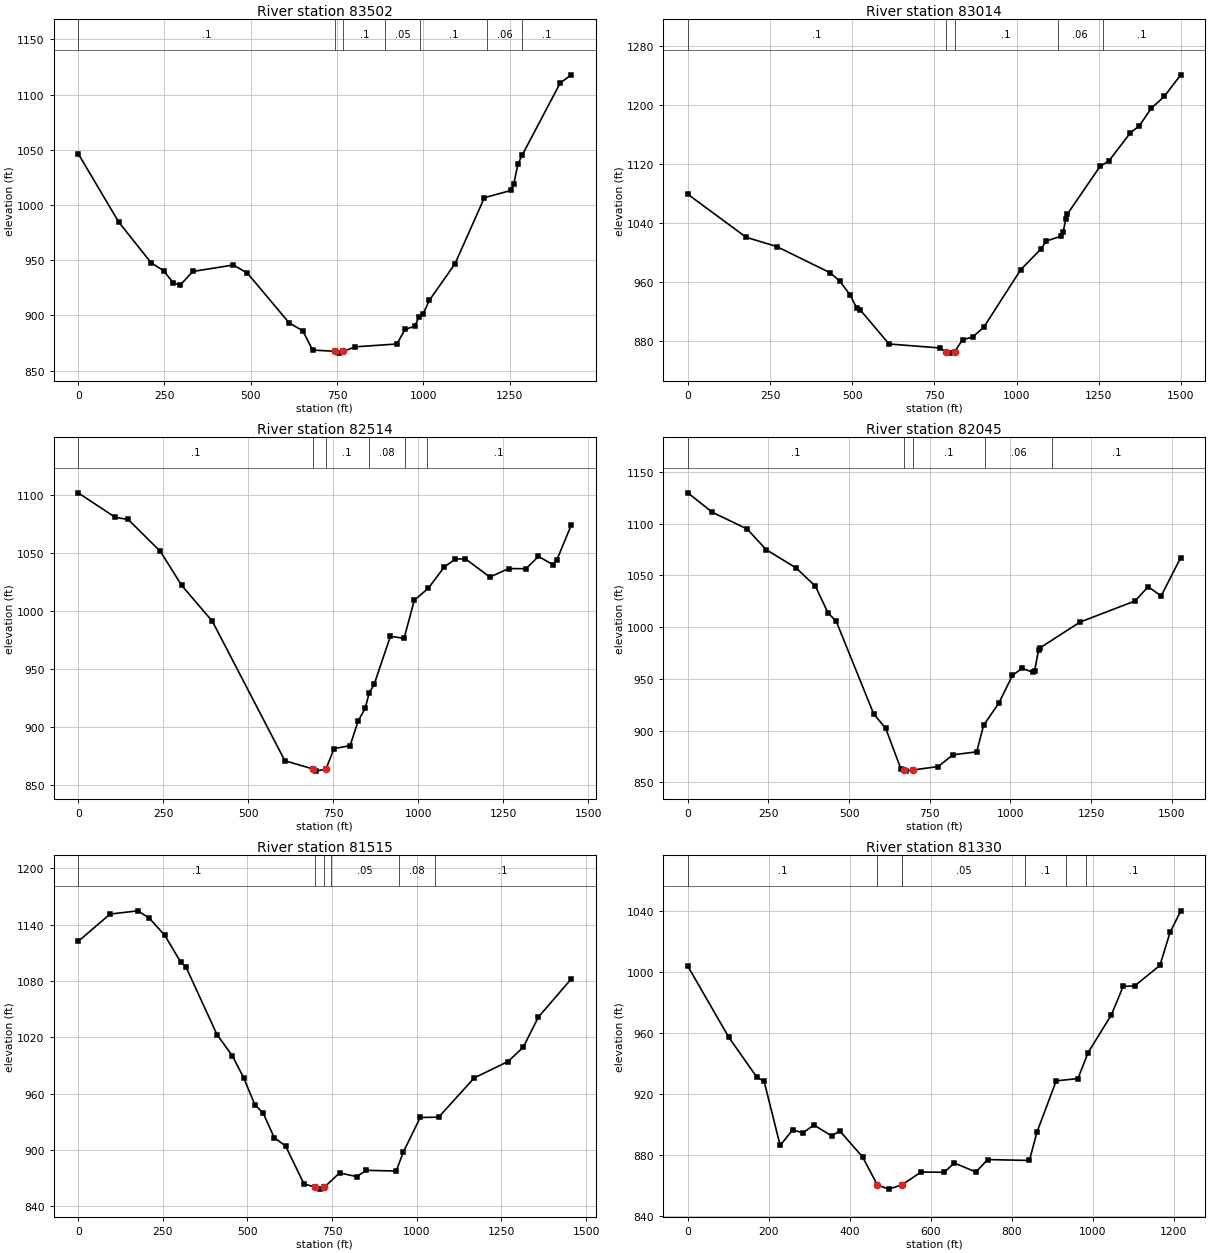
Type RM Length L Ch R = 1 ,83502   ,474.9,487.3,493
XS GIS Cut Line= 5
1673171.39328752359924.9103407811673379.11668921359953.768550778
1673765.20165233360012.9401021651674210.10719244 360006.29972097
1674587.82158248360070.614971853
#Sta/Elev= 30
       0 1046.55   117.3  984.67   210.7  947.93   248.1  940.36   275.5  929.45
   295.7   927.5   332.1  939.85   449.5   945.7   490.2  938.36   611.2  893.34
   651.2  885.99   679.2  868.67  742.88867.5859   755.2   865.9  768.32 867.586
   803.2  871.59   923.3  874.19   947.3  887.35   975.3  890.39   987.3  898.31
   999.3  901.07  1017.4  913.66  1091.9  946.82  1177.1 1006.64  1254.2 1013.26
  1262.4  1019.5  1274.5 1037.35  1286.7 1045.22  1396.3 1110.29  1428.4 1117.92
#Mann= 7 ,-1,0
       0      .1       0  742.88    .045       0  768.32      .1       0
  890.31     .05       0  990.31      .1       0 1185.27     .06       0
 1285.27      .1       0
Bank Sta=742.88,768.32
XS Rating Curve= 0 ,0
Exp/Cntr(USF)=0,0
Exp/Cntr=0.3,0.1

Type RM Length L Ch R = 1 ,83014   ,493.7,500.4,506.8
XS GIS Cut Line= 6
1673183.80409075360085.5156915041673507.77785225360232.429111585
1673716.07435167360306.7596715841673802.66112076360345.129345506
1673945.46332859360449.7088607551674425.08966592360889.449451089
#Sta/Elev= 30
       0 1078.43   177.6 1020.09   270.7 1007.54     433  972.06   462.8  960.43
   493.4  942.09   513.6  924.45   524.9   921.4     612  875.54   765.7   870.2
  784.79865.0603   798.3  863.15  811.45865.0577   835.5  881.13   866.7  885.12
   900.2  898.27  1012.7  976.31  1074.8 1004.66  1090.4 1015.08  1135.7 1021.68
  1141.4 1026.77  1149.8 1045.14  1154.8 1051.77  1253.9 1116.25    1281 1123.64
  1346.1 1161.68  1373.5 1171.32  1410.3 1195.27  1449.2 1210.98  1499.4  1240.3
#Mann= 5 ,-1,0
       0      .1       0  784.79    .045       0  811.45      .1       0
 1125.31     .06       0 1262.19      .1       0
Bank Sta=784.79,811.45
XS Rating Curve= 0 ,0
Exp/Cntr(USF)=0,0
Exp/Cntr=0.3,0.1

Type RM Length L Ch R = 1 ,82514   ,477.2,469.3,456
XS GIS Cut Line= 6
1673146.53808917360109.1734525861673220.94738917 360187.27369009
1673265.86265367360275.7849960031673744.15992543361157.539794177
1673837.08034326361219.5088303391673956.74513017361262.962483585
#Sta/Elev= 30
       0 1101.68   109.3 1080.55   146.9 1078.76   241.8 1051.24   304.2 1022.05
   394.5  991.16   607.6  871.19   691.5863.9887   699.5  862.24  728.39863.9892
   752.2   881.6   799.4  884.16     823  905.35   843.6  916.15   855.4  929.28
   870.2  936.91   917.9  978.23   958.2   976.5   988.2 1009.26  1029.5 1019.62
  1076.7 1037.96  1109.1 1044.71  1138.6 1044.88  1210.3 1029.24  1266.1 1036.53
  1316.6 1036.37  1353.2 1046.98  1395.3 1039.94    1407 1043.71  1449.3 1073.67
#Mann= 6 ,-1,0
       0      .1       0   691.5    .045       0  728.39      .1       0
  853.69     .08       0  961.19     .06       0 1024.94      .1       0
Bank Sta=691.5,728.39
XS Rating Curve= 0 ,0
Exp/Cntr(USF)=0,0
Exp/Cntr=0.3,0.1

Type RM Length L Ch R = 1 ,82045   ,539.3,530.2,520.7
XS GIS Cut Line= 2
1672504.94467628360742.9856849051673937.04995959361275.740017086
#Sta/Elev= 30
       0 1129.86    75.9 1111.06   184.1 1094.87   242.4 1075.04   335.8 1057.24
   395.6 1039.59   434.4 1013.88     460 1005.68     576  916.31   613.4  902.18
   660.6  862.96   669.2  861.99   677.7  860.91     697  861.99   775.9  865.33
   821.8  876.68   895.4  879.54   916.7  905.23   963.6  926.39  1006.3  953.38
  1036.2  960.36  1070.6  956.25  1074.6  957.56  1087.4  978.16  1091.7     980
  1215.4 1004.89  1386.2 1025.38    1427 1039.05  1467.2 1030.23    1528 1067.35
#Mann= 5 ,-1,0
       0      .1       0   669.2    .045       0     697      .1       0
     920     .06       0    1130      .1       0
Bank Sta=669.2,697
XS Rating Curve= 0 ,0
Exp/Cntr(USF)=0,0
Exp/Cntr=0.3,0.1

Type RM Length L Ch R = 1 ,81515   ,213.6,184.7,151.4
XS GIS Cut Line= 6
1672549.05437601361682.6699775011672836.35202976361589.598313257
1673187.62626159361493.868845925  1673713.622913361326.599167332
  1673821.811673361304.038516924  1673949.110631361305.227162838
#Sta/Elev= 30
       0 1122.12    94.1  1151.2     176 1154.67   209.6 1146.99   255.7 1128.66
   302.7  1100.1   318.4 1094.82   409.9 1022.96   455.3 1000.32   488.6  977.05
   521.6  948.42     547  938.89     579  913.15   612.7  904.21   666.6  864.08
   700.4  860.32   713.1  858.33   727.2   860.4   772.1  875.63   822.2  871.66
   851.5  878.34   939.3  877.61   960.2  897.62  1010.3  934.65  1064.7  934.92
  1169.9   976.8  1269.7  994.21  1314.7 1009.48  1359.2 1041.46    1456 1081.99
#Mann= 6 ,-1,0
       0      .1       0   700.4    .045       0   727.2      .1       0
  746.12     .05       0  949.04     .08       0 1052.81      .1       0
Bank Sta=700.4,727.2
XS Rating Curve= 0 ,0
Exp/Cntr(USF)=0,0
Exp/Cntr=0.3,0.1

Type RM Length L Ch R = 1 ,81330   ,72.9,82,92.2
XS GIS Cut Line= 6
1673084.21377512361826.678180637 1673292.3917079361919.765874155
1673290.69920438361775.9030750821673282.23668679361679.430374527
1673268.69665864361515.2575332321673833.99283382 361369.70223064
#Sta/Elev= 30
       0 1003.95   100.7  957.54   170.8  931.02   188.3  928.59     228   886.4
   259.3  896.86   283.3   894.5   311.3  899.86   355.3  892.65   375.3  895.95
   431.5  878.87  468.04860.5587   495.8  857.79  528.52860.5594     576  868.98
   633.5  868.85   657.7  874.96   711.4  868.99   740.3  877.18   843.5  876.58
   861.9  895.04   909.6  928.77   963.3  930.28   988.1  947.19  1046.1  972.17
  1074.8  990.68  1103.8  991.14  1165.7  1004.5  1190.7 1026.11  1217.2 1040.28
#Mann= 7 ,-1,0
       0      .1       0  468.04    .045       0  528.52      .1       0
  528.76     .05       0  833.49      .1       0  933.49     .06       0
  983.49      .1       0
Bank Sta=468.04,528.52
XS Rating Curve= 0 ,0
Exp/Cntr(USF)=0,0
Exp/Cntr=0.3,0.1

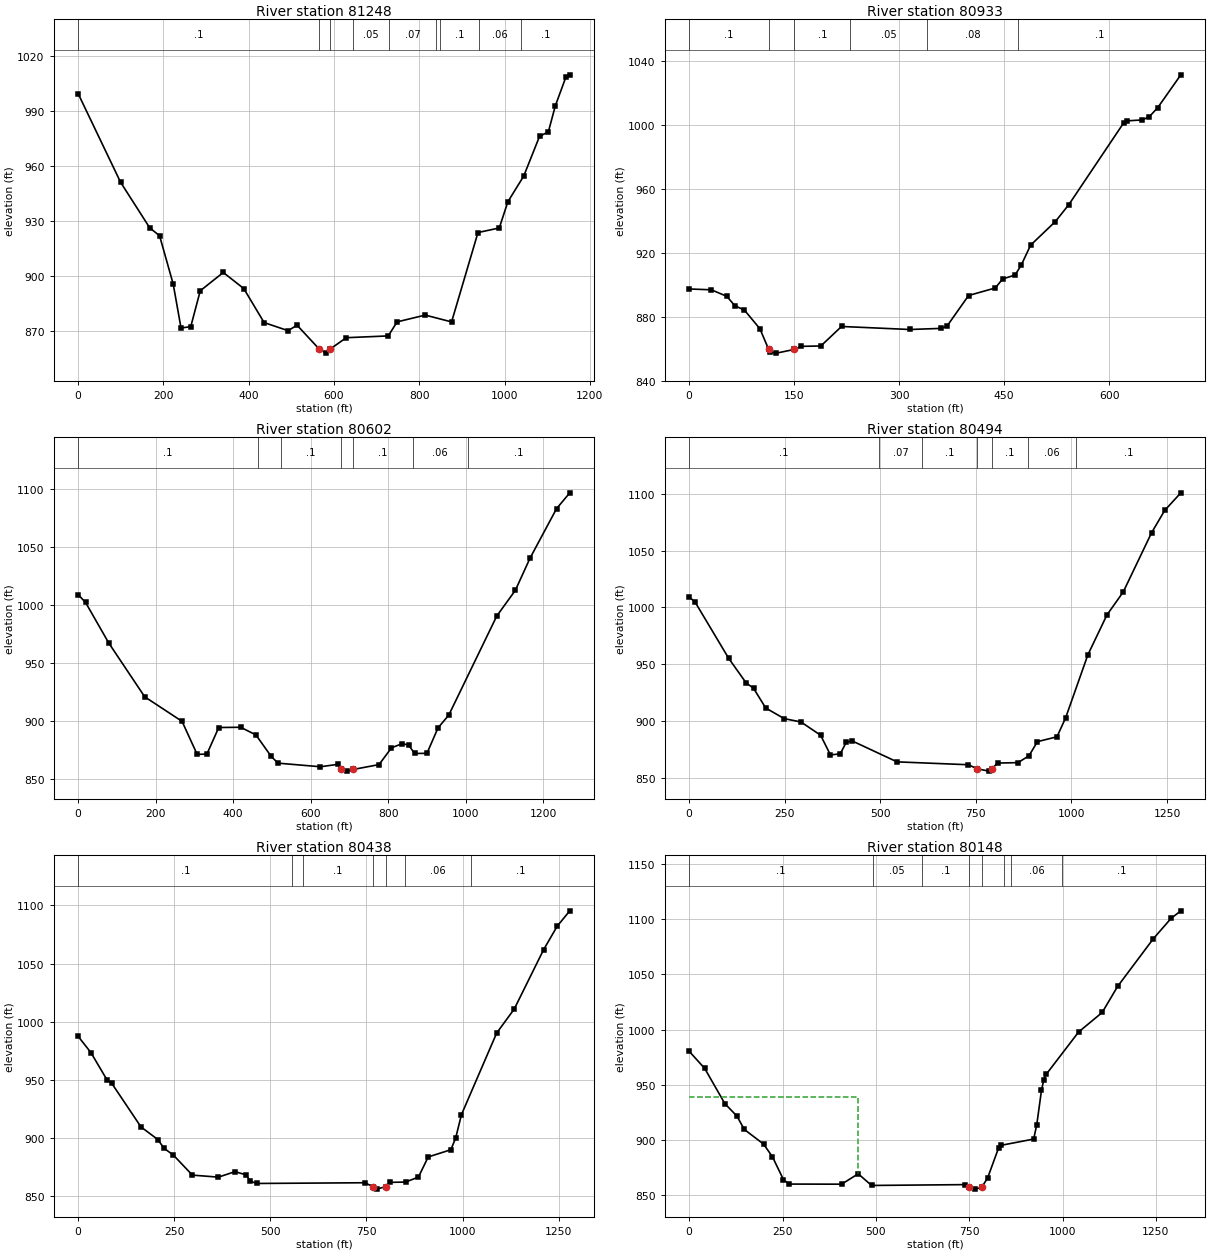
Type RM Length L Ch R = 1 ,81248   ,301.9,314.4,328.5
XS GIS Cut Line= 6
1673085.06002688361837.6794535081673335.55054762361976.464742025
1673365.16935919361904.533342489 1673360.9381004361820.754418322
1673338.93555466361560.1088764721673768.83144836361451.788651288
#Sta/Elev= 30
       0  999.33    99.5  951.08   168.1  926.19     191  921.96     223   895.6
   241.3  871.75   264.1  872.43   286.4  891.99   340.4  901.95   388.4  893.21
   436.2  874.67   492.4  870.27   513.4  873.25  564.98  860.36   580.8  858.05
  591.65860.3586   628.9  866.45   727.3  867.42     748  875.06     814  878.75
   875.8  875.04   937.7  923.69   987.6  926.17  1007.8  940.45    1045  954.44
  1082.1  976.07  1102.7  978.47  1119.2  992.74    1144 1008.39    1153 1009.53
#Mann= 9 ,-1,0
       0      .1       0  564.98    .045       0  591.65      .1       0
  644.89     .05       0  729.62     .07       0  839.62     .05       0
  849.62      .1       0  939.62     .06       0 1039.62      .1       0
Bank Sta=564.98,591.65
XS Rating Curve= 0 ,0
Exp/Cntr(USF)=0,0
Exp/Cntr=0.3,0.1

Type RM Length L Ch R = 1 ,80933   ,321.1,331.1,348.3
XS GIS Cut Line= 2
 1673347.4362069362022.392524915 1673982.0157403361721.300734292
#Sta/Elev= 30
       0  897.37    31.7  896.85    53.9  892.74      65  886.97      79  884.08
     101  872.51  113.58859.5179     116  857.75   124.7  857.19  150.36859.5164
   160.1  861.44   188.1  861.66   217.7  873.89   315.1  871.99   359.4  872.68
   368.2     874   399.2  893.28   437.3  897.99   447.9  903.67   465.6  906.08
   474.5   912.4   487.8  924.82   523.2  939.62   542.4  950.19   620.6 1001.29
     625 1002.64   647.5 1003.23   657.5 1005.34   669.3 1010.86   702.4 1031.48
#Mann= 6 ,-1,0
       0      .1       0  113.58    .045       0  150.36      .1       0
     230     .05       0     340     .08       0     470      .1       0
Bank Sta=113.58,150.36
XS Rating Curve= 0 ,0
Exp/Cntr(USF)=0,0
Exp/Cntr=0.3,0.1

Type RM Length L Ch R = 1 ,80602   ,93.8,108.2,111.4
BEGIN DESCRIPTION:
Structure 23 XS 4
END DESCRIPTION:
XS GIS Cut Line= 4
 1673055.8726375361826.1111677361673223.56933101362016.675592181
1673800.97953708362338.7294694931673983.92138455 362641.72690436
#Sta/Elev= 30
       0 1008.76    19.2 1001.99    79.1  967.06   171.9  920.73   268.2  899.63
   307.1  871.23   332.3   871.4   362.9  894.31   419.4  894.53   458.9  887.93
   498.2  869.49   515.8  863.63   625.5  860.52   671.3  862.65   679.3858.2031
   694.2  856.76  710.12858.2046   776.6  862.39   808.7  876.82   836.1   880.4
     853  879.26   868.2  871.96   900.3  872.08   928.8     894   956.5  904.94
  1080.6   990.4  1128.4 1012.43  1166.2 1040.09  1234.8  1082.8  1268.9 1096.38
#Mann= 7 ,-1,0
       0      .1       0  463.84     .07       0  523.84      .1       0
   679.3    .045       0  710.12      .1       0  863.84     .06       0
    1005      .1       0
Bank Sta=679.3,710.12
XS Rating Curve= 0 ,0
Exp/Cntr(USF)=0,0
Exp/Cntr=0.3,0.1

Type RM Length L Ch R = 1 ,80494   ,59.9,56.4,55.6
BEGIN DESCRIPTION:
Structure 23 XS 3
END DESCRIPTION:
XS GIS Cut Line= 6
1672960.14833464361863.0929021971673278.97309778362119.403005897
1673440.26091913362174.4159062041673490.27264668362221.927047377
 1673610.3007928362426.9751303371673859.10913737362733.296961589
#Sta/Elev= 30
       0    1009    15.1  1004.8   103.4  955.02   149.1  933.35   168.3  928.71
   200.2  911.29   248.5  901.94   292.5  898.97   343.8   887.3   369.5  869.96
   395.1  870.89   410.9  881.07   426.2  882.31   543.7  863.84   730.5  861.31
   752.2857.8639   783.6  855.68  792.44857.8663   806.5   862.8     860  863.15
   888.9  869.22   910.9  881.65     962  885.91   984.8  902.71  1042.8   958.1
  1092.8   993.3  1135.4 1013.52  1209.4  1065.6  1243.8 1085.31    1286 1100.81
#Mann= 7 ,-1,0
       0      .1       0  496.87     .07       0  609.55      .1       0
   752.2    .045       0  792.44      .1       0  884.95     .06       0
 1011.39      .1       0
Bank Sta=752.2,792.44
XS Rating Curve= 0 ,0
Exp/Cntr(USF)=0,0
Exp/Cntr=0.8,0.6

Type RM Length L Ch R = 1 ,80438   ,284.1,289.6,288
BEGIN DESCRIPTION:
Structure 23 XS 2
END DESCRIPTION:
XS GIS Cut Line= 6
1672906.38572752361915.6052161261673205.20579964362170.665026637
 1673298.9777888362183.1679585251673378.99655288362215.675581433
1673440.26091913362268.1878953621673815.34887576362762.053704931
#Sta/Elev= 30
       0  987.27    33.1  973.31    75.4  949.58    87.7  946.66   163.6  909.15
   207.4  898.32   223.2  890.84   247.9  884.89   297.2  867.66     365  865.92
   407.9  870.65   436.3  867.95   448.3  862.44   464.4  860.47   745.9  861.09
  766.55857.7654   776.6  855.59  800.34857.7671   810.7  861.41     852  861.71
   885.2  865.98   910.6  883.31   969.5  889.54   982.1  899.67   997.1  919.78
  1088.7  990.09  1134.5 1010.84  1210.8 1061.95  1246.4 1082.27  1278.9  1095.4
#Mann= 7 ,-1,0
       0      .1       0  557.47     .07       0  583.84      .1       0
  766.55    .045       0  800.34      .1       0   851.2     .06       0
 1022.16      .1       0
Bank Sta=766.55,800.34
XS Rating Curve= 0 ,0
Exp/Cntr(USF)=0,0
Exp/Cntr=0.3,0.1

Type RM Length L Ch R = 1 ,80148   ,619.5,636.2,641.5
BEGIN DESCRIPTION:
Structure 23 XS 1
END DESCRIPTION:
XS GIS Cut Line= 5
1672830.63073863361945.5986395761672989.82121396362122.070806185
1673143.71314571362299.4446178691673416.11729073362676.802239413
1673704.10856372362923.129945413
#Sta/Elev= 30
       0  980.37    41.7  964.77    95.5  932.93   127.9  921.63   147.6  909.53
   199.3   896.2   223.2  884.62   252.4  864.07   267.4  859.97   408.3  859.86
   452.8  869.28   488.6  858.71     740  859.47  750.45  856.91   765.8  855.38
  783.33  856.91   799.4   865.5   828.8   892.8     834  895.01   922.8  900.78
   931.1  913.96   943.6  944.81   949.8  954.47     956  959.33  1043.2  997.88
  1106.3 1015.56  1147.6  1039.2  1243.2  1082.4  1290.6 1100.81  1316.9 1107.71
#Mann= 8 ,-1,0
       0      .1       0  492.49     .05       0  622.49      .1       0
  750.45    .045       0  783.33      .1       0  842.49     .07       0
  862.49     .06       0   997.9      .1       0
#XS Ineff= 2 , 0
           450.9  939.22
Permanent Ineff=
       F       F
Bank Sta=750.45,783.33
XS Rating Curve= 0 ,0
Exp/Cntr(USF)=0,0
Exp/Cntr=0.3,0.1

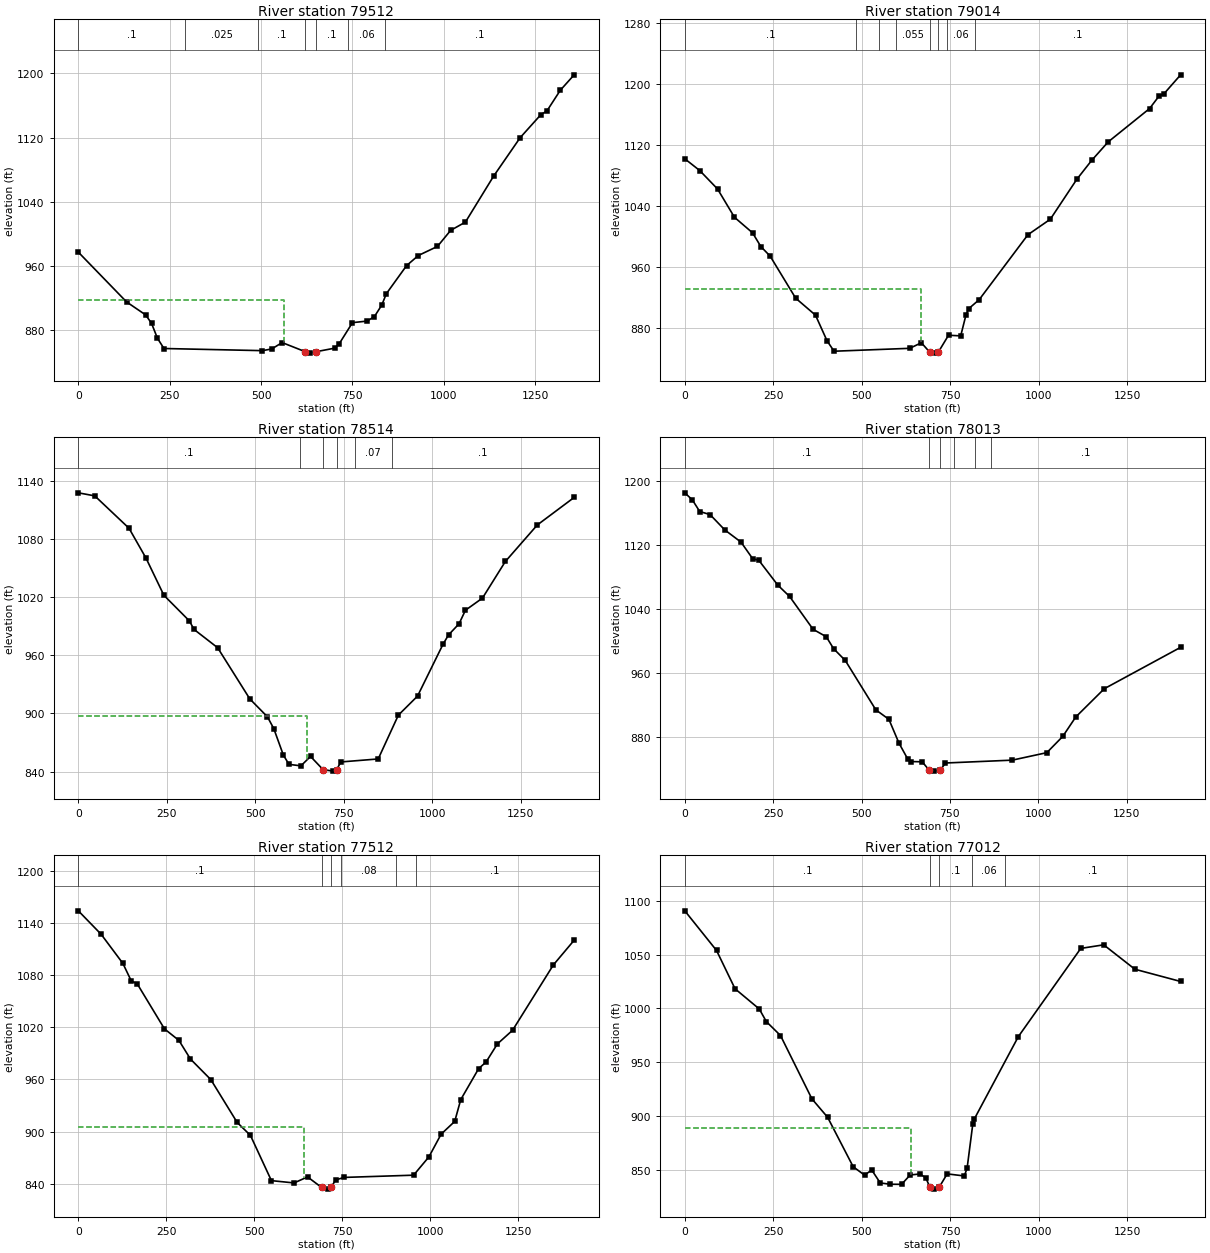
Type RM Length L Ch R = 1 ,79512   ,502.1,497.9,483.2
XS GIS Cut Line= 6
 1672547.7396041362037.3164531851672525.04630494362258.185549852
1672717.17182192362556.8923104261672695.23649834362828.947212502
1672714.35096142363027.9044917521672766.57231367363329.671604753
#Sta/Elev= 30
       0  977.41   131.9   915.5   184.2  899.29   200.3  888.85   216.4  870.28
   234.3  857.47   503.8  854.79   529.2  856.89   557.7  864.85  621.07853.4777
   633.2  851.71  650.43853.4805   701.7   857.9   713.8  863.31   750.2  889.67
   790.2   891.6   810.2  897.22   830.2  911.42     843  925.77   898.3  960.69
   930.4  973.24   982.7  984.55  1018.9 1004.55  1059.2 1014.83  1136.1 1071.84
  1209.1 1119.97    1266 1148.75  1282.1 1153.12    1319 1179.03  1356.8 1198.18
#Mann= 7 ,-1,0
       0      .1       0  292.03    .025       0  492.03      .1       0
  621.07    .045       0  650.43      .1       0  738.66     .06       0
  837.82      .1       0
#XS Ineff= 2 , 0
          562.62  917.59
Permanent Ineff=
       F       F
Bank Sta=621.07,650.43
XS Rating Curve= 0 ,0
Exp/Cntr(USF)=0,0
Exp/Cntr=0.3,0.1

Type RM Length L Ch R = 1 ,79014   ,499.5,500,501.2
XS GIS Cut Line= 6
1671897.30863225362204.3976085931672000.05481784362374.620365262
1672194.64760451362697.0068595861672369.05375175362985.951491669
1672569.70197251 363318.370446251672620.42496817363404.102230176
#Sta/Elev= 30
       0 1102.09    42.2 1086.66    92.5 1062.47   140.3 1025.36   191.5 1004.92
   214.8  986.95   241.1   974.4   313.2  919.25   369.3   896.9     402  863.18
   421.7  849.64   635.6  853.45   668.3  860.74  692.27848.2707   710.3  847.14
  716.04848.2687   745.1  870.61   779.5  869.77   794.6  897.69   802.7  905.66
   831.8  917.33   969.4 1002.46  1032.7 1022.82  1107.5 1075.17  1149.5 1099.97
  1196.2 1124.27    1313 1167.95  1339.6 1184.21  1354.2 1187.62  1400.8 1212.23
#Mann= 8 ,-1,0
       0      .1       0  484.14     .06       0  547.89     .07       0
  595.39    .055       0  692.27    .045       0  716.04     .07       0
  740.39     .06       0  820.39      .1       0
#XS Ineff= 2 , 0
          667.15  931.12
Permanent Ineff=
       F       F
Bank Sta=692.27,716.04
XS Rating Curve= 0 ,0
Exp/Cntr(USF)=0,0
Exp/Cntr=0.3,0.1

Type RM Length L Ch R = 1 ,78514   ,497.2,501.4,505.8
XS GIS Cut Line= 6
1671499.32878518362416.5730372521671543.98223917362505.626993001
1671588.55990592362594.2800309211671632.98599817362682.130905092
1671677.10861334362768.3777798411672142.59980834363660.926519677
#Sta/Elev= 30
       0 1127.69    46.4 1124.55   143.2 1091.13   191.3 1060.23   241.7 1021.95
   313.5  995.58     327  986.67   393.6  967.81   484.6  914.92   534.2  896.54
   552.3  884.23   579.3  856.94   595.2  847.43   628.9  845.91     656  855.64
  691.36842.0406   719.2  840.45   729.8  842.04   741.7  849.92   847.2  853.02
   904.1  898.22   958.3  917.89  1030.4  971.46  1045.9  981.06  1075.6  992.53
  1093.6 1006.49  1141.8 1019.06  1206.4 1056.82  1296.6 1094.49  1400.8 1122.94
#Mann= 6 ,-1,0
       0      .1       0  625.42    .055       0  691.36    .045       0
   729.8    .055       0  780.42     .07       0  885.42      .1       0
#XS Ineff= 2 , 0
          645.51  897.35
Permanent Ineff=
       F       F
Bank Sta=691.36,729.8
XS Rating Curve= 0 ,0
Exp/Cntr(USF)=0,0
Exp/Cntr=0.3,0.1

Type RM Length L Ch R = 1 ,78013   ,490.4,500.1,507.7
XS GIS Cut Line= 6
1671184.02167301362568.0596109181671268.01330292362854.668617755
1671293.81804134362948.1841787551671316.96432051363039.077697754
1671336.98199701363124.2638790911671516.03150767363929.999800429
#Sta/Elev= 30
       0  1184.7    21.4 1175.87    42.2 1161.35    71.4 1157.53   113.1 1138.34
     159 1123.11   192.4 1102.12     209  1100.6   263.1 1069.34   296.4  1055.2
   362.8 1014.18   400.2 1004.84   420.9  989.93   453.8  975.27   540.3  913.53
   577.3  901.63   605.9  871.81   630.5  852.11   638.7  848.89   671.5  848.61
  690.93838.2322   704.3  836.93  723.03838.2316   737.1  847.08   926.2  850.65
  1023.9  860.01    1069   880.3  1105.8  904.58  1186.6  939.93  1402.4  991.64
#Mann= 6 ,-1,0
       0      .1       0  690.93    .045       0  723.03      .1       0
  761.98     .06       0  821.98     .07       0  866.98      .1       0
Bank Sta=690.93,723.03
XS Rating Curve= 0 ,0
Exp/Cntr(USF)=0,0
Exp/Cntr=0.3,0.1

Type RM Length L Ch R = 1 ,77512   ,504.5,500.2,497
XS GIS Cut Line= 6
1671061.03963551362584.9683697521670999.40491626362879.825063512
1670948.36072701363065.4178681671670723.09050825 363638.50792934
1670693.22114542363732.4972426741670643.32459167363926.075923756
#Sta/Elev= 30
       0 1154.47    64.8 1127.41   126.5 1093.85   150.5 1073.51   166.8 1070.61
   244.6 1018.34   285.6  1005.1   318.5  983.52   376.3  959.85   451.1  910.46
   488.7  895.59   548.3  843.38   612.7  840.72     651  847.67  690.82835.5396
   707.7  833.58  717.77835.5412   730.8  844.24   755.2  847.09   952.1  849.66
   995.7  870.82  1030.3  896.96  1068.9  911.66    1086  936.76  1136.9  972.55
  1157.9  980.15    1190 1000.97  1233.2 1016.76    1349 1092.08  1408.1 1120.59
#Mann= 6 ,-1,0
       0      .1       0  690.82    .045       0  717.77      .1       0
  746.49     .08       0  901.49     .06       0  958.98      .1       0
#XS Ineff= 2 , 0
          641.84  905.52
Permanent Ineff=
       F       F
Bank Sta=690.82,717.77
XS Rating Curve= 0 ,0
Exp/Cntr(USF)=0,0
Exp/Cntr=0.3,0.1

Type RM Length L Ch R = 1 ,77012   ,508.6,500,482.4
XS GIS Cut Line= 6
1670453.11893535362499.4065330031670400.20401493362984.444604918
  1670333.854082363596.4643782531670326.72351883363694.704667345
1670321.36427759363793.9255975041670316.47353934363893.619295761
#Sta/Elev= 30
       0 1090.68    89.7 1053.84     142 1018.26   210.4  999.51   230.5  987.75
   270.4  974.85   359.2  915.99   403.5  898.92   475.9  852.91   508.1   845.1
   528.2  849.92   552.4  837.86   580.5  836.66   612.7  836.57   636.9  845.28
     665   846.2   681.1  842.57   692.1834.3425   704.4  832.12   719.7 834.345
   741.5  846.29   789.8  844.35   797.8  851.55   813.9  892.66   817.9  897.11
   942.6  973.83    1119 1055.77  1183.8 1059.09    1272  1036.4  1401.2 1025.05
#Mann= 5 ,-1,0
       0      .1       0   692.1    .045       0   719.7      .1       0
  810.42     .06       0  905.42      .1       0
#XS Ineff= 2 , 0
          639.54  888.45
Permanent Ineff=
       F       F
Bank Sta=692.1,719.7
XS Rating Curve= 0 ,0
Exp/Cntr(USF)=0,0
Exp/Cntr=0.3,0.1