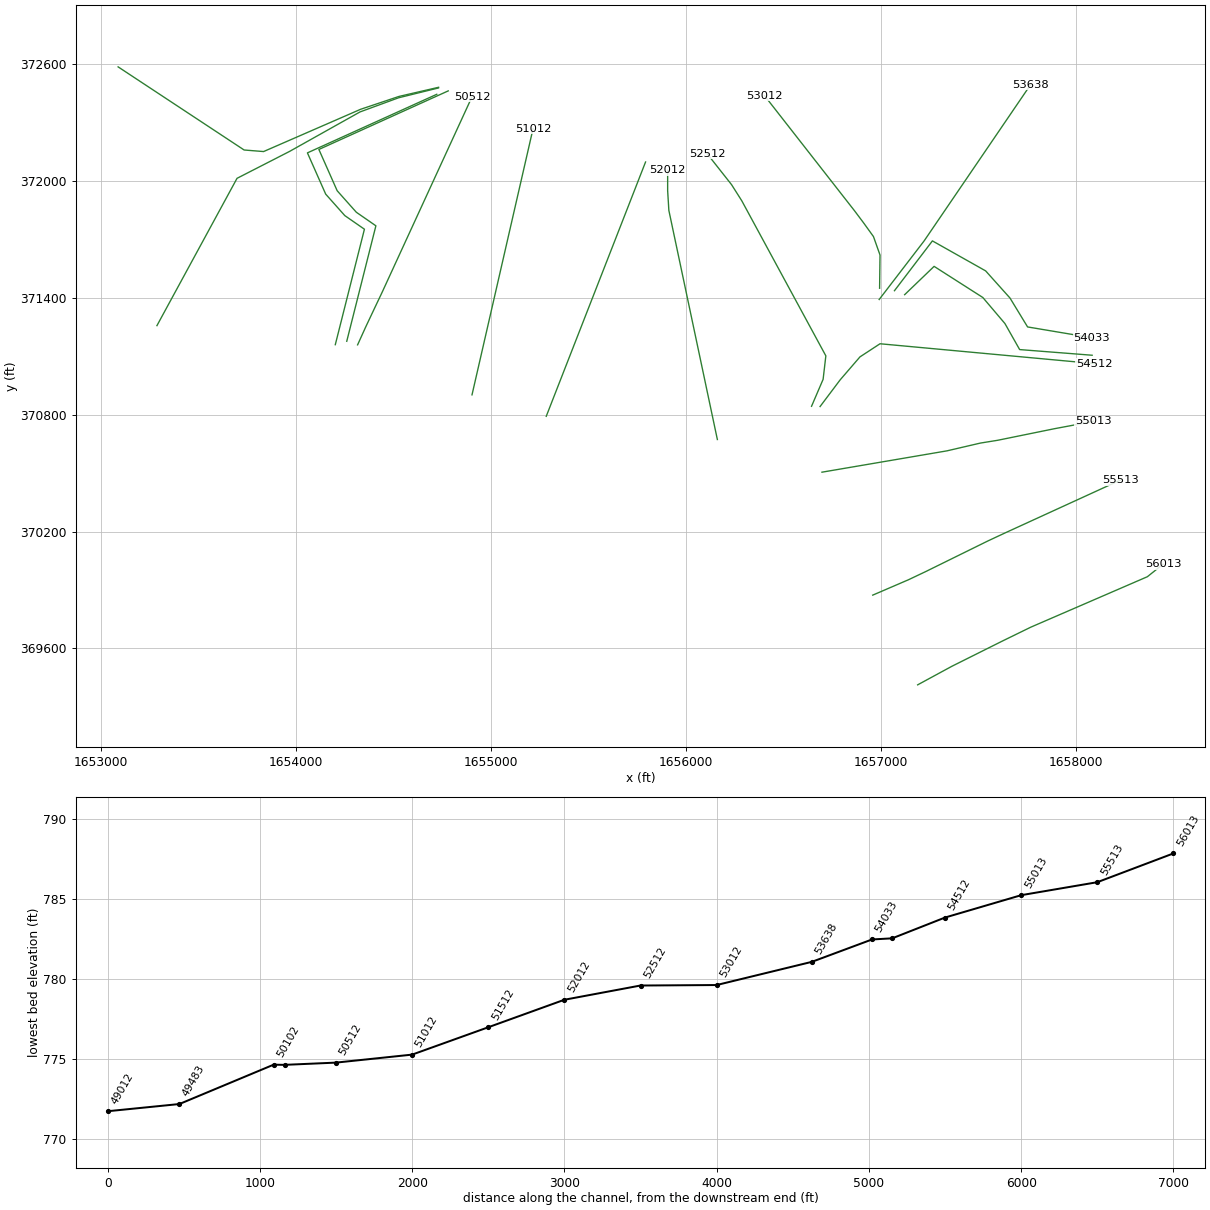
HEC-RAS study SFFSHGCK.prj: SFFSHGCK

--- SFFSHGCK.g01 (geometry) --- (continued)

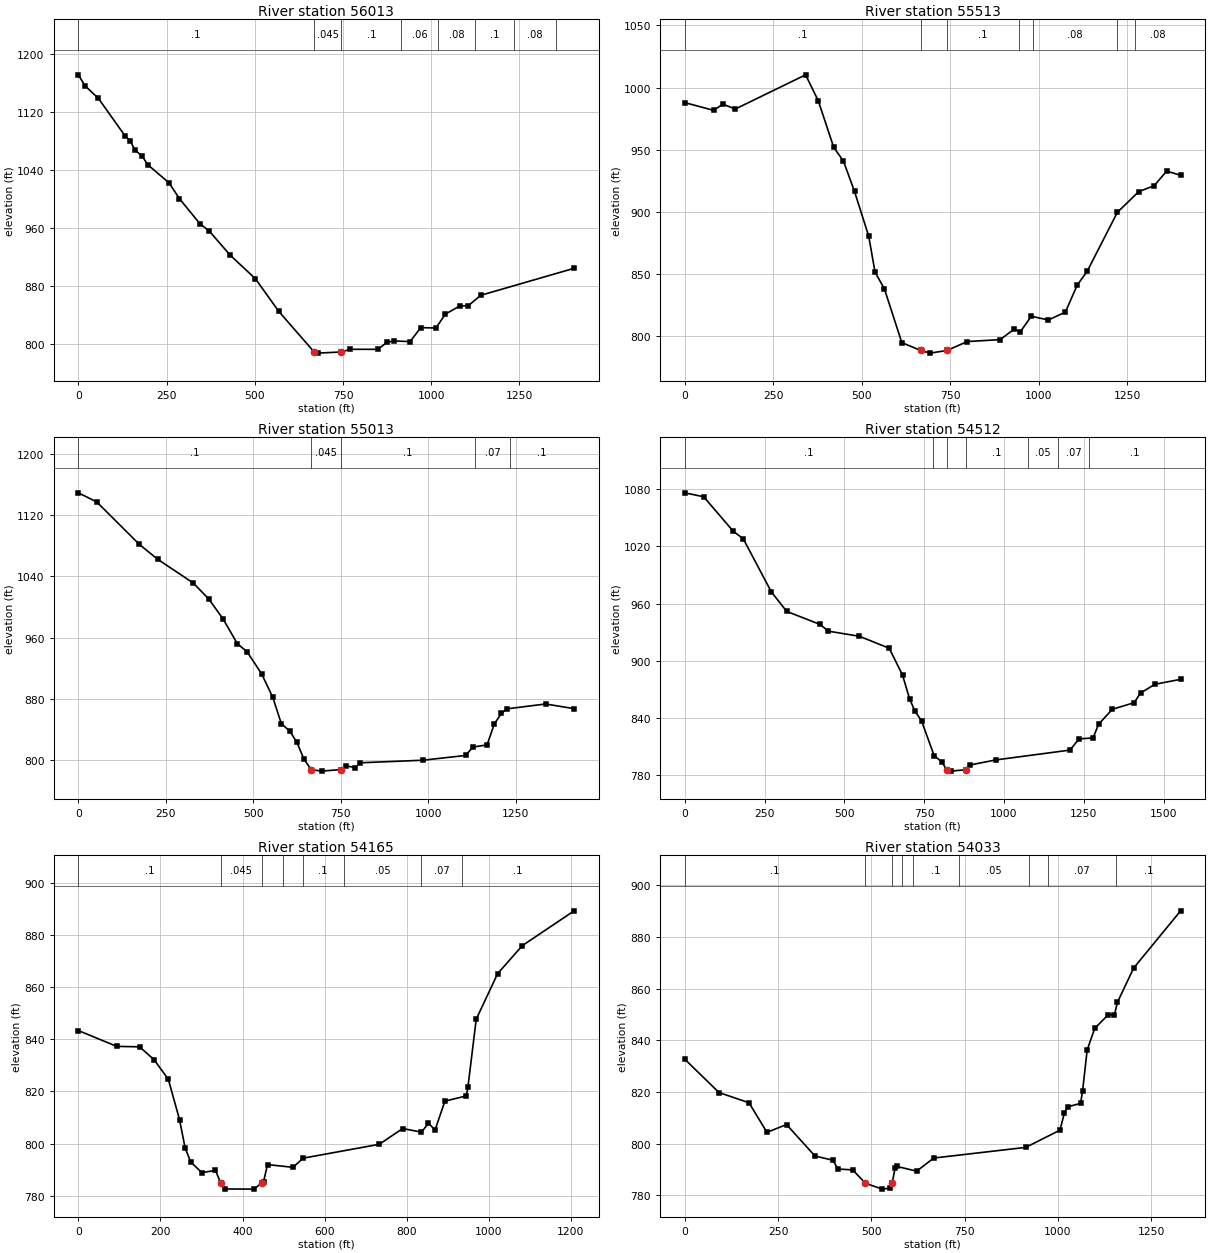
Type RM Length L Ch R = 1 ,56013   ,498,500,499.6
XS GIS Cut Line= 6
  1657187.246517369413.179122761 1657362.8701815369508.492252335
1657621.82570034369637.9588569251657767.98288834369709.391784921
1658365.16640526369968.0198765841658445.11309576370031.900326252
#Sta/Elev= 30
       0 1171.81    19.2 1156.59    56.9  1139.3   133.1 1087.08   146.8 1081.05
   160.4 1068.03   180.1 1060.08   196.7 1047.82   257.4  1022.6   286.3 1001.05
   344.4  966.42   370.7  956.49   429.3  923.51   501.9  890.39   567.9  845.52
  668.15789.4391   678.4  787.83  745.73789.4401   769.9   793.1     849  793.07
   874.7  802.74   894.6  804.67     940  803.72   970.5  823.02  1013.3  822.48
  1040.2  841.68  1080.3  852.68  1105.6  853.45  1140.4  867.61  1405.1  904.89
#Mann= 8 ,-1,0
       0      .1       0  668.15    .045       0  745.73      .1       0
  914.52     .06       0 1018.27     .08       0 1125.15      .1       0
 1233.58     .08       0  1352.8      .1       0
Bank Sta=668.15,745.73
XS Rating Curve= 0 ,0
Exp/Cntr(USF)=0,0
Exp/Cntr=0.3,0.1

Type RM Length L Ch R = 1 ,55513   ,505.4,499.2,489
XS GIS Cut Line= 6
1656956.95301434369873.5348293331657140.18854025369952.475616336
1657229.21362467369994.7311092621657546.08142926370150.907634169
1657636.66490951370193.2776281681658227.91274276370464.264290929
#Sta/Elev= 30
       0  987.84    81.6  981.62   107.7   986.6   142.7  982.67   341.5 1010.24
   377.2  989.42     421  951.83   448.6  940.67   479.8  916.25   519.9   880.3
   537.8  851.24   564.4  837.71   613.5   794.5  667.04788.1702   693.2  786.03
  741.25788.1708   798.6  795.37   891.5  796.89   931.1  805.38   948.7  803.28
   979.5  815.75  1027.9  812.72    1076  819.12  1109.1  840.67  1137.9  852.16
  1222.9  899.46  1283.1  916.11  1327.1  920.94  1362.3  932.68  1401.7  929.28
#Mann= 7 ,-1,0
       0      .1       0  667.04    .045       0  741.25      .1       0
  943.83     .07       0  983.83     .08       0  1222.9      .1       0
  1272.9     .08       0
Bank Sta=667.04,741.25
XS Rating Curve= 0 ,0
Exp/Cntr(USF)=0,0
Exp/Cntr=0.3,0.1

Type RM Length L Ch R = 1 ,55013   ,512.5,501.2,486.2
XS GIS Cut Line= 6
1656696.56245901370504.4328457561657337.86596642370613.936235666
1657509.22520375370653.8544629221657597.35888575370668.097216591
1657888.60469434370727.5035938321658088.32214268370764.955290586
#Sta/Elev= 30
       0 1149.48    52.3 1137.66     174 1082.12   226.8 1062.44   328.2 1031.47
   372.9 1010.34   413.5  984.32     454   952.2   482.4  941.21   523.5  912.53
   555.5  881.76   579.8  847.35   604.2  837.61   624.5   822.7   644.4  801.08
  665.02787.2895   694.7  785.22  750.76787.2934   764.1  792.13   790.8  789.91
     805  796.14   983.8  799.48  1106.4  805.73  1126.8  816.68  1167.6  819.52
  1188.1  846.82  1208.5   860.9  1224.8  866.76  1334.7  873.11  1416.3  866.98
#Mann= 5 ,-1,0
       0      .1       0  665.02    .045       0  750.76      .1       0
 1131.98     .07       0 1233.08      .1       0
Bank Sta=665.02,750.76
XS Rating Curve= 0 ,0
Exp/Cntr(USF)=0,0
Exp/Cntr=0.3,0.1

Type RM Length L Ch R = 1 ,54512   ,369.6,347,316.7
BEGIN DESCRIPTION:
Structure 18 XS 4
END DESCRIPTION:
XS GIS Cut Line= 6
1656686.90237334370841.2602560821656789.97500184370978.300008252
    1656891.4164371096.0418987571656994.29939634371163.437761337
1657797.11537601371089.102608174  1658093.114784 371061.69551076
#Sta/Elev= 30
       0 1076.37    59.2 1072.22   151.7 1036.02   183.1 1028.11     271   972.3
   319.2  951.73   423.4  938.09   449.9  930.93   546.8  925.61   640.5  912.99
   682.2  884.73   704.2  859.81   720.9  847.01   741.7  836.69   781.1  800.13
   805.2  793.44  820.43785.3366   833.8  783.82  881.45785.3352   893.6   790.3
   975.5  795.65  1206.9  805.94    1235  817.72  1279.2  818.69  1296.2  833.06
  1339.5  848.83  1407.8  855.75  1427.9  865.94  1472.7   875.1  1553.4  880.32
#Mann= 7 ,-1,0
       0      .1       0  778.01    .025       0  820.43    .045       0
  881.45      .1       0 1075.51     .05       0 1169.26     .07       0
 1266.13      .1       0
Bank Sta=820.43,881.45
XS Rating Curve= 0 ,0
Exp/Cntr(USF)=0,0
Exp/Cntr=0.3,0.1

Type RM Length L Ch R = 1 ,54165   ,130.1,132.2,146.9
BEGIN DESCRIPTION:
Structure 18 XS 3
END DESCRIPTION:
XS GIS Cut Line= 6
1657120.61563583371415.3114090291657271.64977805371560.536545779
1657521.43701326371400.7888953531657634.71261993371267.181769543
1657710.22969104371133.5746437321658082.00604112371104.529616382
#Sta/Elev= 30
       0  843.33    93.6  837.26   149.1  837.09   184.4  832.18   219.2  824.66
   246.5   809.2   260.2  798.29   273.8  792.92   301.2  788.82   334.1  789.73
  346.71784.9291   358.5  782.58   428.1  782.52  446.96784.9316   451.2  785.35
   460.9  791.93     523  790.88   547.7  794.39   733.2  799.71   790.3  805.76
     836  804.36     853  807.81   869.1   805.2   893.1  816.27   945.3  818.26
   949.2  821.67   969.4  847.68  1021.5  865.14  1081.7   875.9    1208  889.24
#Mann= 8 ,-1,0
       0      .1       0  346.71    .045       0  446.96    .025       0
  498.71     .05       0  546.45      .1       0  646.45     .05       0
  835.08     .07       0  935.08      .1       0
Bank Sta=346.71,446.96
XS Rating Curve= 0 ,0
Exp/Cntr(USF)=0,0
Exp/Cntr=0.3,0.1

Type RM Length L Ch R = 1 ,54033   ,342.9,395.4,433.2
BEGIN DESCRIPTION:
Structure 18 XS 2
END DESCRIPTION:
XS GIS Cut Line= 6
 1657068.3345866371435.6429281741657262.93626985371691.239168855
1657535.95952694371537.3005238991657660.85314455371397.884392618
1657750.89272933371249.7547531321658079.10153839371194.569201167
#Sta/Elev= 30
       0   832.7    91.6  819.82   172.1  815.86   220.3   804.4   272.6  807.44
   348.9  795.27   397.2  793.62   410.4  790.22     450   789.9  484.15784.7067
   529.5  782.45   549.7  782.83  555.54784.7097   563.9   790.7   568.7  791.23
   621.4   789.4   667.4  794.48   913.8   798.6  1005.5  805.25  1017.7  811.99
  1025.8  814.27  1060.8  815.62  1066.3  820.52  1078.5  836.28  1098.8  844.65
  1135.3  849.97  1151.5  849.84  1159.6  854.72  1203.1  867.97    1329  890.11
#Mann= 9 ,-1,0
       0      .1       0  484.15    .045       0  555.54      .1       0
  581.63    .025       0  611.63      .1       0  735.63     .05       0
  922.81     .06       0  972.81     .07       0 1156.16      .1       0
Bank Sta=484.15,555.54
XS Rating Curve= 0 ,0
Exp/Cntr(USF)=0,0
Exp/Cntr=0.3,0.1

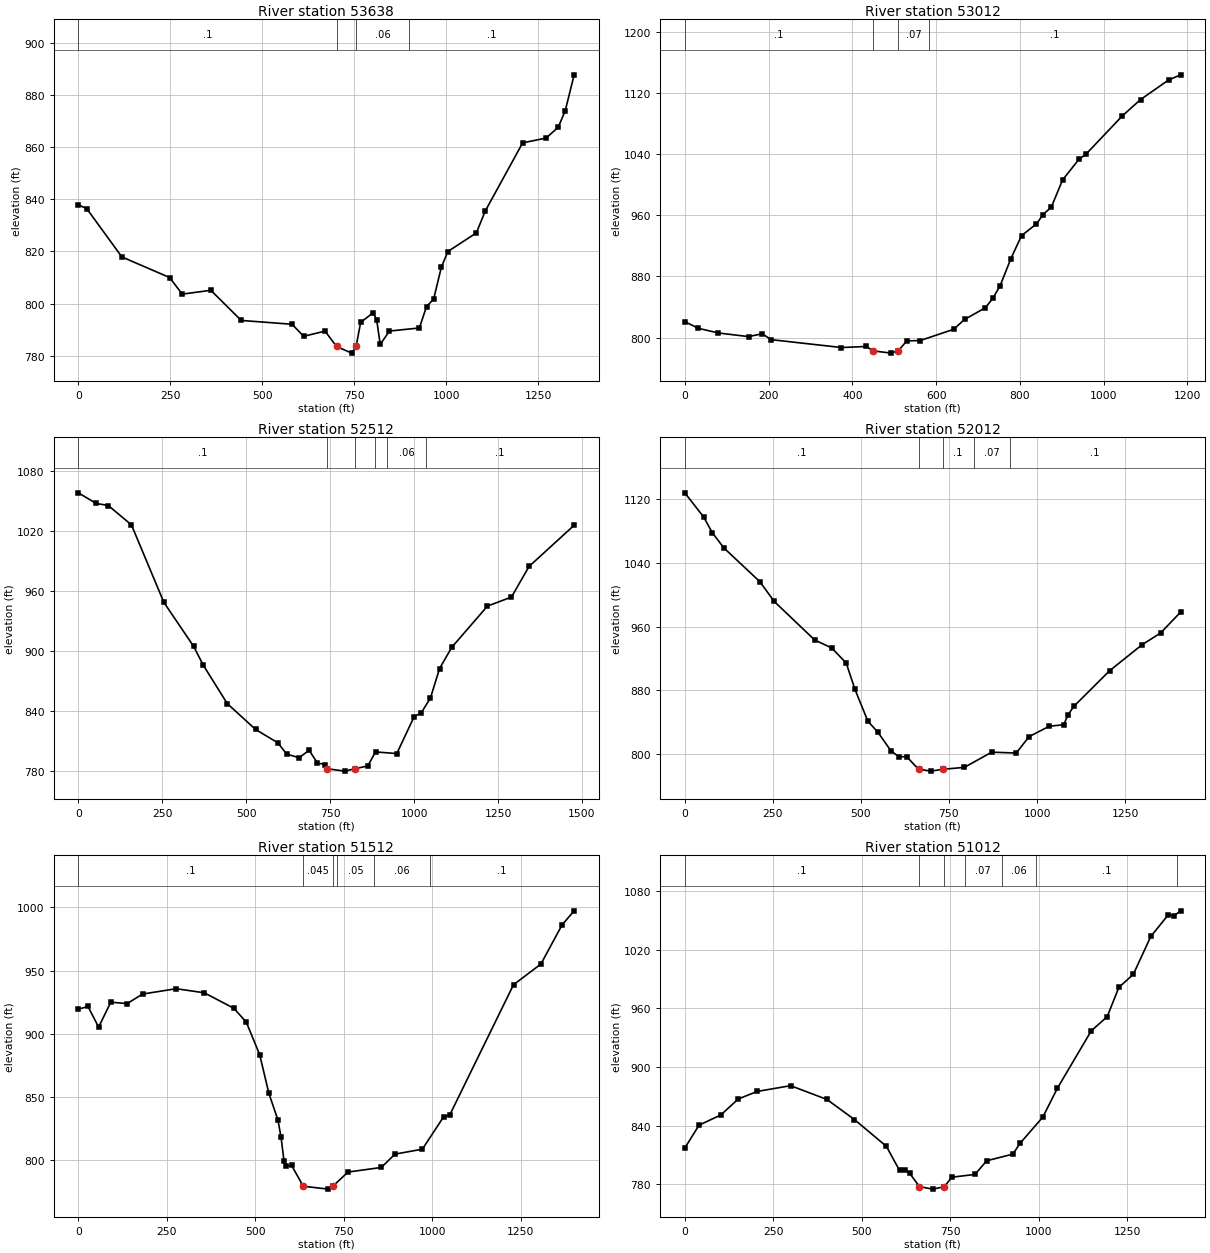
Type RM Length L Ch R = 1 ,53638   ,585.7,625.4,656.7
BEGIN DESCRIPTION:
Structure 18 XS 1
END DESCRIPTION:
XS GIS Cut Line= 3
1656990.02112033371390.5998183471657220.65327453371691.511294322
1657765.95114711372492.340140399
#Sta/Elev= 30
       0  837.83    22.6  836.45   118.4   817.9   248.2  810.01   282.5  803.66
   360.3  805.12   442.8  793.57     581  792.11   612.7   787.5   670.7  789.48
  701.94783.5958   743.3  781.05  755.18783.5931   767.5  792.82   801.4  796.52
   811.1  793.84   820.7   784.4   845.9  789.51   927.2  790.69   946.6  798.91
   965.9  801.72   986.9  813.95  1004.6  819.98  1082.1   827.1  1106.3   835.5
  1207.9  861.59  1271.9  863.46  1304.7   867.6  1323.8  873.94    1348  887.67
#Mann= 4 ,-1,0
       0      .1       0  701.94    .045       0  755.18     .06       0
  899.13      .1       0
Bank Sta=701.94,755.18
XS Rating Curve= 0 ,0
Exp/Cntr(USF)=0,0
Exp/Cntr=0.3,0.1

Type RM Length L Ch R = 1 ,53012   ,503.7,500,487.7
XS GIS Cut Line= 6
1656992.12326245371448.3549803541656994.27610242371618.668150082
1656960.70530343371713.3953228441656909.54005143371784.459813252
1656864.56966892371844.5013598351656402.59782384372435.828917339
#Sta/Elev= 30
       0  820.75    32.2  812.06    80.2  805.92   152.2   801.2     185   804.9
   206.3  797.21   374.1  786.93   433.8  788.29  448.71782.6432   492.6   779.6
  509.89782.6462   529.9  795.62     562  796.03   641.6  810.69   668.1  823.65
   717.7  838.94   735.8  851.56   752.9  867.81   778.6  903.21     804  933.22
   839.5  948.51   855.5  960.79   875.1  970.51     902 1006.05   940.9 1032.94
   958.1 1039.85  1044.9 1089.92  1088.3 1111.18  1155.3 1136.75  1183.8 1143.44
#Mann= 4 ,-1,0
       0      .1       0  448.71    .045       0  509.89     .07       0
  583.41      .1       0
Bank Sta=448.71,509.89
XS Rating Curve= 0 ,0
Exp/Cntr(USF)=0,0
Exp/Cntr=0.3,0.1

Type RM Length L Ch R = 1 ,52512   ,509.8,500,489
XS GIS Cut Line= 6
1656643.16689651370842.5929305851656702.50470434370980.965029165
1656716.47547692371101.3719405831656285.58919959371896.857226253
1656232.77664118371980.2012196781656107.86219284372138.662188843
#Sta/Elev= 30
       0 1058.58    53.1 1047.96    89.2 1045.86   158.2 1026.46   254.8  948.75
   343.6  904.59   371.8  885.97   443.7  847.25   528.1  821.32   593.8  808.06
   621.1  796.58   657.5  793.04   687.5  800.47   712.1  787.71   734.7  786.21
  742.13781.8949   793.7  779.57  822.66 781.894   862.2  784.76   885.2  798.84
   948.6  797.16  1000.3   834.2  1021.4  838.02  1048.7  852.75    1076  882.45
  1112.4  903.72  1218.7  945.04  1290.1  954.08  1342.6  984.78  1476.9 1026.08
#Mann= 6 ,-1,0
       0      .1       0  742.13    .045       0  822.66     .06       0
  883.34      .1       0  918.34     .06       0 1035.84      .1       0
Bank Sta=742.13,822.66
XS Rating Curve= 0 ,0
Exp/Cntr(USF)=0,0
Exp/Cntr=0.3,0.1

Type RM Length L Ch R = 1 ,52012   ,526,500,483.7
XS GIS Cut Line= 6
1656160.22396475370672.0437310041656004.92506276371406.188260093
1655931.84253176371751.6682121751655911.47085334371847.974450007
1655905.30387092371949.364995256 1655905.3478341372053.577057168
#Sta/Elev= 30
       0 1127.95    53.7 1097.55    78.2 1077.85   110.9 1058.82   213.1 1016.43
     254  991.57   368.5  943.35   417.5  933.15   458.4  914.21   482.9  881.52
   519.7  841.35   548.4  827.39   585.2  804.18   607.9   796.7   630.1  796.82
  663.58780.9686   699.6  778.68   731.7780.9695   793.7  783.38   871.4  802.48
   940.9  801.37   977.7  822.03  1034.9  835.06  1075.8  836.86    1088   849.2
    1104   859.8  1206.5  904.85  1298.7  937.45  1350.7  951.99  1407.7  978.24
#Mann= 5 ,-1,0
       0      .1       0  663.58    .045       0   731.7      .1       0
  820.39     .07       0  922.89      .1       0
Bank Sta=663.58,731.7
XS Rating Curve= 0 ,0
Exp/Cntr(USF)=0,0
Exp/Cntr=0.3,0.1

Type RM Length L Ch R = 1 ,51512   ,492.5,500,503.6
XS GIS Cut Line= 6
1655282.77558842 370791.127482341655355.05759609370976.351521343
1655582.83962084371560.0432673391655683.94899867371819.138549671
1655755.80548225372003.2707273361655792.01735209 372096.06483309
#Sta/Elev= 30
       0  919.48    27.3   921.6    57.3  905.24    91.7     925     138   923.9
   181.3  931.43   276.3  935.68   355.8  932.46   439.5  920.14   474.7  909.12
   512.5  883.28   538.2  852.95     564  831.59   572.6  818.25   581.2  799.03
   585.5  795.22   602.6  795.68  635.51779.2604   705.7  776.96  719.03779.2614
   761.9  790.47     856  794.13   894.6  804.68   971.9  808.59    1032  834.23
  1049.4  835.72  1229.5  938.86  1306.8  955.19  1366.9  986.33  1400.8  997.36
#Mann= 6 ,-1,0
       0      .1       0  635.51    .045       0  719.03      .1       0
  730.39     .05       0  835.39     .06       0  992.89      .1       0
Bank Sta=635.51,719.03
XS Rating Curve= 0 ,0
Exp/Cntr(USF)=0,0
Exp/Cntr=0.3,0.1

Type RM Length L Ch R = 1 ,51012   ,507.6,500,493.2
XS GIS Cut Line= 6
1654902.15266201370901.2771964221654990.19316834371285.459170833
1655011.13505559371376.840221673 1655069.7707651371632.707492083
1655127.01113617371882.4825830911655215.05164251372266.664557502
#Sta/Elev= 30
       0  817.22    40.3  840.58   101.8  851.05   151.1  867.33   204.4  875.04
   298.8  880.93   401.4  866.88   479.4  846.31   569.7  818.88   606.6  794.36
     623  794.73   635.3  791.41  663.07777.7714     701  775.25  733.25777.7703
   754.3  787.41     820  790.28   852.8  804.23   926.7  810.98   947.2  822.03
  1011.6  848.92  1052.7  878.37  1148.3  936.92  1193.4  951.47  1226.2  981.28
  1267.3  994.77  1316.5 1033.36  1365.8 1055.42  1382.2 1054.51  1400.8 1059.56
#Mann= 7 ,-1,0
       0      .1       0  663.07    .045       0  733.25     .06       0
  790.39     .07       0  895.39     .06       0  992.89      .1       0
 1391.17     .05       0
Bank Sta=663.07,733.25
XS Rating Curve= 0 ,0
Exp/Cntr(USF)=0,0
Exp/Cntr=0.3,0.1

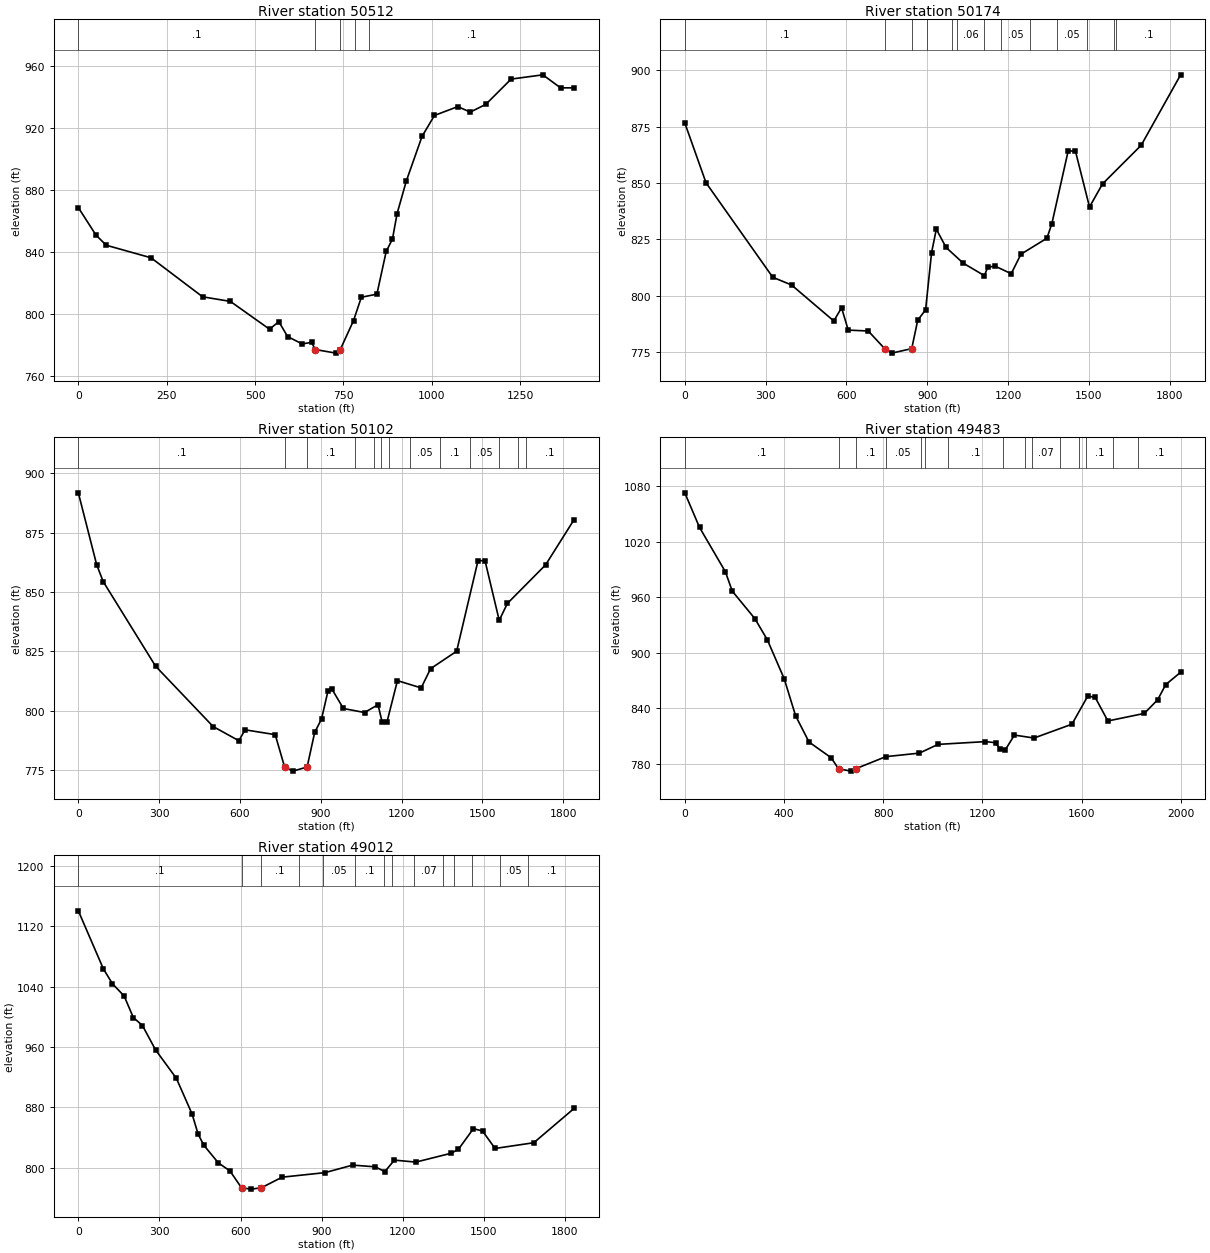
Type RM Length L Ch R = 1 ,50512   ,305.8,337.9,403.1
XS GIS Cut Line= 6
1654315.51538384 371157.851486431654357.01661317371249.531093091
1654399.60412642371339.7343247531654441.85502617371428.827650502
  1654482.299171371516.8560177531654902.57293676372431.566458672
#Sta/Elev= 30
       0  868.49    49.9  850.77      79  844.24   205.7  836.15   351.5  811.03
   430.2  808.05   540.8  790.16   567.2  795.02   591.8  785.44   633.2  780.67
   659.6  781.71  670.28777.0594   728.8  774.75     741777.0604   778.5  795.75
   800.5  810.74   844.5  812.73   870.9   840.3   888.5  848.19   901.7  864.66
   927.8  885.66   972.2  914.35  1007.4  927.84  1073.4  933.54  1108.6  929.99
  1152.7  935.01  1224.2  951.25  1313.9     954    1364  945.62  1402.5  945.61
#Mann= 5 ,-1,0
       0      .1       0  670.28    .045       0     741      .1       0
  782.12     .06       0  822.12      .1       0
Bank Sta=670.28,741
XS Rating Curve= 0 ,0
Exp/Cntr(USF)=0,0
Exp/Cntr=0.3,0.1

Type RM Length L Ch R = 1 ,50174   ,74.6,72,64.5
XS GIS Cut Line= 6
1654259.90087753371176.1607897371654409.28219507 371768.70668266
1654308.83501909371838.3915666141654210.73963476371948.640361401
1654116.98475415372160.4569435111654780.28226211372461.018129662
#Sta/Elev= 30
       0  876.64    78.8  850.12   326.6  808.23   396.4  804.81   553.2  788.86
     582  794.72   606.8  784.81     681  784.42  741.99776.6086   768.3  774.61
  842.51776.6074   864.7  789.17     894  793.83   916.1   819.1   933.8  829.54
     970  821.46  1033.6  814.49  1112.6  808.93  1124.1  812.62  1151.2  813.22
  1211.8  809.81    1248  818.46  1344.4  825.54  1362.9  832.06  1423.5  864.33
  1450.5  864.03  1502.5  839.39  1550.8  849.61  1694.3  866.73  1840.8  897.96
#Mann= 13 ,-1,0
       0      .1       0  741.99    .045       0  842.51      .1       0
  900.91     .07       0  990.91      .1       0 1010.91     .06       0
 1112.62     .07       0 1172.62     .05       0 1282.62      .1       0
 1382.62     .05       0 1492.62      .1       0 1592.62     .05       0
 1602.62      .1       0
Bank Sta=741.99,842.51
XS Rating Curve= 0 ,0
Exp/Cntr(USF)=0,0
Exp/Cntr=0.3,0.1

Type RM Length L Ch R = 1 ,50102   ,651.6,618.9,561.8
XS GIS Cut Line= 6
1654201.14678646371158.661637934  1654350.528104371751.207530857
1654250.08092802371820.8924148111654151.98554368371931.141209598
1654058.23066308372142.9577917081654721.52817104372443.518977859
#Sta/Elev= 30
       0  891.73    67.9  861.54    92.3  854.38   286.6  818.81   500.4  793.39
     596  787.41   618.9  792.01   730.9  789.97  765.86776.3577   796.8  774.62
  849.42776.3561   877.4  790.89   902.9  796.57   926.6  808.22     942  809.03
   984.1  800.98  1062.5  799.28  1112.6  802.56  1127.9  795.29  1145.4  795.09
  1184.7   812.7  1272.8  809.64  1307.9  817.74  1404.5  825.07  1483.9  863.21
  1509.9  863.15  1562.6  838.05  1592.7  845.16  1734.8  861.42  1840.8   880.5
#Mann= 13 ,-1,0
       0      .1       0  765.86    .045       0  849.42      .1       0
 1026.06     .06       0 1096.06      .1       0 1122.62     .06       0
 1152.62     .07       0 1232.62     .05       0 1342.62      .1       0
 1452.62     .05       0 1562.62      .1       0 1632.62     .05       0
 1662.62      .1       0
Bank Sta=765.86,849.42
XS Rating Curve= 0 ,0
Exp/Cntr(USF)=0,0
Exp/Cntr=0.3,0.1

Type RM Length L Ch R = 1 ,49483   ,524.4,471.1,408
XS GIS Cut Line= 6
1653286.58060367371256.3987708851653697.28857941372012.347446928
1653966.86253785372150.5453671661654327.85131717372353.010841504
1654525.72428101 372425.637664751654730.14775668372476.061448425
#Sta/Elev= 30
       0 1072.65    59.3 1035.33   163.5  987.49   191.4   966.5   282.4  936.84
   332.5  914.09   400.8  871.84   446.6  831.97   500.9  803.54   589.7  786.68
  619.77 774.687   669.3  772.16  688.57774.6864   810.5  787.79   945.8   791.6
  1020.8  801.04  1211.6  804.02  1253.8  802.84  1270.4  795.52  1291.3  794.84
  1328.8  811.09  1407.9  807.89  1560.7  822.84  1624.6  853.23  1654.4  851.78
  1705.5  826.32  1852.5  834.47    1906  849.15    1939  865.66  1998.8  878.85
#Mann= 15 ,-1,0
       0      .1       0  619.77    .045       0  688.57      .1       0
     810     .05       0  950.31      .1       0  970.31     .06       0
 1060.31      .1       0 1283.25     .07       0 1371.06      .1       0
 1401.06     .07       0 1511.06      .1       0 1587.43     .05       0
 1617.43      .1       0 1727.43     .05       0 1828.21      .1       0
Bank Sta=619.77,688.57
XS Rating Curve= 0 ,0
Exp/Cntr(USF)=0,0
Exp/Cntr=0.3,0.1

Type RM Length L Ch R = 1 ,49012   ,500,500,499.7
XS GIS Cut Line= 6
1653087.53701145372584.2707065391653733.62678385372157.720221594
1653833.42185985372149.6769305911654330.95596975372366.599725083
1654527.27677134372432.4322705861654730.92400184372479.458423257
#Sta/Elev= 30
       0 1140.69    92.4 1063.92   126.1 1044.06   169.6 1027.66   203.4  999.22
   237.2  988.62   285.5  956.43   362.6  918.63   420.6   871.5   443.3  844.44
   464.1  829.96   518.2   806.4   560.6  795.92  603.84773.4363   639.2  771.71
  676.71773.4347   753.7  787.54   912.1  793.56  1014.7  803.55  1098.3  801.28
  1133.7  794.93  1169.1  810.16  1248.5  807.55  1379.9  819.35  1406.2  824.63
  1461.4  851.89  1495.2  848.73  1541.6  825.62  1684.8  833.23  1834.1  878.76
#Mann= 14 ,-1,0
       0      .1       0  603.84    .045       0  676.71      .1       0
  814.85     .06       0  904.97     .05       0 1024.97      .1       0
 1130.94     .07       0 1160.94      .1       0 1240.34     .07       0
 1350.34      .1       0 1390.34     .05       0 1458.03      .1       0
 1558.03     .05       0  1665.1      .1       0
Bank Sta=603.84,676.71
XS Rating Curve= 0 ,0
Exp/Cntr(USF)=0,0
Exp/Cntr=0.3,0.1