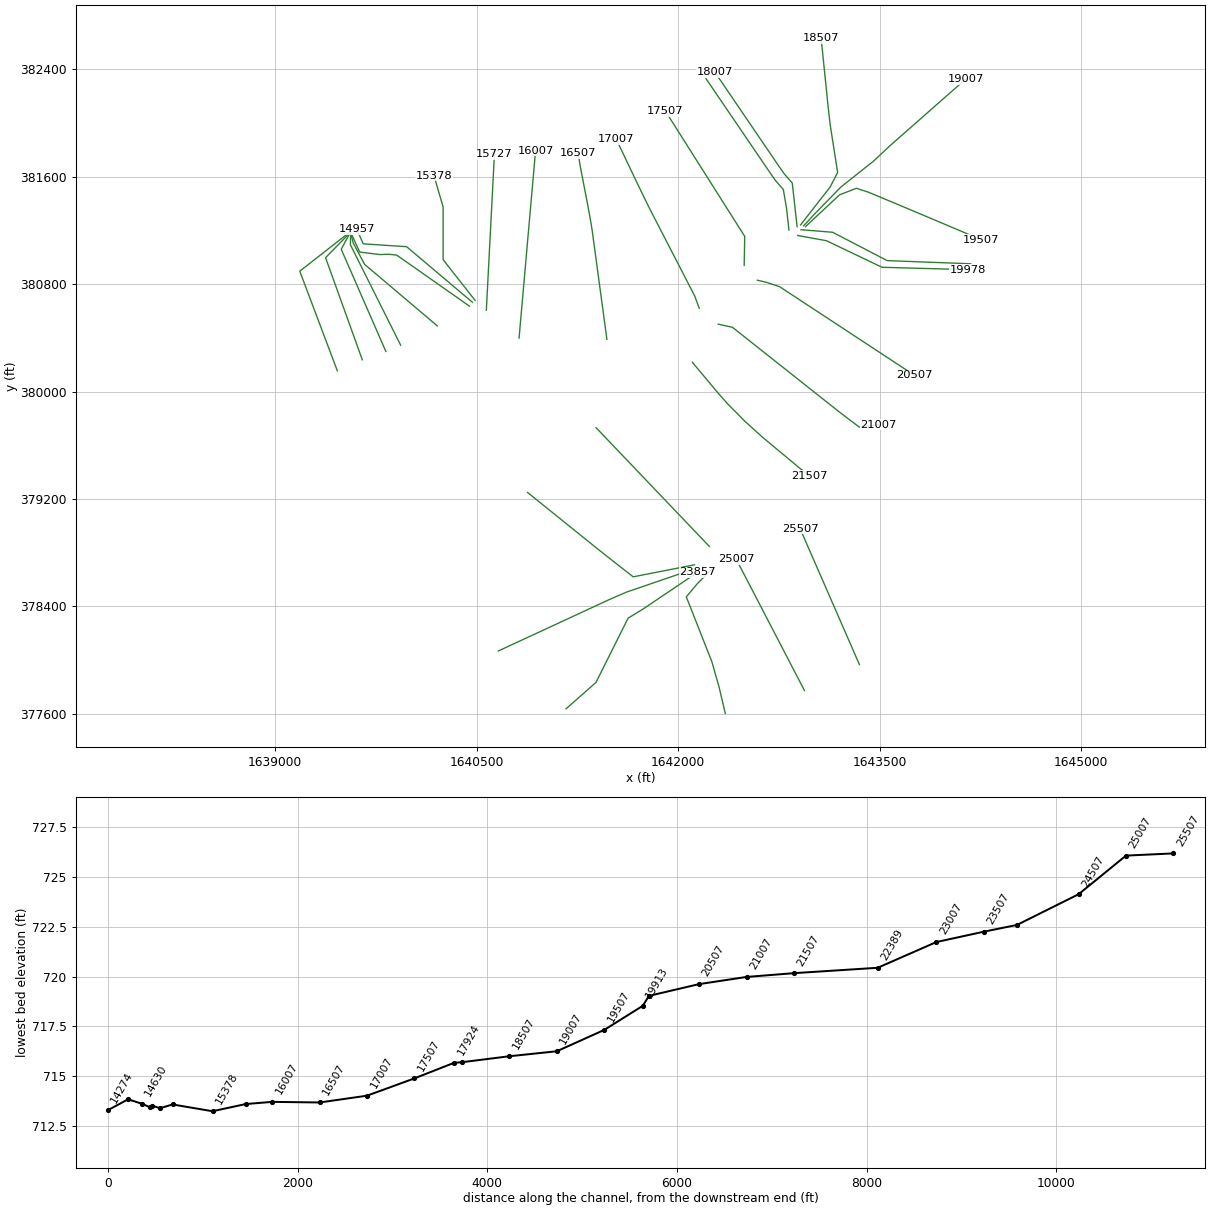
HEC-RAS study SFFSHGCK.prj: SFFSHGCK

--- SFFSHGCK.g01 (geometry) --- (continued)

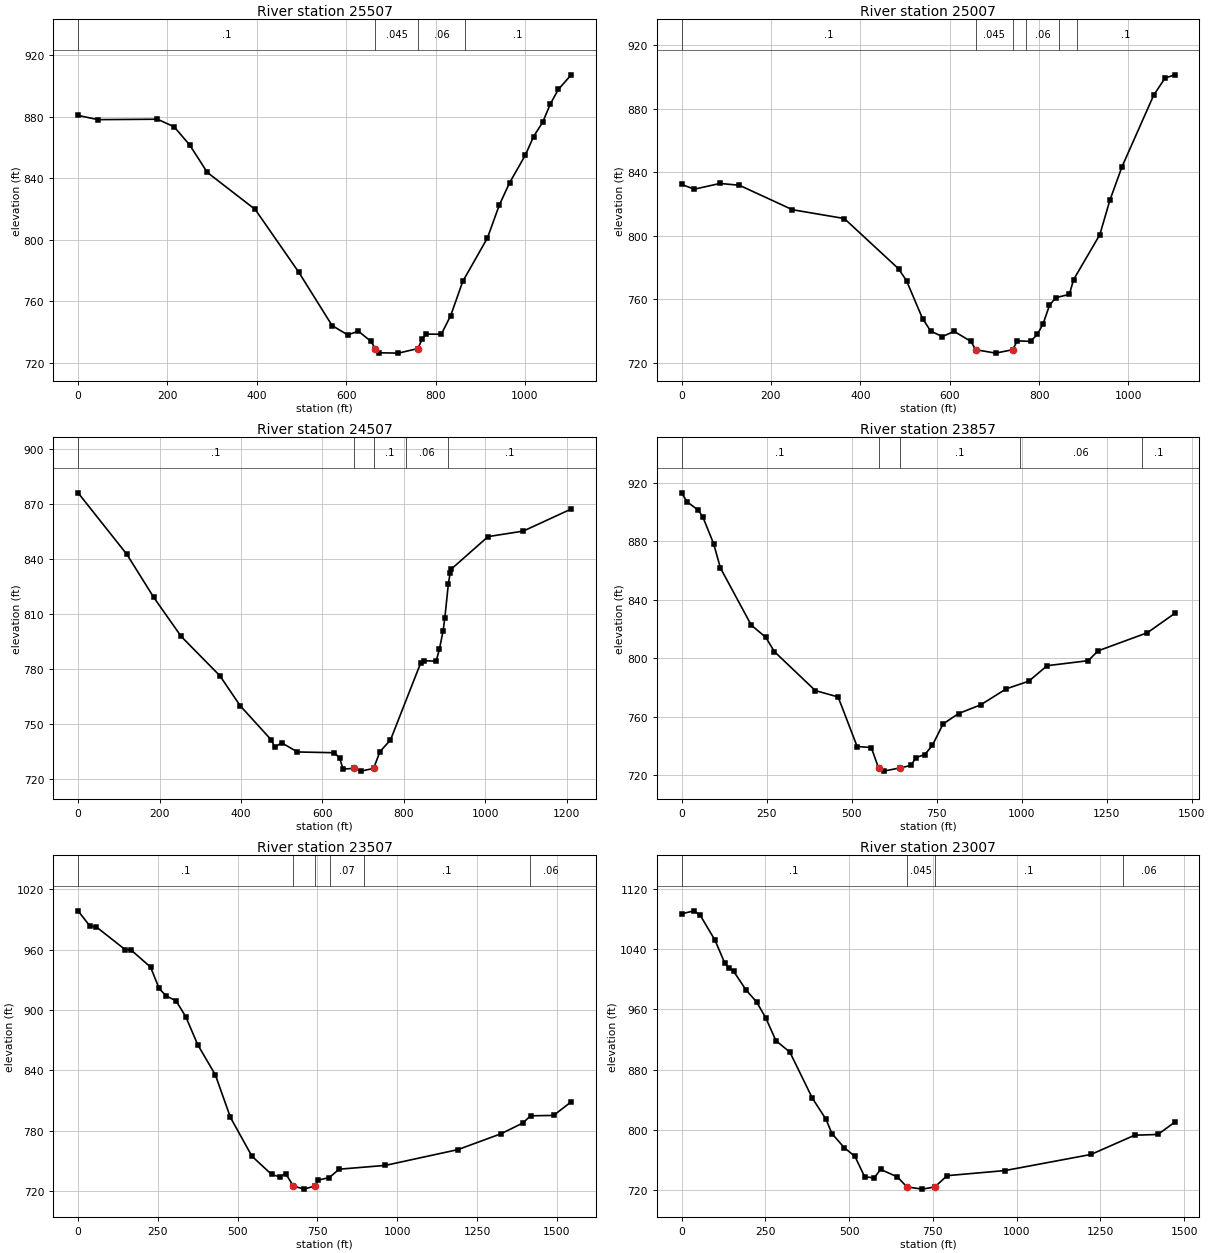
Type RM Length L Ch R = 1 ,25507   ,497.4,500,503.8
XS GIS Cut Line= 6
1643348.86441693377967.5281557591643309.04723933378058.833419338
1643269.38590135378149.7800878441643088.88134108378563.696582839
1642983.95077667378804.3122433421642907.75178209 378979.04516159
#Sta/Elev= 30
       0  880.81    44.7  878.09   177.6  878.36   214.9  873.44   249.8  861.59
   289.1  843.77   396.4  819.64   494.2  778.67   568.4  744.13   603.3  738.04
   627.3  740.45   655.7  733.75  664.88 729.144   673.1  726.41   716.8  726.18
  760.31 729.144   770.1  735.41   779.2  738.58   812.8  738.44   833.9  750.66
   860.8  772.83     916  801.07   942.5  822.43   965.5  836.95  1001.1  855.11
  1019.3  867.11  1039.7  876.42  1057.1  888.48  1074.6   897.7  1103.5  907.24
#Mann= 4 ,-1,0
       0      .1       0  664.88    .045       0  760.31     .06       0
  865.39      .1       0
Bank Sta=664.88,760.31
XS Rating Curve= 0 ,0
Exp/Cntr(USF)=0,0
Exp/Cntr=0.3,0.1

Type RM Length L Ch R = 1 ,25007   ,506.2,500,492.5
XS GIS Cut Line= 6
 1642939.8147101377773.8431756791642893.92995934377862.254744262
1642715.06975275378206.8872570841642594.15037517378439.877932832
1642559.60221593378506.4466973391642431.48469001378753.306111753
#Sta/Elev= 30
       0   832.3    28.5  829.32    86.2  832.93   129.4  831.77     248  816.39
   364.1  810.83   485.4  779.23   503.3  771.68   539.3  747.79   557.3  740.03
   583.3  736.48     610  739.77   647.5  733.42  658.13 728.231   702.7  726.07
  740.87 728.229   751.1   733.8   780.9  733.46   796.2  737.92   808.8  744.42
   823.2  756.12   836.8  760.95   867.7  763.06   877.3  772.43   935.9  800.65
   958.4  822.36   985.5  843.41  1056.3   888.4  1081.7  899.26  1103.5  901.33
#Mann= 6 ,-1,0
       0      .1       0  658.13    .045       0  740.87      .1       0
  770.39     .06       0  845.39     .07       0  885.39      .1       0
Bank Sta=658.13,740.87
XS Rating Curve= 0 ,0
Exp/Cntr(USF)=0,0
Exp/Cntr=0.3,0.1

Type RM Length L Ch R = 1 ,24507   ,671,649.2,617.8
XS GIS Cut Line= 6
1642350.53636108377603.7864291671642304.32647976377799.796207756
1642250.63006485377988.8699765951642060.52250542378471.537646428
1642145.65712954378573.5761502331642260.53053934 378686.61709418
#Sta/Elev= 30
       0  875.99   119.8  842.42   185.6     819   253.2  797.62   348.3  776.14
     398  759.81   474.5  741.13   482.8  737.21   499.9  739.57   538.7  734.59
   629.2  734.17   642.1  731.31   650.7  725.24   676.6  725.62   693.8  724.13
  725.58   725.6   741.2  734.77   767.1  741.13   840.9  782.96   848.9   784.4
   879.1  784.12   887.1  790.58   896.3  800.72   900.6  807.95   909.2  826.31
   913.5  832.18   916.8  834.47  1006.6   852.1  1093.1  855.11  1210.8  867.16
#Mann= 5 ,-1,0
       0      .1       0   676.6    .045       0  725.58      .1       0
  804.25     .06       0  909.25      .1       0
Bank Sta=676.6,725.58
XS Rating Curve= 0 ,0
Exp/Cntr(USF)=0,0
Exp/Cntr=0.3,0.1

Type RM Length L Ch R = 1 ,23857   ,368.3,350.8,323.2
XS GIS Cut Line= 5
1641165.57444683377637.8438570791641388.33882836377834.532891608
1641627.17002568378312.8145386731641740.89783359378382.431846918
1642143.00066599378653.711735526
#Sta/Elev= 30
       0   913.2    16.2  907.03      49  901.34    62.1  896.89    94.1  878.47
   114.2  861.75   204.9  822.59   247.4  814.28   272.9  804.45   393.3  777.75
   460.4  773.39   516.2  739.45   557.9  738.76  579.14  724.83   594.5  722.59
   643.7  724.88     675  726.51   688.4   731.8   715.2  733.92   737.6  740.26
   768.9  754.89   814.4  762.01   879.8  768.01   954.8  778.97  1020.8  784.15
  1075.1  794.82  1195.8  798.23  1224.7  804.97  1369.7  817.38  1450.2  830.59
#Mann= 5 ,-1,0
       0      .1       0  579.14    .045       0   643.7      .1       0
  995.11     .06       0 1355.11      .1       0
Bank Sta=579.14,643.7
XS Rating Curve= 0 ,0
Exp/Cntr(USF)=0,0
Exp/Cntr=0.3,0.1

Type RM Length L Ch R = 1 ,23507   ,528.3,499.6,446.3
XS GIS Cut Line= 6
1640661.79006667378068.8035437611640842.18931217378152.402457923
1641019.39860342378234.5236847551641490.06629726378452.636765584
1641613.38133934378506.2091650071642084.35699514378667.927496019
#Sta/Elev= 30
       0  998.39    37.8  982.96    55.8  982.78     148  959.79   165.7  959.62
   227.2  942.56   253.9  921.38   275.9  913.98   306.8  909.17   337.6  893.26
     375  865.51   430.2  835.57   477.5  793.35   544.8  754.91   606.5  736.82
   631.2   734.5   650.4  737.72  674.25725.4744   707.9  722.25  743.47 725.476
     752  731.15   787.3  733.73     818  742.02   963.1  745.81    1190  761.43
  1324.9  777.12  1392.8   787.7  1418.2     795  1490.1  795.38  1545.3  808.88
#Mann= 6 ,-1,0
       0      .1       0  674.25    .045       0  743.47      .1       0
  790.39     .07       0  895.39      .1       0 1417.34     .06       0
Bank Sta=674.25,743.47
XS Rating Curve= 0 ,0
Exp/Cntr(USF)=0,0
Exp/Cntr=0.3,0.1

Type RM Length L Ch R = 1 ,23007   ,622.5,617.6,611.4
XS GIS Cut Line= 6
1640878.72762492379249.261484668 1641385.0008906378841.217353255
1641463.32783367378779.0406403391641522.25783393378732.575838253
1641665.09317817378620.7837390011642121.45845842378710.220724531
#Sta/Elev= 30
       0 1086.89    37.7 1090.83    55.6 1084.96    99.4 1052.12   128.6 1021.91
   140.5 1014.41   155.1 1010.84   192.1  985.97   224.3  969.74   251.8  948.27
   281.6  918.55     323  903.56     390  842.59   431.1  814.27   448.7  795.45
   485.1  776.83   517.5  765.07   546.4  738.07   574.8  736.68     594  747.84
     644  737.94  672.45724.6664   718.4  721.73  755.87724.6658   792.5  739.58
   964.8  746.34  1221.7  767.69  1352.1  793.24  1421.5  794.22  1471.7  810.51
#Mann= 4 ,-1,0
       0      .1       0  672.45    .045       0  755.87      .1       0
 1316.67     .06       0
Bank Sta=672.45,755.87
XS Rating Curve= 0 ,0
Exp/Cntr(USF)=0,0
Exp/Cntr=0.3,0.1

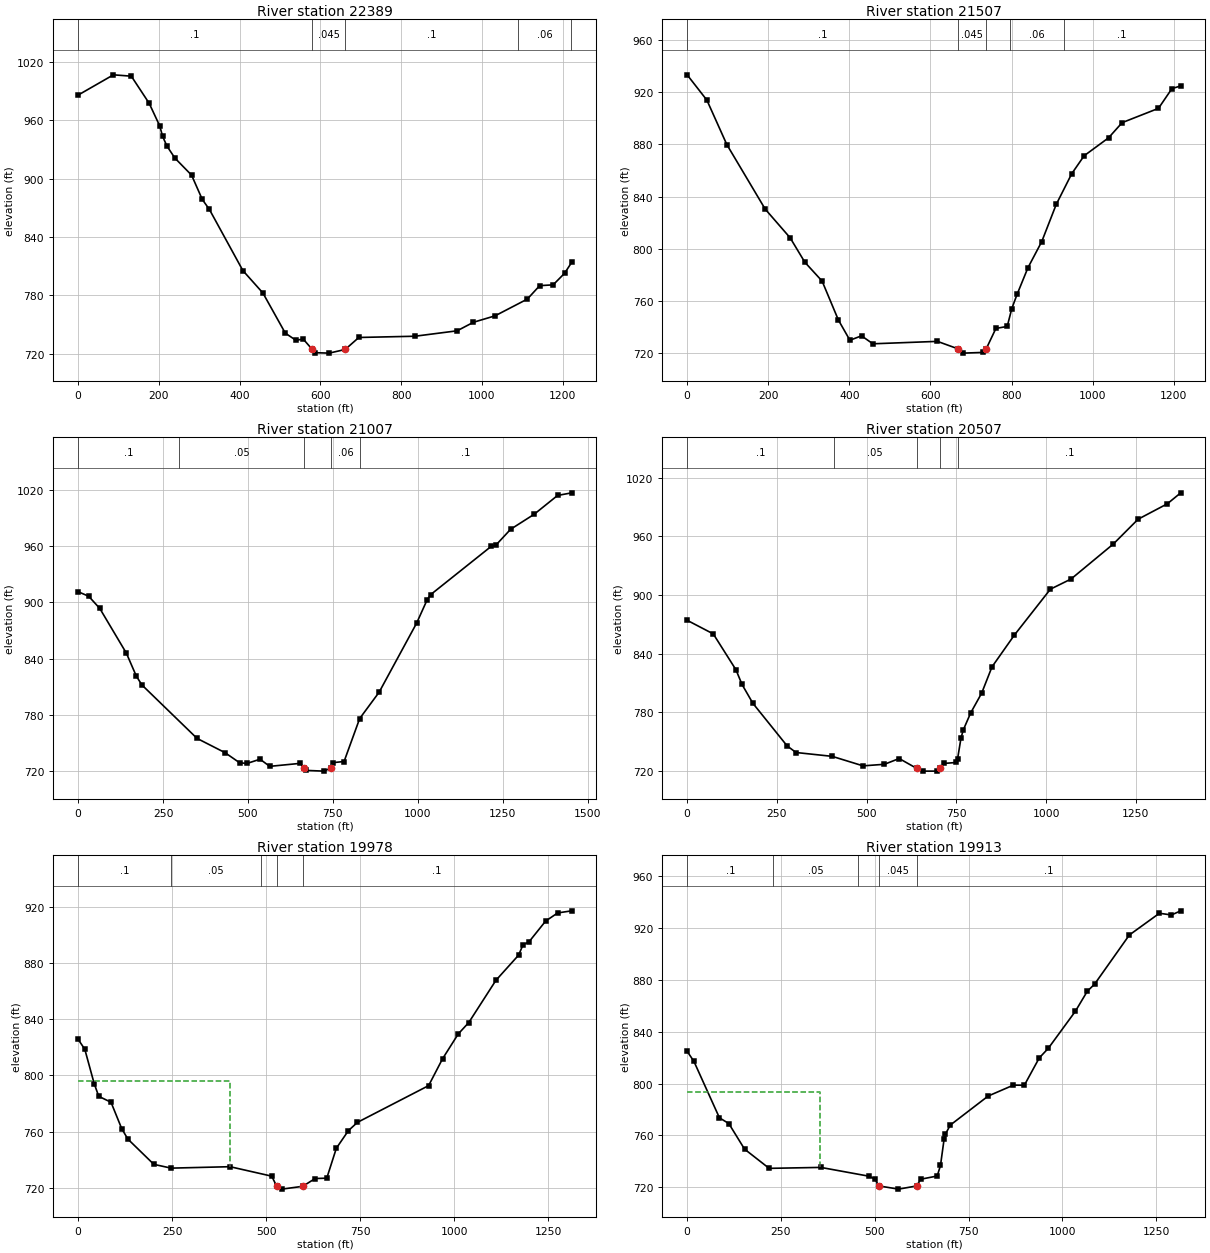
Type RM Length L Ch R = 1 ,22389   ,874.1,882,876.7
XS GIS Cut Line= 2
1641388.53745921379731.8971105031642231.95324895 378847.24765993
#Sta/Elev= 30
       0  985.93    87.5 1006.79   131.8  1005.4     176   977.5   202.3  954.11
   209.1  943.65   219.9  933.55   239.7  921.14     281  903.57   307.6  878.52
   325.2  868.24   408.1  805.36   457.6  782.35   513.1  741.02   539.6  733.58
   557.3     735  579.95724.1923   587.7  720.87   621.7  720.44  661.34724.1913
   695.2  736.55   834.1  737.82   938.6  743.41     979  752.19  1032.6  758.82
  1112.4  776.04  1143.1  789.88  1176.3  790.68  1204.5   802.5  1222.3  813.83
#Mann= 5 ,-1,0
       0      .1       0  579.95    .045       0  661.34      .1       0
    1090     .06       0    1220      .1       0
Bank Sta=579.95,661.34
XS Rating Curve= 0 ,0
Exp/Cntr(USF)=0,0
Exp/Cntr=0.3,0.1

Type RM Length L Ch R = 1 ,21507   ,497.5,500.8,501.4
XS GIS Cut Line= 6
1642105.03980485380219.242156252 1642302.7943306379982.956539586
1642368.64065559379908.7631184161642497.46323259379778.670530841
  1642627.275637379660.9709630911642974.35926042379372.096540838
#Sta/Elev= 30
       0  933.19    48.7  913.81    97.9  879.79   192.5   830.4     254  808.44
   290.3  789.73   332.8  775.32   373.1  745.43   401.4  730.03     430  733.41
     458  727.31   617.2  729.17  667.02723.5616   680.8  720.17   729.7  720.71
  737.66723.5602   761.4  739.08   789.3   740.6   800.6  754.26   813.6  765.12
   840.4  785.52   874.5  805.57   910.1  833.94   948.3  857.45   978.9  871.22
  1039.2  884.97  1072.7  896.59  1162.3  907.53  1195.4   922.6  1217.2  924.73
#Mann= 5 ,-1,0
       0      .1       0  667.02    .045       0  737.66      .1       0
  795.64     .06       0  928.21      .1       0
Bank Sta=667.02,737.66
XS Rating Curve= 0 ,0
Exp/Cntr(USF)=0,0
Exp/Cntr=0.3,0.1

Type RM Length L Ch R = 1 ,21007   ,496.7,500,502.8
XS GIS Cut Line= 6
1642297.79926184380502.9023500831642404.07267134 380479.32956259
1643190.72562559379855.6267417521643268.82487884379795.686244845
1643348.30076976379736.224749595 1643489.4451725379753.914674833
#Sta/Elev= 30
       0  911.36    31.1  906.53    63.8  893.52   142.2  845.72   171.3  821.37
   187.7  811.95     350  754.91   432.6  739.64   475.3  728.92   496.9  728.15
   535.5  732.69     564  725.07   654.2  728.28  665.18 723.085   671.8  720.74
     723  719.98  743.64723.0871   751.5  729.08   782.8  730.24   828.7  776.07
     886   804.2   996.4   877.9  1027.6  902.96    1038  908.35  1215.3  959.58
  1230.1  961.24    1273  977.96  1342.2  993.94  1411.1 1014.02  1452.7 1016.83
#Mann= 5 ,-1,0
       0      .1       0  298.08     .05       0  665.18    .045       0
  743.64     .06       0  829.64      .1       0
Bank Sta=665.18,743.64
XS Rating Curve= 0 ,0
Exp/Cntr(USF)=0,0
Exp/Cntr=0.3,0.1

Type RM Length L Ch R = 1 ,20507   ,523.4,528.3,532.5
BEGIN DESCRIPTION:
Structure 13 XS 4
END DESCRIPTION:
XS GIS Cut Line= 6
1642589.33966476380830.1892251191642657.59414592380814.181583166
1642755.04605076380781.7971335051643510.96251792380284.756132841
 1643593.2126815380230.6742200111643759.34456709380121.436577588
#Sta/Elev= 30
       0  874.12    72.8  860.16     136   823.4   152.8  808.43   183.1  789.09
   278.5  745.46   303.3  738.69   403.9  734.76     490  725.01   549.6  726.63
   590.6  732.52  639.16722.4871   656.8  719.62   695.9  719.62  705.28722.4865
     715   727.5   749.2  728.47   753.3  732.35   762.9  753.81   769.4  762.04
   789.7  779.23   820.4  799.54   849.1  826.42   911.3   858.9  1011.8  905.98
  1069.3  916.38  1187.1  952.25    1256  977.62  1337.4  993.42  1374.8 1004.66
#Mann= 5 ,-1,0
       0      .1       0  408.11     .05       0  639.16    .045       0
  705.28     .07       0  754.36      .1       0
Bank Sta=639.16,705.28
XS Rating Curve= 0 ,0
Exp/Cntr(USF)=0,0
Exp/Cntr=0.3,0.1

Type RM Length L Ch R = 1 ,19978   ,70.7,65.3,64.7
BEGIN DESCRIPTION:
Structure 13 XS 3
END DESCRIPTION:
XS GIS Cut Line= 4
1642890.06511035381163.1769524761643103.64600811381124.199446619
1643517.35380817380926.4655121161644153.43318835380908.773498696
#Sta/Elev= 30
       0  825.65    17.8  818.56    42.7  794.16    54.9  785.06    87.5  780.85
   115.9   762.1   132.2  754.66   201.3  736.66   247.2  733.97   403.8  734.99
   514.7  728.25  527.98721.0191   541.3  719.03  597.12721.0193   629.9  726.56
     661  726.83   686.4   748.1   718.4  760.63   742.4  766.52   931.7  792.68
   968.7  811.77  1010.5  829.47  1038.4  837.56  1110.6  867.61  1170.8   885.5
  1182.6  892.86  1198.6  895.02  1242.6  909.73  1274.6  915.55    1312  917.06
#Mann= 5 ,-1,0
       0      .1       0  247.11     .05       0  487.11     .07       0
  527.98    .045       0  597.12      .1       0
#XS Ineff= 2 , 0
          403.59  796.12
Permanent Ineff=
       F       F
Bank Sta=527.98,597.12
XS Rating Curve= 0 ,0
Exp/Cntr(USF)=0,0
Exp/Cntr=0.3,0.1

Type RM Length L Ch R = 1 ,19913   ,402.2,406.3,409.7
BEGIN DESCRIPTION:
Structure 13 XS 2
END DESCRIPTION:
XS GIS Cut Line= 4
1642914.26505089381206.3416556651643149.98055264381187.039353351
1643555.46669306380976.0122624711644176.90000194380952.556962984
#Sta/Elev= 30
       0  824.85    17.9   817.2    86.1  773.54     111  769.16     153   749.4
   218.6  734.56   356.2  735.29   484.5  728.51   500.4  726.29  511.26720.9929
   563.2  718.53  612.12720.9919   622.2  726.15   666.5  728.66   675.2  736.79
   684.8  757.06   687.8  760.72   701.4  767.96   802.3  790.36   869.5  798.77
   898.7  798.68   938.4  819.75   962.5  827.16  1034.5  855.67  1066.5  871.21
  1085.9  876.68  1178.6  914.63  1258.7  931.38  1290.7  930.07  1315.5  933.26
#Mann= 5 ,-1,0
       0      .1       0     230     .05       0   456.5     .07       0
  511.26    .045       0  612.12      .1       0
#XS Ineff= 2 , 0
          355.28  793.53
Permanent Ineff=
       F       F
Bank Sta=511.26,612.12
XS Rating Curve= 0 ,0
Exp/Cntr(USF)=0,0
Exp/Cntr=0.3,0.1

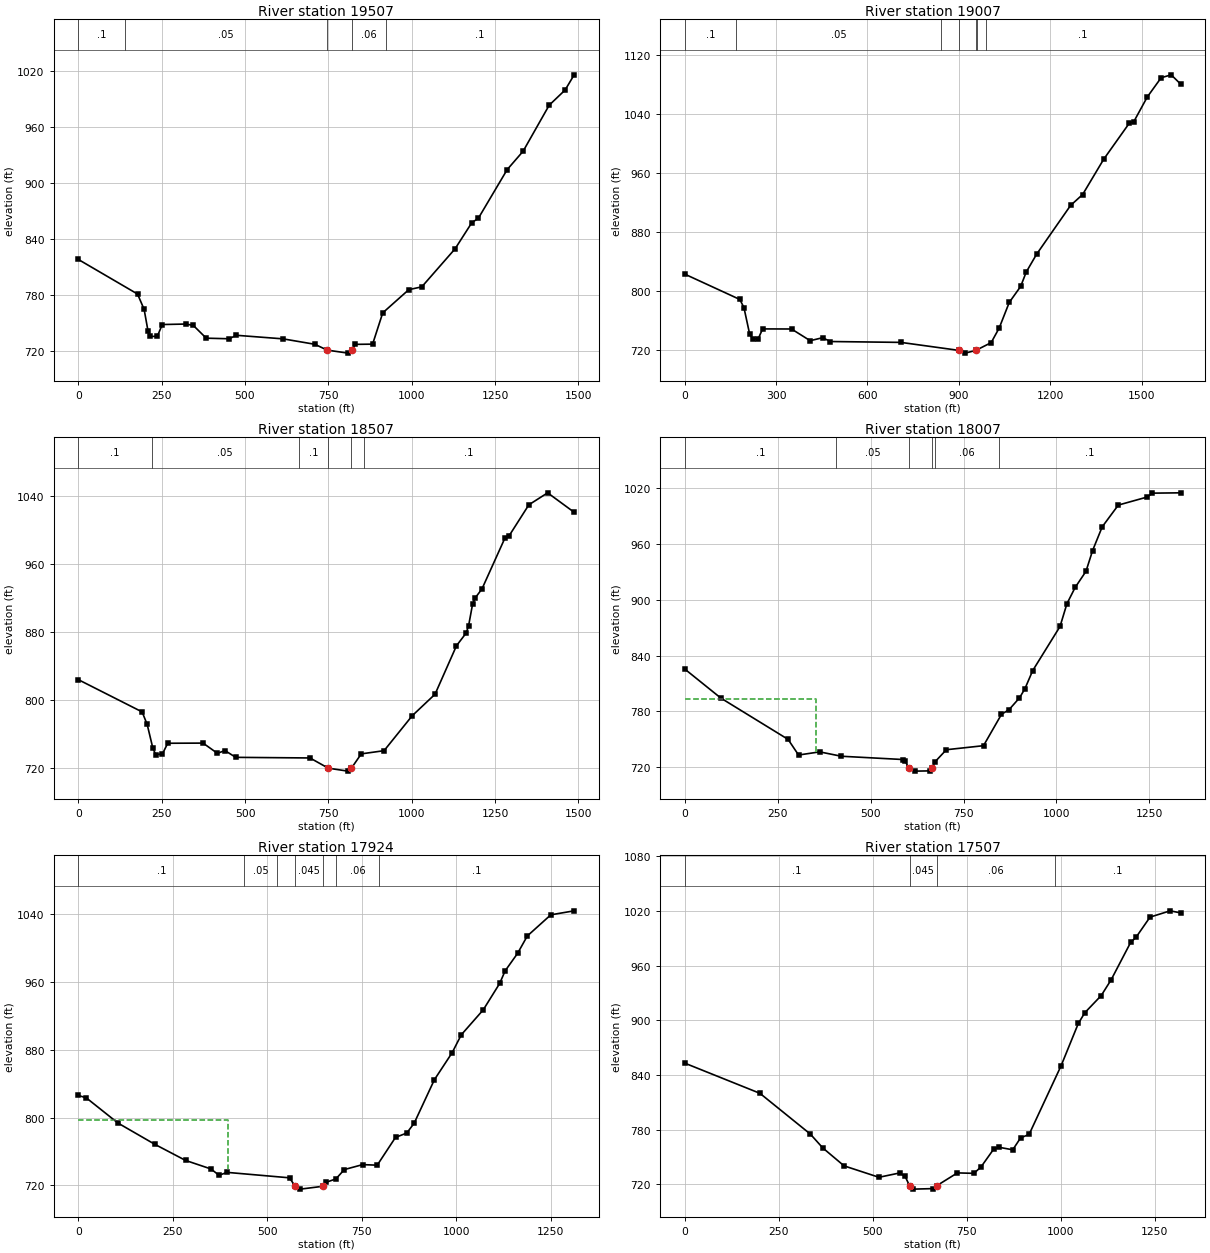
Type RM Length L Ch R = 1 ,19507   ,463.7,499.8,531.8
BEGIN DESCRIPTION:
Structure 13 XS 1
END DESCRIPTION:
XS GIS Cut Line= 6
1642948.06978177381229.606684499 1643200.8161566381465.775424346
1643326.33559059381514.7694208321643415.81047726381485.728140339
1643727.14712492381355.436406165 1644257.1093196381131.341053844
#Sta/Elev= 30
       0  817.98   177.6  780.82   197.4  764.34   209.3   740.6   215.2  735.21
     237  735.42   251.9  748.05   323.1  748.58     345  747.08   383.8  733.38
   452.5  732.75   474.1  736.49   614.1  732.66   709.5  726.83  746.67720.5557
   809.2  717.32  820.45720.5592   830.9  726.74   882.9  726.97   913.3  760.61
   991.4   785.5  1030.5  788.56  1130.4  829.45  1180.8  857.63  1199.9  862.09
  1286.7  914.56  1334.5  934.31  1412.7  983.74  1460.5 1000.08  1487.6 1016.37
#Mann= 5 ,-1,0
       0      .1       0     140     .05       0  746.67    .045       0
  820.45     .06       0  922.23      .1       0
Bank Sta=746.67,820.45
XS Rating Curve= 0 ,0
Exp/Cntr(USF)=0,0
Exp/Cntr=0.3,0.1

Type RM Length L Ch R = 1 ,19007   ,470.1,500.2,528.4
XS GIS Cut Line= 6
1642933.94075781381235.2960796461643021.80175084381329.926614672
1643210.55334184381523.7700590041643454.75954634381717.706350923
1643576.25175743381831.6162280891644139.37661542382327.576522261
#Sta/Elev= 30
       0  823.23   180.7  788.95   194.2     778   212.7  742.58   223.1  735.36
   241.4  735.91   255.6  749.05   350.5  748.93   411.9  733.08   452.5  737.13
   478.2  731.97   709.7  730.79  901.12 719.918   920.6  716.25  955.66719.9188
  1006.2  730.44  1032.7  750.36  1065.7  784.97  1103.2  806.64  1121.3  825.99
  1155.2  850.04  1267.1   916.3  1306.6  931.03  1375.6  978.68  1459.6 1027.48
  1474.9 1029.86  1519.1 1063.24  1564.5  1089.2  1597.5 1093.16  1628.5 1080.64
#Mann= 7 ,-1,0
       0      .1       0  169.13     .05       0  843.05     .06       0
  901.12    .045       0  955.66     .06       0  958.08     .08       0
  988.08      .1       0
Bank Sta=901.12,955.66
XS Rating Curve= 0 ,0
Exp/Cntr(USF)=0,0
Exp/Cntr=0.3,0.1

Type RM Length L Ch R = 1 ,18507   ,484.9,500,513.2
XS GIS Cut Line= 6
1642910.74562166381241.6841298881643131.08630918381524.362249419
1643186.87622385381631.9427429291643131.87928659381983.922353923
1643113.50596376382145.5227525091643064.16518317382631.623814419
#Sta/Elev= 30
       0  823.61   191.3  785.66   206.5   770.9   223.4  743.17   231.8  735.54
   252.1  736.12   268.1  748.79   374.1  748.97   417.2  736.93   439.7  740.21
   472.1  732.21   694.8  731.49  749.68719.4769   808.1     716  818.99719.4713
   848.6   736.3     917  740.05  1001.5   781.2  1069.9  806.48  1134.2  863.51
    1163  878.35  1170.3  886.63  1182.5  912.58  1190.5  919.86  1210.6  930.33
  1278.9  989.68    1291  992.19  1351.3 1029.31  1407.6 1043.37  1487.1 1020.49
#Mann= 6 ,-1,0
       0      .1       0     220     .05       0  660.84      .1       0
  749.68    .045       0  818.99     .06       0  855.85      .1       0
Bank Sta=749.68,818.99
XS Rating Curve= 0 ,0
Exp/Cntr(USF)=0,0
Exp/Cntr=0.3,0.1

Type RM Length L Ch R = 1 ,18007   ,82.6,82.5,82
BEGIN DESCRIPTION:
Structure 12 XS 3
END DESCRIPTION:
XS GIS Cut Line= 6
1642885.21402845381228.3187833281642849.19251601381553.342178345
1642787.42689151381624.6402640941642737.74818508381696.671944171
1642495.25326325382053.2850760821642273.62378526382379.210277259
#Sta/Elev= 30
       0  825.55    96.8  794.39   277.9  749.88   306.1  733.04     363  736.43
   421.2  731.72   586.1  728.21   592.9  726.63  602.56719.0383   619.9   715.7
   658.6  715.96  664.83719.0435   673.1  725.63   703.8  738.74   803.8  743.09
   852.1  776.79   872.7  781.95   900.5   794.5     915   804.2   936.1  823.86
  1009.7  871.42  1028.2  895.87  1050.4  913.41  1079.5  930.77  1097.3  953.12
  1123.2  978.68  1166.5 1002.07  1243.9 1010.71  1258.4 1014.93  1334.2 1015.27
#Mann= 6 ,-1,0
       0      .1       0  407.01     .05       0  602.56    .045       0
  664.83      .1       0  673.85     .06       0  846.35      .1       0
#XS Ineff= 2 , 0
          354.28  792.93
Permanent Ineff=
       F       F
Bank Sta=602.56,664.83
XS Rating Curve= 0 ,0
Exp/Cntr(USF)=0,0
Exp/Cntr=0.3,0.1

Type RM Length L Ch R = 1 ,17924   ,416.7,417.5,414.6
BEGIN DESCRIPTION:
Structure 12 XS 2
END DESCRIPTION:
XS GIS Cut Line= 6
1642824.40396708381203.4916361581642806.21685746 381367.66066391
1642782.49234724381505.7696252681642720.72672274381577.067711017
1642671.04801631381649.0993910941642206.92361649382331.637724182
#Sta/Elev= 30
       0  826.03    21.2  823.12   104.9  793.49   202.6  768.42   283.8  749.49
   351.3  739.39   372.5  731.94   393.6  735.41     559  728.99  574.05718.9709
     588  715.67  646.63718.9709   655.8  723.71   681.8  727.69   704.1  738.69
   752.5  744.53   791.2  743.88   839.6  776.61   869.4  781.72   889.1  793.42
   942.5  844.52   989.5  876.34  1013.7  897.43  1071.8   926.8  1115.3  957.89
  1129.8  972.76  1162.6  993.25  1188.5 1013.82  1250.7 1038.74  1312.5 1043.44
#Mann= 7 ,-1,0
       0      .1       0  439.64     .05       0  527.14      .1       0
  574.05    .045       0  646.63      .1       0  682.14     .06       0
  797.14      .1       0
#XS Ineff= 2 , 0
          396.55  797.16
Permanent Ineff=
       F       F
Bank Sta=574.05,646.63
XS Rating Curve= 0 ,0
Exp/Cntr(USF)=0,0
Exp/Cntr=0.3,0.1

Type RM Length L Ch R = 1 ,17507   ,502.4,500,495.7
BEGIN DESCRIPTION:
Structure 12 XS 1
END DESCRIPTION:
XS GIS Cut Line= 6
1642491.26240723380940.7835454261642495.19978568381156.778667003
 1642443.4062541381238.645629257 1642306.4045596381455.197361499
1642166.06100826381677.0302511751641905.21408901382089.336513177
#Sta/Elev= 30
       0  853.11   199.8  820.04     334  775.33   367.2  760.09   423.9  740.41
   516.7  727.88   571.8  732.63   586.3  728.88     598718.7058   608.6  714.89
   660.7  715.46   670.8718.7108   725.4   732.7   769.5  732.21   788.5  739.36
   821.6  758.55   835.8  760.85   872.7  758.04   893.6  771.11   916.3  774.95
  1001.5  850.35  1047.2  896.64  1064.6  908.49  1108.1  927.24  1134.6  944.58
  1186.4  985.52  1200.9  991.26  1238.1 1013.35  1291.7 1020.25  1319.5 1017.98
#Mann= 4 ,-1,0
       0      .1       0     598    .045       0   670.8     .06       0
  985.41      .1       0
Bank Sta=598,670.8
XS Rating Curve= 0 ,0
Exp/Cntr(USF)=0,0
Exp/Cntr=0.3,0.1

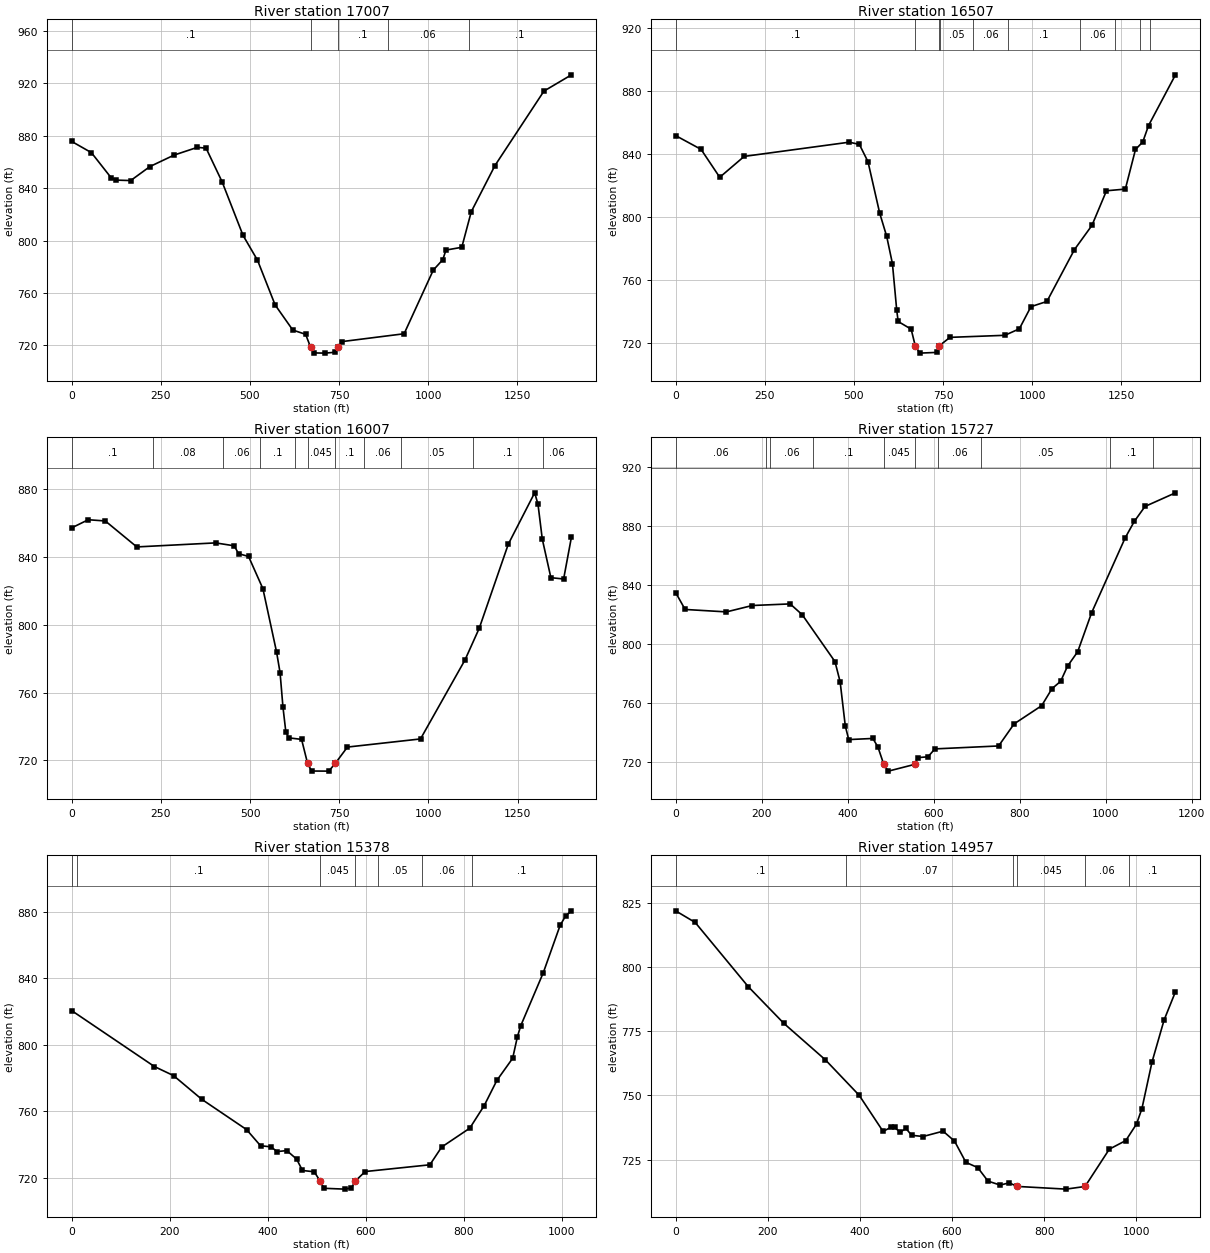
Type RM Length L Ch R = 1 ,17007   ,509.9,500,485.5
XS GIS Cut Line= 6
1642156.85728651380620.5218655021642122.18937685380714.568593428
1641789.31504259381359.5128415821641750.58382083 381437.98971875
1641709.73941433381522.4094974251641539.89132884381878.288050756
#Sta/Elev= 30
       0  875.74    55.4  867.15   111.5  847.71     125  846.18   165.5  845.83
   219.5  856.54   287.3   865.3   352.6  871.21     377  870.58     422   844.8
   480.6  803.95   521.1  785.03   570.6  750.82   620.1  731.65   656.1  728.37
  670.01718.5491   678.6  714.19   710.1  714.02   737.1  714.64   746.4718.5533
   758.9  722.86   932.3  728.82  1014.1  777.46  1040.7  785.39  1049.6  792.74
    1094  794.86  1120.6  822.04  1187.1  857.33  1324.4  914.18  1401.6   926.6
#Mann= 5 ,-1,0
       0      .1       0  670.01    .045       0   746.4      .1       0
  886.01     .06       0 1114.23      .1       0
Bank Sta=670.01,746.4
XS Rating Curve= 0 ,0
Exp/Cntr(USF)=0,0
Exp/Cntr=0.3,0.1

Type RM Length L Ch R = 1 ,16507   ,506.9,500,491.2
XS GIS Cut Line= 6
1641469.40229659 380389.924885751641358.86806884381207.880927011
1641344.39270408381294.219993174  1641327.408158381386.526895165
1641271.44928043381676.2152921711641256.01886509381775.145212427
#Sta/Elev= 30
       0  851.91    71.3  843.15   123.7  825.41   192.3  838.68   486.9  847.71
   515.3  846.32   539.5  835.33   572.4   802.6   591.9  787.97   608.1  770.55
   620.2  740.85   624.2  733.78   660.6   728.9  672.03718.4188   684.8  713.68
   733.2  714.15  740.05718.4219   769.5   723.7   923.4     725   964.1  729.12
   996.6  743.21  1041.4  746.51  1118.8  779.51  1167.7  794.82  1208.5  816.84
  1261.4  817.91  1289.9  843.08  1310.3  847.87  1326.5  858.28    1402  890.51
#Mann= 10 ,-1,0
       0      .1       0  672.03    .045       0  740.05      .1       0
  740.39     .05       0  835.39     .06       0  932.93      .1       0
 1133.81     .06       0 1232.42      .1       0 1301.84     .06       0
 1331.84      .1       0
Bank Sta=672.03,740.05
XS Rating Curve= 0 ,0
Exp/Cntr(USF)=0,0
Exp/Cntr=0.3,0.1

Type RM Length L Ch R = 1 ,16007   ,278.4,279.4,280.8
XS GIS Cut Line= 6
1640815.62145193380398.6450126771640824.35338984380497.870864093
1640872.63478935 381046.531840251640887.97563793381220.857935175
1640929.68257551381694.8077746781640938.41451342381794.033626094
#Sta/Elev= 30
       0  857.28    46.5  862.09    94.3  861.36   182.6  846.04   403.4  848.42
   455.6   846.7   467.7  842.07   495.8  840.41     536  821.39   574.3     784
   584.1  771.82   592.2  751.51   600.2  736.96   608.2  733.36   644.4  732.44
  661.17718.2855   672.5  713.77   720.7  713.71  738.83718.2886   772.9  727.91
   977.7  732.71  1102.3   779.3  1142.3  798.04  1223.8   847.7  1297.6  877.97
  1306.9  871.33    1319  850.65  1343.1  827.89  1378.8  827.11  1400.8  851.97
#Mann= 11 ,-1,0
       0      .1       0  228.83     .08       0  424.14     .06       0
  527.89      .1       0  625.39    .025       0  661.17    .045       0
  738.83      .1       0  820.39     .06       0  922.89     .05       0
 1123.52      .1       0 1321.17     .06       0
Bank Sta=661.17,738.83
XS Rating Curve= 0 ,0
Exp/Cntr(USF)=0,0
Exp/Cntr=0.3,0.1

Type RM Length L Ch R = 1 ,15727   ,347.2,348.9,350.9
XS GIS Cut Line= 2
1640572.07444884380606.5603484721640632.19765545381767.199641385
#Sta/Elev= 30
       0  834.99      22  823.49   118.1  821.83   178.2  826.17   266.3  827.26
   294.4  819.89   370.5  788.05   382.5   774.3   394.5  744.24   402.5  735.04
   458.6  735.81   470.3  730.03  484.01718.1641   494.6   713.6  555.57718.1625
   562.7  722.76   586.8  723.34   602.8  728.71     751  730.71     787   745.7
   851.1  758.09   875.1  769.65   895.2  774.65   911.2  784.92   934.9  794.79
   967.3  821.28  1045.3  872.15  1066.5  883.34  1091.4   893.5  1162.2  902.76
#Mann= 10 ,-1,0
       0     .06       0     210     .07       0     220     .06       0
     320      .1       0  484.01    .045       0  555.57    .025       0
     610     .06       0     710     .05       0    1010      .1       0
    1110     .08       0
Bank Sta=484.01,555.57
XS Rating Curve= 0 ,0
Exp/Cntr(USF)=0,0
Exp/Cntr=0.3,0.1

Type RM Length L Ch R = 1 ,15378   ,373,421.4,527.2
BEGIN DESCRIPTION:
Structure 11 XS 4
END DESCRIPTION:
XS GIS Cut Line= 4
1640488.42477007380679.7538173951640250.54599607 380982.98390293
1640250.54599607381375.0917721581640182.58063207381607.742441232
#Sta/Elev= 30
       0  820.48     169  786.85   207.9  781.43   265.7  767.15   356.9     749
   385.4  739.31     407  738.62     419   735.8     439  736.38     459   731.3
     471  724.44     495  723.66  507.08718.0577     515  713.74   557.4  713.24
     571  714.01  578.61718.0584     599   723.8     731  727.86     755  738.51
   812.4  749.85   841.9  763.46   867.7  778.57   899.9  791.84   909.6  804.84
   916.5  811.46   962.4  843.25   996.7  871.65  1008.2  877.46  1019.9  880.41
#Mann= 7 ,-1,0
       0     .06       0      10      .1       0  507.08    .045       0
  578.61     .06       0   625.4     .05       0   715.4     .06       0
  817.51      .1       0
Bank Sta=507.08,578.61
XS Rating Curve= 0 ,0
Exp/Cntr(USF)=0,0
Exp/Cntr=0.3,0.1

Type RM Length L Ch R = 1 ,14957   ,128.8,132.4,103.6
BEGIN DESCRIPTION:
Structure 11 XS 3
END DESCRIPTION:
XS GIS Cut Line= 6
 1640468.5643215380665.946884345 1639978.4493915381079.793929831
1639882.17681596381086.0453957751639750.89603114381094.797448096
 1639655.8737488 381101.048914041639607.11231443381211.074714653
#Sta/Elev= 30
       0  821.83    42.5   817.3   157.6  792.34   234.9  778.06   325.2  763.85
   398.5  750.07   450.4  736.02   466.5  737.57   475.2  737.58   487.5  735.73
     500  737.18   512.4  734.52   537.2  734.05   580.6  736.12   605.4  732.28
   630.2  723.99   655.8  721.96   678.2  716.69   704.6  715.16     724  716.02
   741.8  714.63   847.5  713.58   888.8  714.61   941.5  729.12   977.3  732.48
  1000.6  738.91  1012.3   744.9  1034.2  763.02  1060.4  779.35  1085.1  790.36
#Mann= 6 ,-1,0
       0      .1       0     370     .07       0  731.47     .06       0
   741.8    .045       0   888.8     .06       0  984.74      .1       0
Bank Sta=741.8,888.8
XS Rating Curve= 0 ,0
Exp/Cntr(USF)=0,0
Exp/Cntr=0.3,0.1

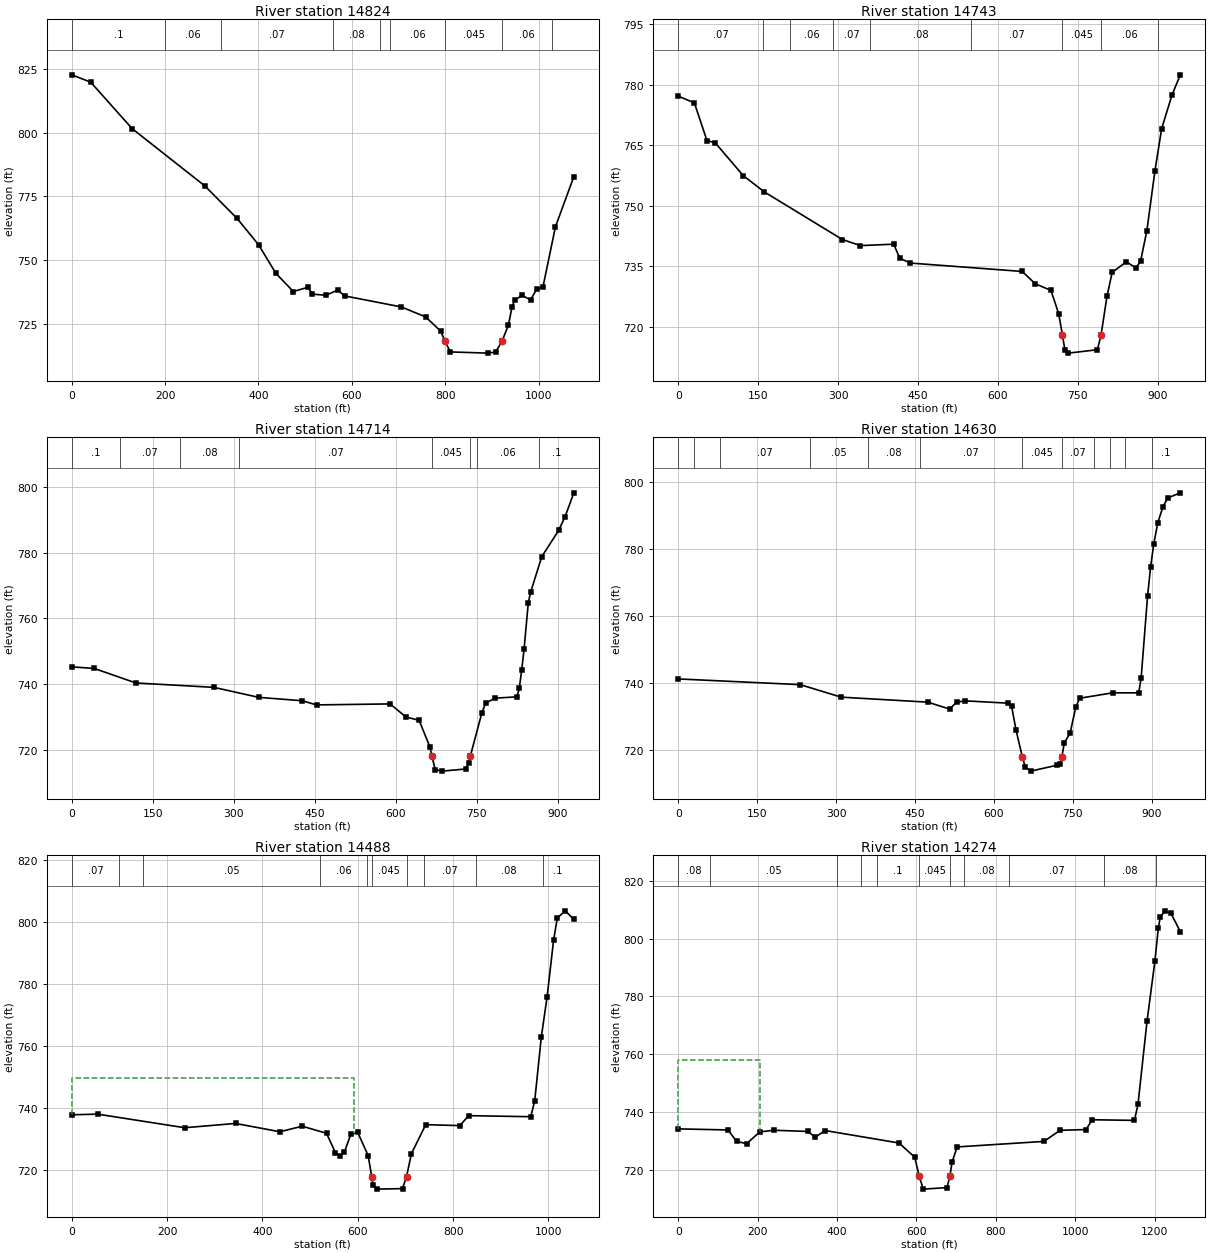
Type RM Length L Ch R = 1 ,14824   ,124.1,81.8,24.7
BEGIN DESCRIPTION:
Structure 11 XS 2
END DESCRIPTION:
XS GIS Cut Line= 6
 1640446.0590441380637.1901410031639904.68209336381017.279270392
1639843.41772711381023.5307363361639780.90306767381021.030149958
1639629.61759183 381039.784547791639572.10410515381164.813866668
#Sta/Elev= 30
       0  822.66    40.6  819.77   129.4  801.52   285.2  779.03   354.3  766.25
   400.1  755.97   437.4  744.69   474.7  737.58   505.8  739.24   515.6  736.56
   544.9   736.1   569.7  738.15   584.8  735.85   706.3  731.52   758.4  727.58
   790.5  721.99  800.01718.0206   810.9  713.86   891.5  713.39   907.9  713.81
  921.71718.0201   935.6  724.46   943.3  731.56   948.8  734.23   965.3  736.06
   982.9  734.26   996.1  738.53  1009.4  739.26  1036.3  763.01  1075.7  782.71
#Mann= 9 ,-1,0
       0      .1       0     200     .06       0     320     .07       0
     560     .08       0     660     .07       0  681.48     .06       0
  800.01    .045       0  921.71     .06       0 1028.08      .1       0
Bank Sta=800.01,921.71
XS Rating Curve= 0 ,0
Exp/Cntr(USF)=0,0
Exp/Cntr=0.3,0.1

Type RM Length L Ch R = 1 ,14743   ,29.1,28.4,27.5
BEGIN DESCRIPTION:
Structure 10 XS 4 AND Structure 11 XS 1
END DESCRIPTION:
XS GIS Cut Line= 4
1640207.25304505380489.6555447271639665.87609431380948.513145009
1639580.85615747381108.5506731731639568.35322558381158.562400724
#Sta/Elev= 30
       0  777.24    30.3  775.56    53.9  766.23    69.5  765.65     122  757.53
   161.4  753.51   308.2  741.68     342  740.18   404.4  740.53   415.8  737.06
   435.7  735.85   645.7  733.77     670  730.72   699.6  729.07   714.2  723.25
   721.1717.9901   725.8  714.34   732.3  713.52   786.7  714.36  793.61717.9844
   804.8  727.63   814.5  733.55   841.1  736.16   859.2  734.64   867.8  736.33
   879.6  743.85   894.8  758.74   907.4   769.2   926.9  777.56   942.4  782.52
#Mann= 9 ,-1,0
       0     .07       0     160     .08       0     210     .06       0
     290     .07       0     360     .08       0     550     .07       0
   721.1    .045       0  793.61     .06       0  900.89      .1       0
Bank Sta=721.1,793.61
XS Rating Curve= 0 ,0
Exp/Cntr(USF)=0,0
Exp/Cntr=0.3,0.1

Type RM Length L Ch R = 1 ,14714   ,85.5,83.8,81.3
BEGIN DESCRIPTION:
Structure 10 XS 3
END DESCRIPTION:
XS GIS Cut Line= 3
1639933.81519743  380347.01734781639560.00569543381094.636351793
1639562.61974789381188.742240407
#Sta/Elev= 30
       0  745.25    41.9  744.74   118.7  740.33   263.2  738.99   346.1  735.95
   426.6  734.91   453.4  733.64   589.7  733.94   618.9  729.96   643.4  728.94
   663.6  720.74  667.16717.9764   673.2  713.91   685.9  713.45   729.9  714.11
   735.1  715.93  738.14717.9763   759.7  731.26   766.4  734.11   783.5  735.69
   824.6   736.1     829  738.76   833.5  744.43   837.8  750.65   845.6  764.76
   849.8  767.94   870.6  778.84   901.8  786.83   913.8  791.05     930   798.3
#Mann= 8 ,-1,0
       0      .1       0      90     .07       0     200     .08       0
     310     .07       0  667.16    .045       0  738.14     .07       0
     750     .06       0  865.86      .1       0
Bank Sta=667.16,738.14
XS Rating Curve= 0 ,0
Exp/Cntr(USF)=0,0
Exp/Cntr=0.3,0.1

Type RM Length L Ch R = 1 ,14630   ,144.4,142,139.8
BEGIN DESCRIPTION:
Structure 10 XS 2
END DESCRIPTION:
XS GIS Cut Line= 3
1639824.02499404380299.9644034931639492.04033143381060.653669793
1639550.74216521381170.258649397
#Sta/Elev= 30
       0  741.18   231.9  739.47   309.8  735.73   474.3  734.24   515.6  732.18
     529  734.19   544.2  734.64   626.3  733.94   633.5  733.09   642.2   725.8
  653.92717.9354   659.6  714.83   669.8  713.62   720.5   715.4   725.1  715.83
  729.24717.9362   733.8  722.09   744.8  724.96   755.7  732.82     763  735.41
   825.5  737.02   875.2  737.02   879.8  741.37     892  765.85   897.9  774.75
   903.8  781.46   911.5  787.91   921.5  792.71   930.4  795.27   954.3  796.81
#Mann= 12 ,-1,0
       0     .08       0      30      .1       0      80     .07       0
     250     .05       0     360     .08       0     460     .07       0
  653.92    .045       0  729.24     .07       0     790     .06       0
     820     .08       0  849.98     .06       0  899.98      .1       0
Bank Sta=653.92,729.24
XS Rating Curve= 0 ,0
Exp/Cntr(USF)=0,0
Exp/Cntr=0.3,0.1

Type RM Length L Ch R = 1 ,14488   ,215.1,214.7,215.5
BEGIN DESCRIPTION:
Structure 9 XS 4 AND Structure 10 XS 1
END DESCRIPTION:
XS GIS Cut Line= 3
1639648.71860416380237.5666270591639375.57626246380997.706942342
1639547.32855744381173.324381746
#Sta/Elev= 30
       0  737.79    54.2     738   236.9  733.62   343.6     735   436.7  732.32
   483.5  734.11   534.5  731.83   553.1  725.61   562.5  724.55   571.9  725.72
   585.5  731.52     600   732.1   621.9  724.64   629.2717.8796   632.2  715.04
   640.7  713.84   693.9  714.01  702.39 717.883   712.6  725.27   742.7  734.62
   814.2   734.3   832.7  737.51   962.9  737.17   971.3  742.25   985.1  762.78
   997.3  775.82  1010.9  794.02  1018.7   801.2  1035.5   803.5  1053.4  800.71
#Mann= 10 ,-1,0
       0     .07       0     100      .1       0     150     .05       0
     520     .06       0     620     .08       0   629.2    .045       0
  702.39     .08       0     740     .07       0  847.73     .08       0
  987.73      .1       0
#XS Ineff= 2 , 0
           591.8  749.66
Permanent Ineff=
       F       F
Bank Sta=629.2,702.39
XS Rating Curve= 0 ,0
Exp/Cntr(USF)=0,0
Exp/Cntr=0.3,0.1

Type RM Length L Ch R = 1 ,14274   ,98.6,98.6,99.1
BEGIN DESCRIPTION:
Structure 9 XS 3
END DESCRIPTION:
XS GIS Cut Line= 3
1639463.18202935380155.1036261451639183.47841597380897.494525215
1639554.67386551381187.654348443
#Sta/Elev= 30
       0  734.14   125.5  733.77   146.9  729.82   172.5  729.03   205.3  733.09
   240.9  733.66   326.4  733.25     345  731.26   369.9  733.57   556.1  729.25
   595.7  724.33  606.61 717.829   617.1  713.29   676.9  713.82  684.29717.8265
   689.7  722.68   702.5  727.89   921.1  729.81   961.7  733.65  1026.8   733.9
  1042.9   737.3    1149  737.08  1157.9   742.6  1180.6  771.32  1200.6  792.31
  1209.1  803.65    1214  807.42  1225.7   809.6  1240.9  808.73  1264.5  802.41
#Mann= 11 ,-1,0
       0     .08       0      80     .05       0     400     .08       0
     460     .06       0     500      .1       0  606.61    .045       0
  684.29      .1       0     720     .08       0  833.33     .07       0
 1073.33     .08       0 1203.33      .1       0
#XS Ineff= 2 , 0
          205.32  757.93
Permanent Ineff=
       F       F
Bank Sta=606.61,684.29
XS Rating Curve= 0 ,0
Exp/Cntr(USF)=0,0
Exp/Cntr=0.3,0.1